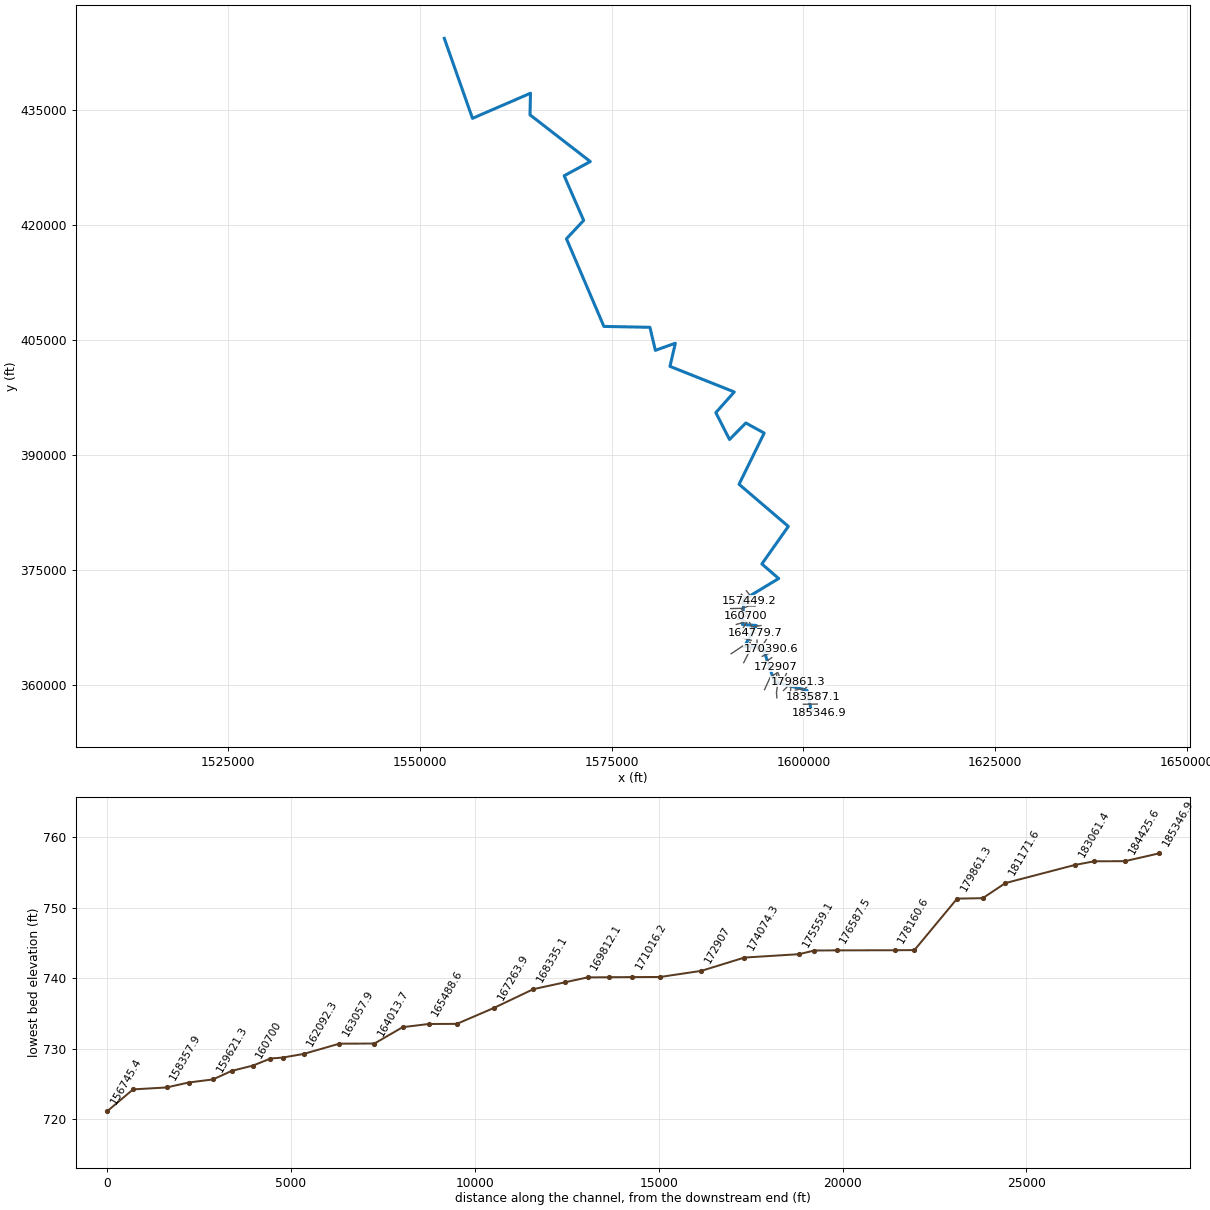
--- EFTWELVECR.prj (project) ---

Proj Title=EFTWELVECR
Current Plan=p01
Default Exp/Contr=0,0
English Units
Geom File=g01
Flow File=f01
Plan File=p01
BEGIN DESCRIPTION:
END DESCRIPTION:
DSS Export Rating Curves= 0
DSS Export Rating Curve Sorted= 0
DSS Export Volume Flow Curves= 0
DXF OffsetX= 0
DXF OffsetY= 0
DXF ScaleX= 0
DXF ScaleY= 0

--- EFTWELVECR.p01 (plan) ---

Plan Title=Floodplain
Program Version=4.00
Geom File=g01
Flow File=f01
K Sum by GR=0
Std Step Tol=0.01
Critical Tol=0.01
Num of Std Step Trials=20
Max Error Tol=0.3
Flow Tol Ratio=0.001
Split Flow NTrial=30
Split Flow Tol=0.02
Split Flow Ratio=0.02
Log Output Level=0
Friction Slope Method=1
Unsteady Friction Slope Method=2
Unsteady Bridges Friction Slope Method=1
Global Log Level=0
CheckData=False
Run HTab=0
Run UNet=0
Run PostProcess=0
UNET Theta=0
UNET Theta Warmup=0
UNET ZTol=0
UNET ZSATol=0
UNET MxIter=0
UNET MaxInSteps=0
UNET DtIC=0
UNET DtMin=0
UNET MaxCRTS=0
UNET WFStab=0
UNET SFStab=0
UNET WFX=0
UNET SFX=0
UNET DSS MLevel=0
UNET DZMax Abort=0
UNET Convert EG Bridges=0
UNET Use Existing IB Tables=0
UNET Froude Limit=0
UNET Froude Power=0
Write IC File=0
Echo Input=False
Echo Output=False
Write Detailed=0

--- EFTWELVECR.f01 (steady flow) ---

Flow Title=NFF Regression Equation
Program Version=4.00
Number of Profiles= 1
Profile Names=P100yr
River Rch & RM=EFTWELVECR,Main            ,185346.9
3894.178
River Rch & RM=EFTWELVECR,Main            ,178160.6
4170.536
River Rch & RM=EFTWELVECR,Main            ,169182.5
4632.249
River Rch & RM=EFTWELVECR,Main            ,158958.5
5041.595
River Rch & RM=EFTWELVECR,Main            ,158357.9
5369.935
River Rch & RM=EFTWELVECR,Main            ,140646.4
5805.062
River Rch & RM=EFTWELVECR,Main            ,128367
6116.884
River Rch & RM=EFTWELVECR,Main            ,128053.3
 6934.42
River Rch & RM=EFTWELVECR,Main            ,118011.6
7080.205
River Rch & RM=EFTWELVECR,Main            ,117554
9958.279
River Rch & RM=EFTWELVECR,Main            ,91139.3
11032.24
River Rch & RM=EFTWELVECR,Main            ,75788.7
12226.23
River Rch & RM=EFTWELVECR,Main            ,68550.2
13266.49
River Rch & RM=EFTWELVECR,Main            ,53955.6
14329.66
River Rch & RM=EFTWELVECR,Main            ,40866.1
15534.38
Boundary for River Rch & Prof#=EFTWELVECR,Main            , 1
Up Type= 0
Dn Type= 3
Dn Slope=0.0007
DSS Import GetInterval= 0
DSS Import GetPeak= 0
DSS Import FillOption= 0

--- EFTWELVECR.g01 (geometry) ---

Geom Title=Geometry
Program Version=4.00

River Reach=EFTWELVECR      ,Main
Reach XY= 30
     1601040.178      356659.002     1600475.226       359334.24
     1596227.665      360442.039     1594708.409      364959.145
     1592290.163      365021.305     1593866.415      367792.202
      1592052.34      367918.322     1592237.254      371164.263
     1596781.203      373909.605      1594590.37      375809.525
     1598039.376      380700.071     1591617.436      386193.222
     1594893.256      392865.288     1592500.284      394178.295
     1590377.134      392025.874     1588592.856      395526.812
     1590996.615      398225.043     1582615.953      401554.109
     1583315.463      404575.302     1580710.542      403644.053
      1580002.45       406648.08     1574004.181      406762.118
     1569123.982      418185.546      1571366.42       420579.93
     1568826.554      426395.315      1572232.54      428247.496
     1564374.285      434335.307     1564438.055      437152.687
     1556877.327      433880.649     1553204.459      444306.494

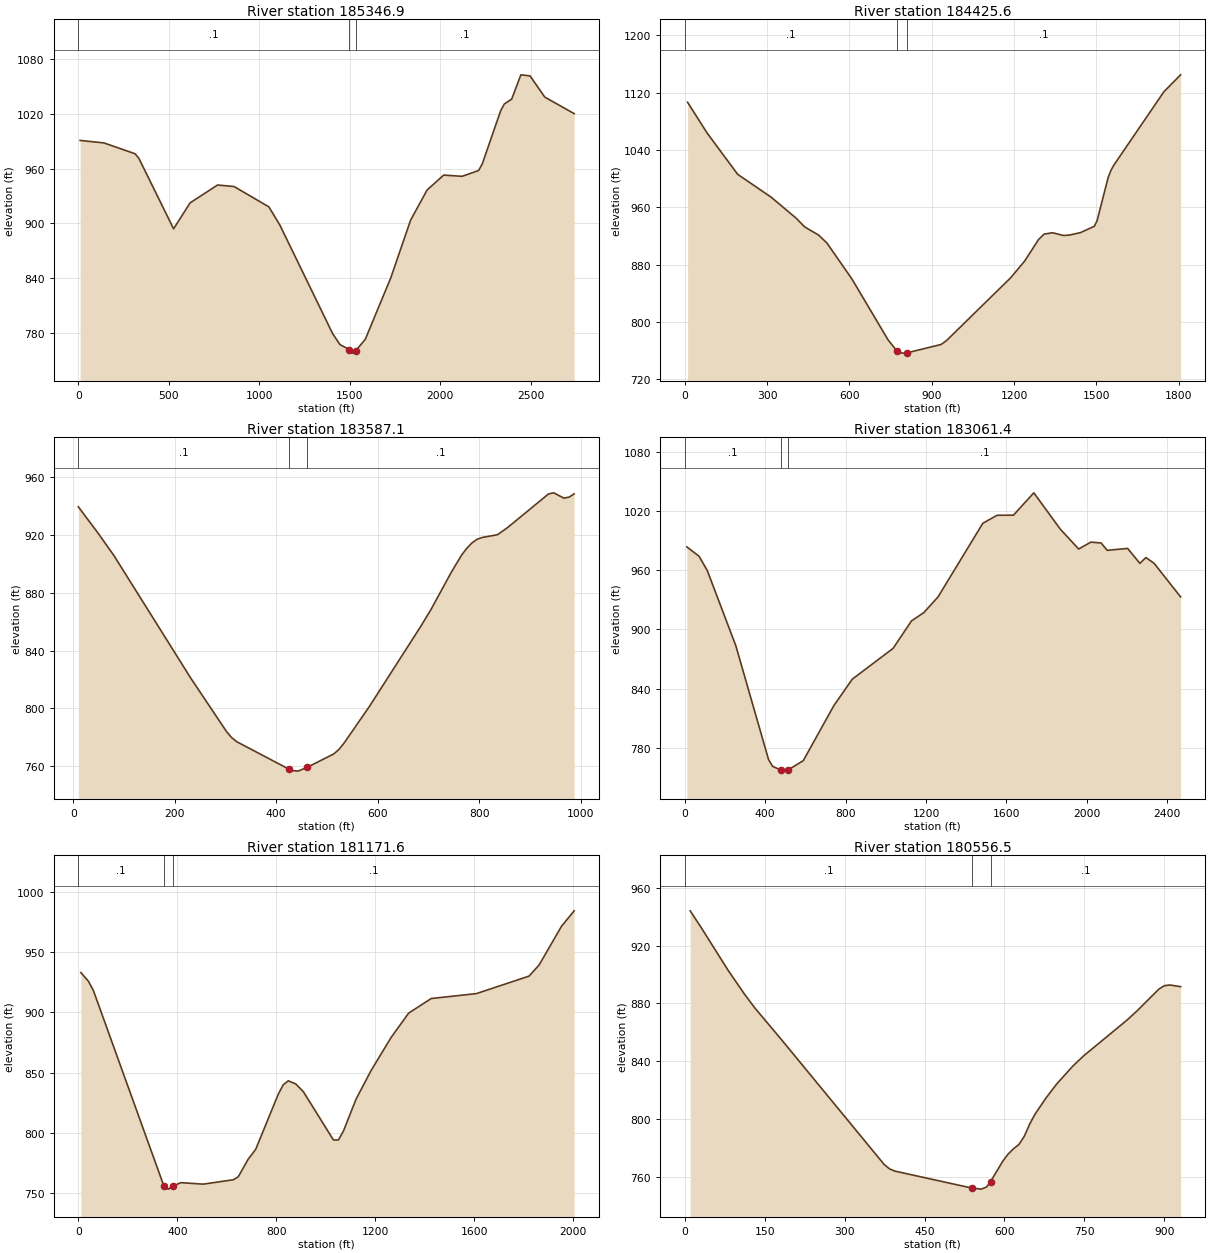
Type RM Length L Ch R = 1 ,185346.9,929.8,921.3,913.3
XS GIS Cut Line= 4
     1599535.114      356399.327     1600737.612      356632.913
     1601323.746      356805.773     1602094.865      356334.873
#Sta/Elev= 30
    10.1  991.04   141.7  988.27   313.8  976.37   334.1  971.56   526.4  894.05
   617.5  922.53   769.4  942.12   860.5  940.44  1052.9  918.12  1113.6  898.17
  1405.3  779.04  1445.4  767.14    1498  761.56  1515.5  757.71    1533  760.44
  1585.6  772.91  1725.9  840.02  1836.1  903.65  1927.4  936.73  2018.8     953
  2120.3  951.65  2211.7  958.01    2232  965.32  2333.5 1023.56  2353.8 1031.03
  2394.4 1036.29  2445.2 1062.97    2496 1061.79  2577.2 1038.58  2739.6 1020.41
#Mann= 3 , 0 , 0
       0      .1       0    1498    .045       0    1533      .1       0
Bank Sta=1498,1533
XS Rating Curve= 0 ,0
Exp/Cntr=0.3,0.1

Type RM Length L Ch R = 1 ,184425.6,826.8,838.4,850.8
XS GIS Cut Line= 2
     1600002.865      357523.775     1601809.968      357549.014
#Sta/Elev= 30
    10.2 1106.49    81.2 1063.67   192.9 1005.95   314.8   974.1   406.1  944.78
   436.6  932.75   487.4  921.32   517.8  910.35   609.2  860.02   741.2  774.95
   774.5  759.09     792  756.61   809.5  756.96   934.1  768.67   954.4  774.26
  1187.9  861.76  1238.7  884.96  1289.5  915.05  1309.8  922.63  1340.2  924.48
  1380.8  920.66  1401.1  921.21  1441.8  924.62  1492.5  933.46  1502.7  941.21
  1543.3 1001.68  1553.4 1011.55  1563.6 1018.62  1746.4 1121.23  1807.3 1144.76
#Mann= 3 , 0 , 0
       0      .1       0   774.5    .045       0   809.5      .1       0
Bank Sta=774.5,809.5
XS Rating Curve= 0 ,0
Exp/Cntr=0.3,0.1

Type RM Length L Ch R = 1 ,183587.1,527.7,525.7,523.8
XS GIS Cut Line= 2
     1600341.066      358063.887      1601239.57      358472.757
#Sta/Elev= 30
    10.1  939.44    50.4  920.53    80.6  905.52   231.7   820.9   302.2  783.92
   312.3  779.76   322.3  776.93   425.7  757.86   433.1  756.92   443.2  756.59
   460.7  759.16   513.7  768.52   523.8  771.64   533.9  776.05   584.2  801.58
     685  856.77   705.1  868.41   745.4  894.35   765.6  906.11   775.6  910.71
   785.7  914.42   795.8  916.93   805.8  918.19   836.1  920.12   856.2  925.12
   936.8  948.37   946.9  949.09     967  945.43   977.1  946.11   987.2  948.37
#Mann= 3 , 0 , 0
    10.1      .1       0   425.7    .045       0   460.7      .1       0
Bank Sta=425.7,460.7
XS Rating Curve= 0 ,0
Exp/Cntr=0.3,0.1

Type RM Length L Ch R = 1 ,183061.4,1874.8,1889.8,1904.6
XS GIS Cut Line= 3
     1600002.865      358497.996     1601003.669      358868.104
     1602396.621      359008.973
#Sta/Elev= 30
    10.2  983.95    71.1  974.42   111.8  959.97   254.1  883.39   416.7  767.91
     437  760.96   480.5  756.89     498  756.07   515.5  757.51   589.4  766.68
   741.9  822.71   833.3  849.51  1036.6  880.84  1127.9  908.73  1188.8  917.07
  1259.8  933.02    1483 1007.95    1554 1016.07  1635.2 1016.14  1736.6 1038.88
  1868.5 1001.96  1959.8  981.78  2020.7   988.8  2071.4   987.9  2101.9  980.45
  2203.3  982.41  2264.2  967.25  2294.6  973.12  2335.2  967.23  2467.1  933.11
#Mann= 3 , 0 , 0
       0      .1       0   480.5    .045       0   515.5      .1       0
Bank Sta=480.5,515.5
XS Rating Curve= 0 ,0
Exp/Cntr=0.3,0.1

Type RM Length L Ch R = 1 ,181171.6,635.5,615.2,594.9
XS GIS Cut Line= 3
     1599270.938      358603.999     1599781.968       359163.37
     1600693.454       360014.78
#Sta/Elev= 30
    10.1  932.99    40.4  925.97    60.6   918.3   346.2  755.94   363.7   753.5
   381.2  755.82   414.2  758.87   505.1  757.63   626.3  761.25   646.5  763.67
   686.9  778.34   717.3   786.5   808.4  832.15   828.6  839.97   848.9  843.27
   879.3  840.65   909.8  834.31  1031.5  794.26  1051.7  794.22    1072  801.67
  1122.7  827.94  1183.6  851.73  1264.7   879.2  1335.7  899.38  1426.9  911.48
  1609.5  915.54  1822.4  930.04    1863  939.21  1954.2   971.5  2004.9  984.16
#Mann= 3 , 0 , 0
       0      .1       0   346.2    .045       0   381.2      .1       0
Bank Sta=346.2,381.2
XS Rating Curve= 0 ,0
Exp/Cntr=0.3,0.1

Type RM Length L Ch R = 1 ,180556.5,655.3,695.2,733.7
XS GIS Cut Line= 2
     1598963.023      359366.213     1599871.623      359568.124
#Sta/Elev= 30
    10.1  944.06    30.4  932.69    80.9  903.13   111.3  886.77   131.5   876.8
   182.1  854.61   374.3  768.41   384.4  765.39   394.6  763.82   538.9   752.1
   556.4  751.36   566.6  752.85   573.9  756.52   596.9  770.67     607  775.65
   617.1  779.32   627.3  782.28   637.4     788   647.5  796.45   657.6  803.33
   677.8  814.33   698.1  824.14   728.4  836.54   748.7  843.64   829.6  868.23
   849.8  875.07   890.3  889.97   900.4  892.22   910.5  892.71   930.8  891.54
#Mann= 3 , 0 , 0
       0      .1       0   538.9    .045       0   573.9      .1       0
Bank Sta=538.9,573.9
XS Rating Curve= 0 ,0
Exp/Cntr=0.3,0.1

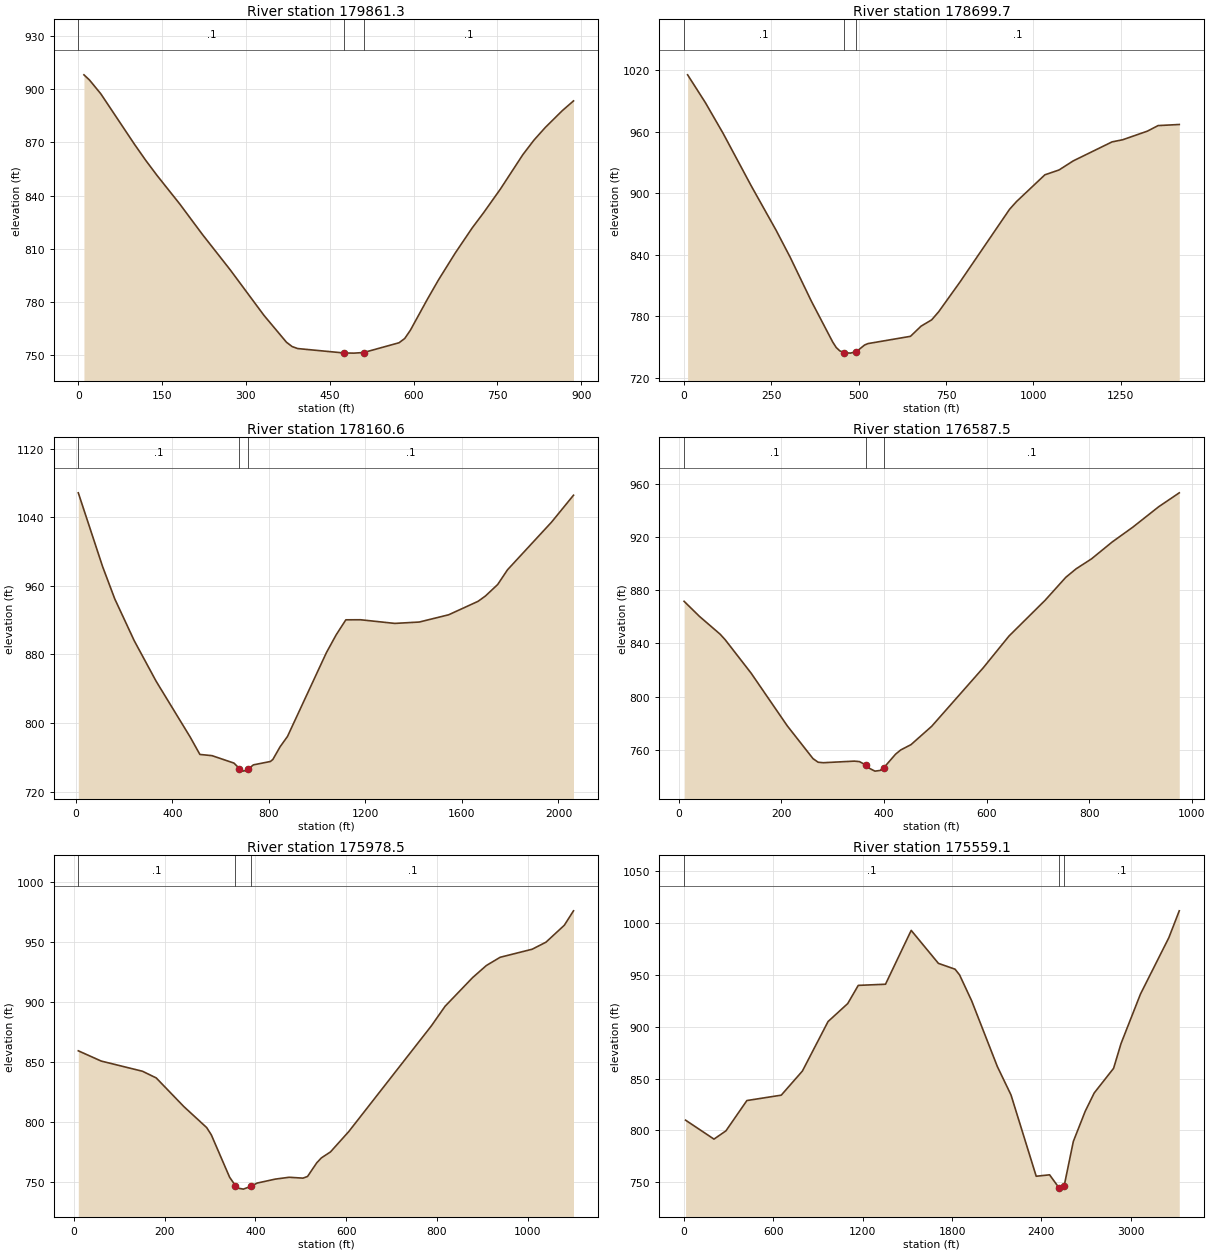
Type RM Length L Ch R = 1 ,179861.3,1160.3,1161.6,1164.2
XS GIS Cut Line= 2
     1598937.784      359628.697     1599291.129      360441.389
#Sta/Elev= 30
    10.1  908.02    20.1  905.07    40.3  897.32   100.7  868.83   120.8  859.81
     141  851.33   181.3   835.4   221.5  818.39   271.9  798.19   332.3  772.55
   372.6  757.41   382.7  754.99   392.7  753.87   475.9  751.37   493.4   751.3
   510.9  751.65     574  757.14   584.1  759.52   594.1   764.1   624.4  781.47
   644.5  792.49   674.7  807.73   704.9   821.8   725.1  830.27   755.3  843.66
   795.6  863.09   815.7  871.35   835.8   878.4     866   887.8   886.2  893.33
#Mann= 3 , 0 , 0
       0      .1       0   475.9    .045       0   510.9      .1       0
Bank Sta=475.9,510.9
XS Rating Curve= 0 ,0
Exp/Cntr=0.3,0.1

Type RM Length L Ch R = 1 ,178699.7,564.5,539.1,513.8
XS GIS Cut Line= 2
     1598313.744      359122.341     1598443.486       360534.23
#Sta/Elev= 30
    10.1 1015.32    60.8  988.31   111.4  958.47   192.4  906.99   263.3   863.9
   303.8  837.47   364.6  794.53   425.4  754.93   435.5  749.55   445.6  746.25
   458.5  744.56     476     744   493.5  745.46   516.5  751.85   526.6   753.3
   648.2  760.38   678.5  770.29   708.9  776.44   729.2  784.45   789.9  813.31
   931.7  884.13     952  891.83    1033  917.84  1073.5  922.56    1114  931.38
  1225.4  949.95  1255.8  952.02  1326.7  960.44  1357.1  965.83  1417.8   966.9
#Mann= 3 , 0 , 0
       0      .1       0   458.5    .045       0   493.5      .1       0
Bank Sta=458.5,493.5
XS Rating Curve= 0 ,0
Exp/Cntr=0.3,0.1

Type RM Length L Ch R = 1 ,178160.6,1558.2,1573.1,1588
XS GIS Cut Line= 3
     1597408.987      359321.215     1598195.761      360088.045
     1598519.328      360995.788
#Sta/Elev= 30
    10.1 1068.38   110.9  982.33   161.3  944.68   241.9  896.01   332.6  848.78
   473.7  783.73     514  763.43   564.4  762.01   655.2  753.34     678  746.94
   695.5  743.98     713  746.21   735.8  751.28   806.4  755.24   816.4  757.58
   846.7  772.52   876.9  784.34  1038.2  882.03  1078.5  902.75  1118.9  920.36
  1179.8  920.42  1321.8  916.17  1423.3  917.77    1545  926.23  1666.7  941.89
  1697.2  948.08  1747.9  961.44  1788.5  978.57    1971 1034.12  2062.3 1065.59
#Mann= 3 , 0 , 0
    10.1      .1       0     678    .045       0     713      .1       0
Bank Sta=678,713
XS Rating Curve= 0 ,0
Exp/Cntr=0.3,0.1

Type RM Length L Ch R = 1 ,176587.5,581.8,609,636.1
XS GIS Cut Line= 2
      1597383.07      360633.205     1597786.892      361521.613
#Sta/Elev= 30
    10.1  871.55    40.2  860.18    80.5  846.81    90.5  842.56   140.8  817.59
   211.3  778.02   261.6  753.33   271.6  750.64   281.7  750.28   342.1  751.47
   352.1  751.11   364.8  748.54   372.2  745.94   382.3  743.96   392.4  744.46
   399.8  746.58   422.5  756.66   432.6  759.86   452.7  763.87     493  777.63
   593.6   821.6   643.9  845.48   714.3  872.34   754.5  889.53   774.7  895.95
   804.8  903.45   845.1  916.12   885.3  927.24   935.6  942.54   975.9  953.04
#Mann= 3 , 0 , 0
    10.1      .1       0   364.8    .045       0   399.8      .1       0
Bank Sta=364.8,399.8
XS Rating Curve= 0 ,0
Exp/Cntr=0.3,0.1

Type RM Length L Ch R = 1 ,175978.5,418.7,419.5,420.2
XS GIS Cut Line= 2
     1597090.299      360623.109     1596676.381       361642.76
#Sta/Elev= 30
    10.1  859.24    60.6  850.68   151.4   842.2   181.7  836.63   242.3  812.82
   292.8  795.23   302.9  789.26   343.3  753.84   356.1  746.84   363.5  744.65
   373.6  743.94   391.1  746.42   403.8  748.98   444.2  752.31   474.5  753.82
   504.8   753.1   514.9  754.51   535.1  765.84   545.2  769.93   565.4  774.96
   605.8  791.99   787.5  880.01   817.8  896.39   878.3  920.24   908.6  930.33
   938.9  937.18  1009.6  943.93  1039.9  949.79  1080.3   963.9  1100.5  975.92
#Mann= 3 , 0 , 0
    10.1      .1       0   356.1    .045       0   391.1      .1       0
Bank Sta=356.1,391.1
XS Rating Curve= 0 ,0
Exp/Cntr=0.3,0.1

Type RM Length L Ch R = 1 ,175559.1,1536.8,1484.7,1423.1
XS GIS Cut Line= 5
     1596549.883      358360.471     1596494.547      359061.441
     1596705.571      360539.354     1596490.732      360989.492
     1596560.282      361617.521
#Sta/Elev= 30
      10  809.93   200.9  791.65   281.3  799.64   421.9  828.85   652.9  834.05
   794.6  857.25   967.2  905.05  1099.2  922.37  1170.3  939.94  1353.1  941.03
  1525.8  992.97  1708.6  961.17  1820.3  955.55  1850.8  950.04    1932  925.02
  2104.7   861.6  2196.1  834.33  2365.6  755.84  2455.4  757.22  2517.7  744.91
  2535.2  743.42  2552.7  746.06    2615  789.42  2694.8   818.5    2755  836.11
  2885.4  859.93  2935.5  883.87  3065.9  931.53  3256.5   985.9  3326.7 1011.84
#Mann= 3 , 0 , 0
       0      .1       0  2517.7    .045       0  2552.7      .1       0
Bank Sta=2517.7,2552.7
XS Rating Curve= 0 ,0
Exp/Cntr=0.3,0.1

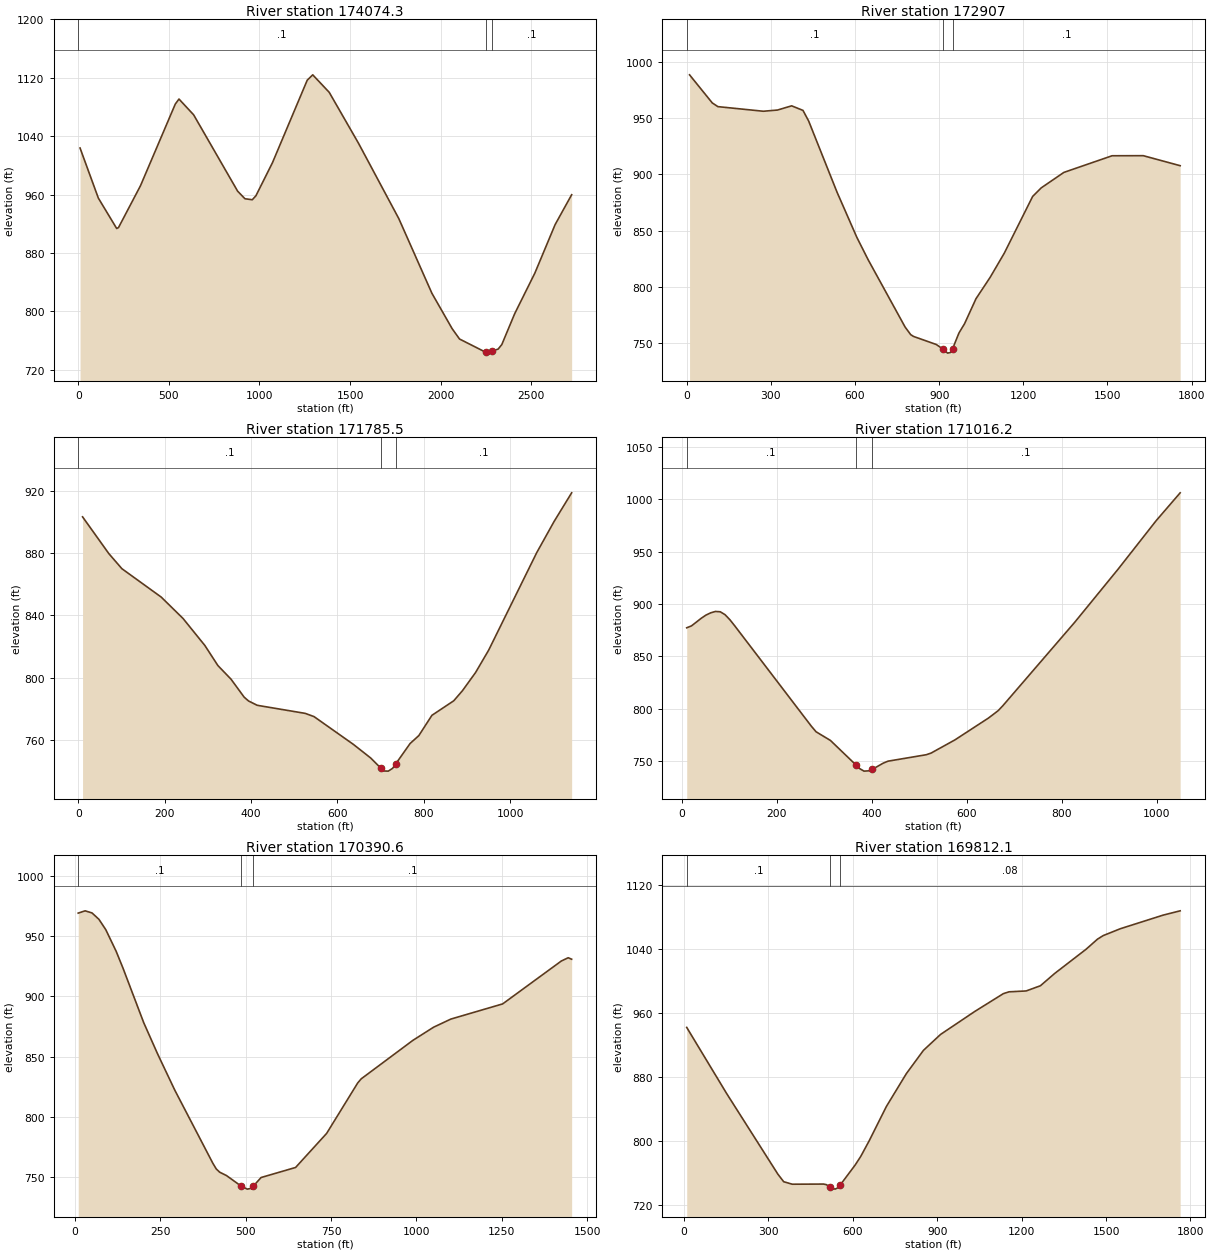
Type RM Length L Ch R = 1 ,174074.3,1180.7,1167.4,1154
XS GIS Cut Line= 3
     1594943.195      359436.447     1595677.159       361046.49
     1596479.518      361561.995
#Sta/Elev= 30
    10.1 1023.92   111.2  955.26   212.3  913.67   222.4  914.94   343.8  972.32
   535.9 1084.19   556.1 1090.98     637 1069.37   879.7  964.83   920.1  954.42
   960.6  953.03   980.8  958.51  1071.8 1003.67  1263.9 1116.81  1294.2 1124.15
  1385.2 1100.19    1547 1030.35  1769.4  927.11  1952.1  824.82  2063.7  776.38
  2104.3  762.28  2249.1   744.1  2266.6  742.94  2284.1  745.82  2317.3  748.43
  2337.6  754.67  2408.6  796.88  2520.2  852.64  2631.8  918.97  2723.1   959.9
#Mann= 3 , 0 , 0
       0      .1       0  2249.1    .045       0  2284.1      .1       0
Bank Sta=2249.1,2284.1
XS Rating Curve= 0 ,0
Exp/Cntr=0.3,0.1

Type RM Length L Ch R = 1 ,172907  ,1109,1121.4,1133.8
XS GIS Cut Line= 2
     1594722.892       362097.06     1596449.231       362435.26
#Sta/Elev= 30
    10.1   988.5      91  963.54   111.2  960.22     273  956.12   323.5  957.18
   374.1  960.93   414.5  956.87   434.7  947.45   535.8  884.22   606.6  843.96
     647  824.02   778.5  764.29   798.7  757.45   808.8  755.88   889.7  748.74
   912.6  744.83   930.1  741.06   940.2  741.63   947.6  744.79   970.6  758.96
   990.8  767.33  1031.2   789.4  1081.8  808.46  1132.3  829.99  1233.4   880.4
  1263.8  887.97  1344.6  901.74  1516.5  916.54  1627.7  916.61  1759.2  907.71
#Mann= 3 , 0 , 0
       0      .1       0   912.6    .045       0   947.6      .1       0
Bank Sta=912.6,947.6
XS Rating Curve= 0 ,0
Exp/Cntr=0.3,0.1

Type RM Length L Ch R = 1 ,171785.5,774.9,769.3,763.7
XS GIS Cut Line= 2
     1594924.803      362975.372      1595883.88      363596.249
#Sta/Elev= 30
    10.1  903.24    70.8  879.71   101.1  870.01   192.1  851.81   242.7  838.08
   293.2  820.78   323.5  807.86   353.9  799.12   384.2  787.63   394.3  785.19
   414.5   782.4   525.8  777.21     546  775.15     637  757.37   677.4  748.56
   700.4   742.2   707.7  740.29   717.9  740.19     728     742   735.4  744.92
   768.4  757.88   788.6  762.96     819  775.99   869.5  785.29   889.7  791.78
   920.1  803.45   950.4  817.79  1061.6  880.28  1102.1   900.4  1142.5  918.65
#Mann= 3 , 0 , 0
       0      .1       0   700.4    .045       0   735.4      .1       0
Bank Sta=700.4,735.4
XS Rating Curve= 0 ,0
Exp/Cntr=0.3,0.1

Type RM Length L Ch R = 1 ,171016.2,631.1,625.6,620.1
XS GIS Cut Line= 2
      1594637.08      363767.873     1595601.205      364181.791
#Sta/Elev= 30
    10.1  877.22    20.2  879.06    40.4  886.22    50.4  889.31    60.5  891.52
    70.6  892.84    80.7  892.53    90.8  889.76   100.9  884.98     111  879.23
   272.4  783.21   282.5  777.79   312.7  769.53   365.9  746.33   373.3  742.84
   383.4  740.17   393.5  740.45   400.9  741.87   423.7  747.74   433.8  749.67
   514.5  755.85   524.6   757.4   575.1  770.09   645.7  790.97   665.9  797.96
   675.9  802.75   827.3  882.57   918.1  933.06   998.8  979.72  1049.2 1006.27
#Mann= 3 , 0 , 0
    10.1      .1       0   365.9    .045       0   400.9      .1       0
Bank Sta=365.9,400.9
XS Rating Curve= 0 ,0
Exp/Cntr=0.3,0.1

Type RM Length L Ch R = 1 ,170390.6,552.5,578.5,604.5
XS GIS Cut Line= 2
     1594359.452      364408.941     1595772.829      364752.189
#Sta/Elev= 30
    10.1  969.16    30.3  971.06    50.5  969.31    70.7  964.03    90.9  955.39
   121.2  937.46   141.4  923.36     202  878.16   242.4   852.4   292.9  822.23
     404  761.72   414.1  756.93   424.2  754.21   444.4  751.36   487.5  742.55
     505  740.15   515.1  740.72   522.5  742.58   545.4  749.78   646.4  758.12
   737.3  786.39   828.2  828.22   838.3  831.61   989.8  863.59  1050.4   874.5
  1100.9  881.24  1252.5  893.83  1424.2   929.4  1444.4  932.14  1454.5   930.9
#Mann= 3 , 0 , 0
    10.1      .1       0   487.5    .045       0   522.5      .1       0
Bank Sta=487.5,522.5
XS Rating Curve= 0 ,0
Exp/Cntr=0.3,0.1

Type RM Length L Ch R = 1 ,169812.1,610.7,629.6,648.4
XS GIS Cut Line= 2
     1594339.261      364580.565     1595242.813      366094.897
#Sta/Elev= 30
    10.1   942.4     152  859.69   334.4  758.65   354.7  749.39   385.1  746.28
   496.6  746.46   506.7  745.68   519.6  742.32   537.1  740.13   547.3  741.81
   554.6  744.88   608.1  770.05   628.3  780.95   658.7  800.78   719.6  843.55
   790.5  884.59   851.3  913.72   912.1  933.64  1033.7  962.38  1135.1  984.64
  1155.3  986.93  1216.1  988.01  1266.8  994.51  1317.5 1009.89    1429 1040.14
  1469.5 1052.77  1489.8 1057.23  1550.6 1065.83  1702.6 1082.83  1763.4 1088.24
#Mann= 3 , 0 , 0
    10.1      .1       0   519.6    .045       0   554.6     .08       0
Bank Sta=519.6,554.6
XS Rating Curve= 0 ,0
Exp/Cntr=0.3,0.1

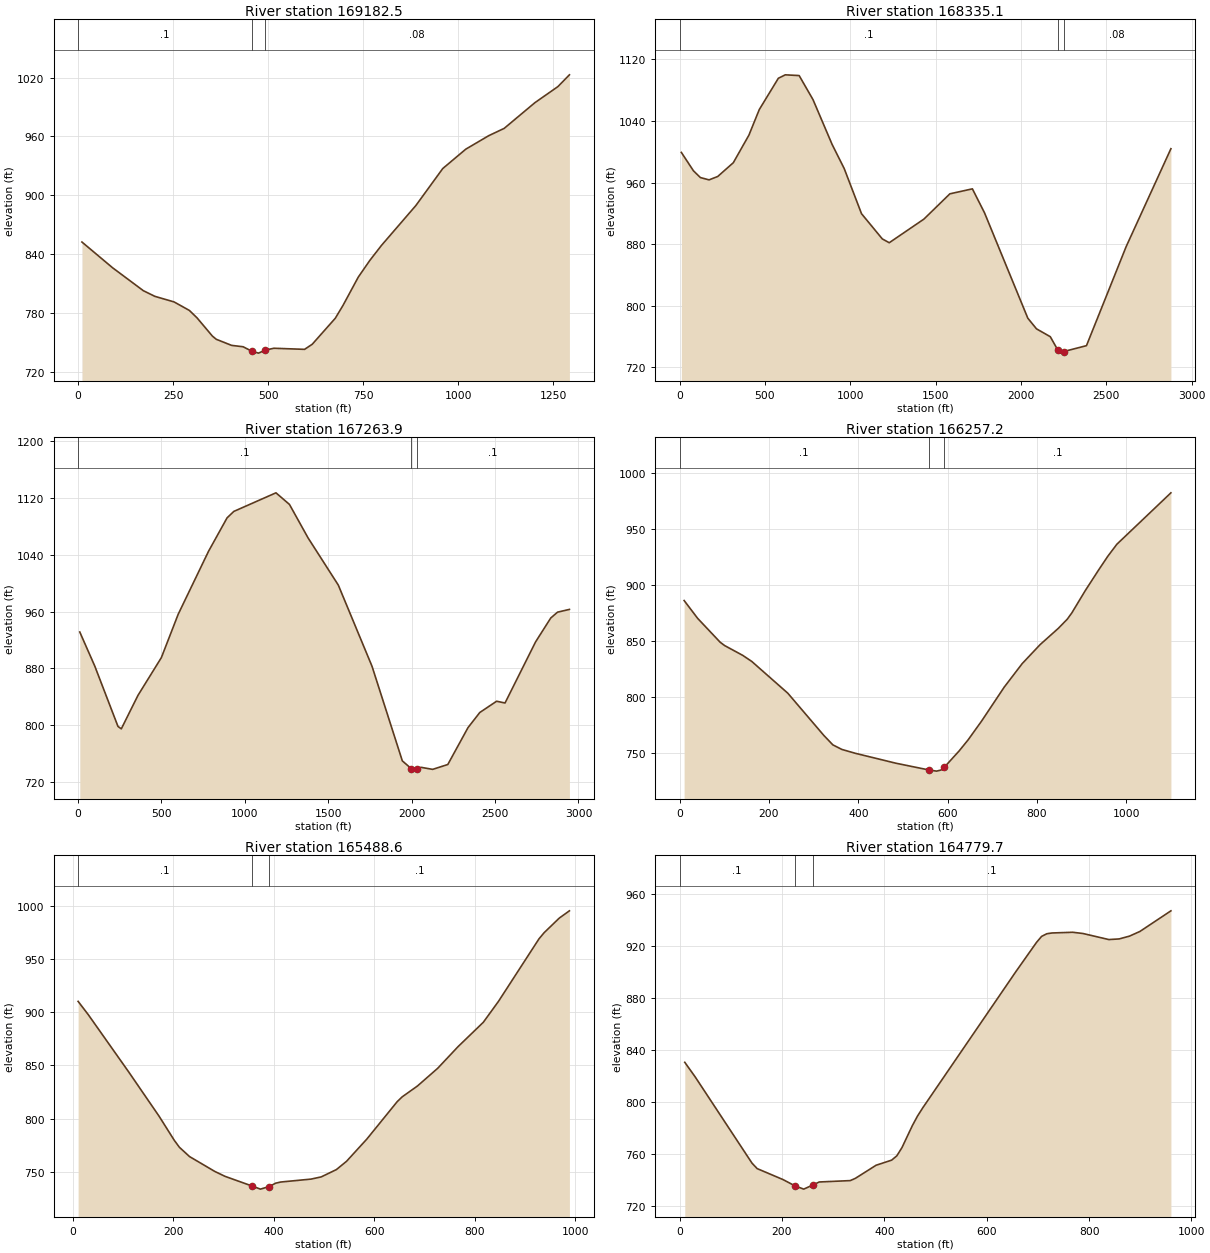
Type RM Length L Ch R = 1 ,169182.5,845.7,847.5,849.2
XS GIS Cut Line= 2
     1594006.108       364590.66      1593955.63      365882.891
#Sta/Elev= 30
    10.1  852.51    90.9  826.28   171.8  802.96   202.1  797.22   252.6  791.55
     293  782.85   313.2  775.26   353.6  756.71   363.7  753.51   404.1   747.3
   434.4   745.9   457.4  741.35   474.9  739.42   492.4  742.49   515.3  744.38
   596.1  743.27   616.3  748.46   676.9   774.9   697.1  787.89   737.5  816.83
   767.8  833.77   798.2  848.94   889.1  889.71   959.8  927.32  1020.4  947.04
    1081  960.81  1121.5  968.21  1202.3  994.36  1262.9 1010.74  1293.2 1022.73
#Mann= 3 , 0 , 0
       0      .1       0   457.4    .045       0   492.4     .08       0
Bank Sta=457.4,492.4
XS Rating Curve= 0 ,0
Exp/Cntr=0.3,0.1

Type RM Length L Ch R = 1 ,168335.1,1122.9,1071.2,1019.6
XS GIS Cut Line= 3
     1592223.195      362937.244     1593163.917      364816.006
     1593092.461       365590.12
#Sta/Elev= 30
    10.2  999.14    81.2  975.22   121.8  966.46   172.6  963.45   223.3  967.85
   314.7  985.74     406 1021.51   466.9 1054.81   578.6 1095.41   619.2 1099.87
   700.4 1098.91   781.6 1067.65   893.2 1009.64   964.3   978.2  1065.8  919.52
  1187.6  886.79  1228.2  881.83  1431.2  912.48  1583.5  945.34  1715.4   951.8
  1786.5  920.63  2040.2  783.78    2091  769.99  2171.8  759.79  2214.9  742.84
  2232.4  738.46  2249.9  740.48  2383.8  748.17    2616  876.64  2878.5 1003.92
#Mann= 3 , 0 , 0
       0      .1       0  2214.9    .045       0  2249.9     .08       0
Bank Sta=2214.9,2249.9
XS Rating Curve= 0 ,0
Exp/Cntr=0.3,0.1

Type RM Length L Ch R = 1 ,167263.9,1018.2,1006.7,995.2
XS GIS Cut Line= 5
       1590582.9      364109.688     1590943.273      364341.361
     1592135.797      365139.671     1592829.976      365196.394
     1593006.648      365539.642
#Sta/Elev= 30
      10  931.25    99.6   883.6   239.1  798.61     259  795.18   358.7  842.12
   499.2  895.26   600.2  956.18   782.1 1044.64   893.3 1091.61   933.7 1100.66
  1186.4 1126.77  1267.2 1110.51  1378.4 1063.65  1560.3  997.12  1762.4  883.09
  1944.2  750.15  1997.4  739.45  2014.9   735.8  2032.4  738.14  2055.3  741.19
  2125.9  738.27  2216.8   745.1  2337.9   796.9  2408.6  818.16  2509.5  833.99
    2560  831.53  2742.8  917.23  2834.3  950.97  2874.9  959.13    2946  963.01
#Mann= 3 , 0 , 0
       0      .1       0  1997.4    .045       0  2032.4      .1       0
Bank Sta=1997.4,2032.4
XS Rating Curve= 0 ,0
Exp/Cntr=0.3,0.1

Type RM Length L Ch R = 1 ,166257.2,777.2,768.6,760
XS GIS Cut Line= 2
     1592138.431      366150.423     1593198.464      365857.652
#Sta/Elev= 30
    10.1  886.14    40.4  870.17    90.8  848.83   100.9  845.81   141.2  837.09
   161.4  831.68   242.1  803.27   322.9  765.44     343  757.04   363.2  752.94
   393.5  749.47   484.3   740.6   557.6  734.62   575.1  733.54   585.2  734.53
   592.6  737.06   625.5  751.52   645.7  761.46     676  778.35   726.4  808.56
   766.8  829.69   807.1  846.76   847.5  861.17   867.7  869.43   877.8  874.99
     908  894.99   938.3   913.7   958.5  925.74   978.7  936.45  1099.7  982.45
#Mann= 3 , 0 , 0
       0      .1       0   557.6    .045       0   592.6      .1       0
Bank Sta=557.6,592.6
XS Rating Curve= 0 ,0
Exp/Cntr=0.3,0.1

Type RM Length L Ch R = 1 ,165488.6,714.5,708.9,703.3
XS GIS Cut Line= 2
     1592446.345      366922.733     1593299.419      366423.003
#Sta/Elev= 30
    10.1  910.27    30.3  897.79     111  843.75   171.5  802.09   201.8  779.38
   211.9  772.89     232  764.18   282.5  750.14   302.7  745.56   355.8  736.57
   373.3  733.52   390.8  735.95   403.5   739.1   413.6   740.2   474.2  742.96
   494.3  745.02   524.6  751.93   544.8  759.73   585.1  780.57   645.7  815.88
   655.7  820.41     686  830.59   726.4  847.29   766.7  867.55   817.2  890.57
   847.4  910.25   928.1  969.11   938.2  974.84   968.5  988.65   988.7  995.49
#Mann= 3 , 0 , 0
    10.1      .1       0   355.8    .045       0   390.8      .1       0
Bank Sta=355.8,390.8
XS Rating Curve= 0 ,0
Exp/Cntr=0.3,0.1

Type RM Length L Ch R = 1 ,164779.7,730.2,765.9,797
XS GIS Cut Line= 2
     1593036.935      367402.271     1593768.863      366781.395
#Sta/Elev= 30
    10.1  830.66    30.3  819.51   141.4  753.09   151.5  748.87   202.1  740.41
     225  735.65   242.5  733.07     260  736.19   272.8  738.57   333.4  739.63
   343.5   741.4   383.9  751.46   414.2  755.37   424.3  758.68   434.4  765.03
   454.6  781.86   464.7  789.25   474.8  795.51   656.7  900.32   697.1  922.88
   707.2  927.57   717.3  929.59   727.4  930.19   767.8  930.74     788  929.79
   838.6  925.12   858.8  925.62     879  927.79   899.2  931.36   959.8  947.24
#Mann= 3 , 0 , 0
       0      .1       0     225    .045       0     260      .1       0
Bank Sta=225,260
XS Rating Curve= 0 ,0
Exp/Cntr=0.3,0.1

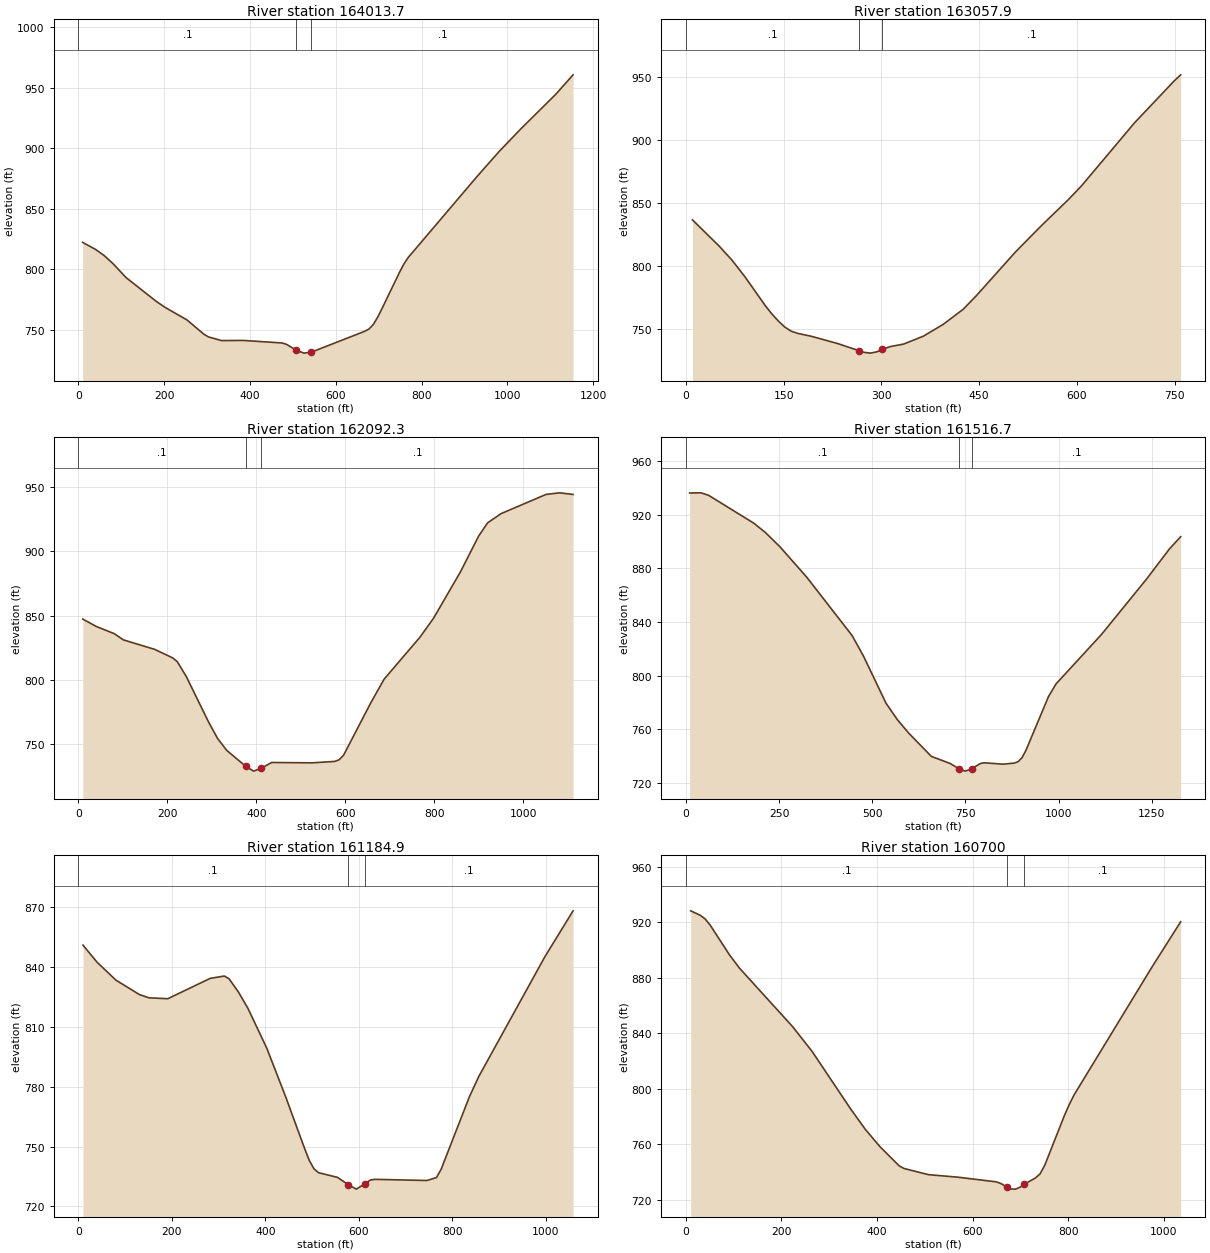
Type RM Length L Ch R = 1 ,164013.7,903.2,955.8,1013.2
XS GIS Cut Line= 2
     1593329.706      367614.278     1594470.503      367780.854
#Sta/Elev= 30
    10.1  822.31    40.5   816.4    60.7   811.3    80.9  804.71   111.2  793.22
     182  773.45   202.3  768.53   252.8  758.31   293.3  746.22   303.4  744.16
   333.7  741.13   384.3  741.24   475.3  739.14   485.4  737.96   508.4  733.09
   525.9  730.75   543.4  731.59   667.5   748.8   677.6  750.73   687.7  754.52
   697.8  760.56   707.9  767.69   748.4  797.45   758.5  804.26   768.6  809.71
   930.4  877.22     981  897.51  1031.5  916.18  1112.4  944.59  1152.9  960.74
#Mann= 3 , 0 , 0
       0      .1       0   508.4    .045       0   543.4      .1       0
Bank Sta=508.4,543.4
XS Rating Curve= 0 ,0
Exp/Cntr=0.3,0.1

Type RM Length L Ch R = 1 ,163057.9,998.4,965.6,932.7
XS GIS Cut Line= 2
     1593233.798      367639.517     1592920.836      368331.062
#Sta/Elev= 30
    10.1  836.67    50.6  816.07    70.8  804.63    91.1  791.08   121.5  768.68
   131.6  762.06   141.7  756.32   151.8  751.44   161.9  748.07   172.1  746.38
   192.3  744.15   232.8  738.36   265.9  732.64   273.3  731.37   283.4  730.73
   293.5  731.84   300.9  733.64   313.7  735.94     334  737.92   364.4  744.22
   394.7  753.58   425.1  765.46   445.3   776.2     506  811.37   546.5  832.64
     587  852.89   607.3  863.94   688.2  913.79   748.9  947.05   759.1  952.02
#Mann= 3 , 0 , 0
       0      .1       0   265.9    .045       0   300.9      .1       0
Bank Sta=265.9,300.9
XS Rating Curve= 0 ,0
Exp/Cntr=0.3,0.1

Type RM Length L Ch R = 1 ,162092.3,599.4,575.6,551.9
XS GIS Cut Line= 2
     1592057.667      367321.507     1592653.304      368260.393
#Sta/Elev= 30
    10.1  847.32    40.4  841.59    80.9  835.97   101.1  831.19   171.8  823.78
   212.3  817.15   222.4  814.27   242.6  802.79   293.1  767.21   313.3  754.51
   333.6   745.4   376.7  732.91   394.2  729.28   411.7  731.59   434.6  735.99
   525.6  735.71   576.2  736.82   586.3   738.1   596.4  741.77     657  782.08
   687.3  800.66   768.2  833.39   798.5  848.03   859.2  884.18   899.6  911.66
   919.8  921.97   950.2  929.16  1051.2  944.06  1081.6   945.3  1111.9  944.05
#Mann= 3 , 0 , 0
       0      .1       0   376.7    .045       0   411.7      .1       0
Bank Sta=376.7,411.7
XS Rating Curve= 0 ,0
Exp/Cntr=0.3,0.1

Type RM Length L Ch R = 1 ,161516.7,346.9,331.8,316.7
XS GIS Cut Line= 2
     1591260.118       367927.24     1592537.205       368290.68
#Sta/Elev= 30
    10.1  936.07    40.5   936.2    60.8  934.38   182.4  913.54   212.9  906.74
   253.4  895.69   324.3  873.32     446  829.84   476.4  814.64   537.2  779.31
   567.6   767.1     598  757.08   658.8  739.74   709.5  734.43   732.6  730.54
   750.1  728.76   767.6  730.66   790.6  734.47   800.7  734.96   851.4  733.94
   881.8  734.76     892  735.91   902.1  738.83   912.2     744     973  784.28
   993.3  793.77  1114.9  830.51  1236.6  872.04  1297.4   894.3  1327.8  903.51
#Mann= 3 , 0 , 0
       0      .1       0   732.6    .045       0   767.6      .1       0
Bank Sta=732.6,767.6
XS Rating Curve= 0 ,0
Exp/Cntr=0.3,0.1

Type RM Length L Ch R = 1 ,161184.9,469.7,484.9,500.1
XS GIS Cut Line= 2
     1591462.029      368553.164     1592501.871      368356.301
#Sta/Elev= 30
    10.1  851.05    40.3  842.44    80.6  833.47     131  826.22   151.2  824.61
   191.5  824.16   282.2  834.37   312.5  835.55   322.5  834.16   342.7  827.47
   362.9  819.32   403.2  799.35   443.5  775.01   483.8  749.19   493.9  743.13
     504  738.83     514  736.85   554.4  734.53   577.2  730.88   594.7  728.62
   612.2  731.16   624.9  733.22     635  733.53   745.9  732.95     766  734.42
   776.1  738.55   836.6  774.98   856.7  785.16   997.8  845.13  1058.3  868.26
#Mann= 3 , 0 , 0
       0      .1       0   577.2    .045       0   612.2      .1       0
Bank Sta=577.2,612.2
XS Rating Curve= 0 ,0
Exp/Cntr=0.3,0.1

Type RM Length L Ch R = 1 ,160700  ,592.8,571.4,550.1
XS GIS Cut Line= 2
     1591507.459      368694.502     1592501.871      368982.225
#Sta/Elev= 30
    10.1  928.33    30.4  925.05    40.6  922.37    50.7  918.06    91.3  896.56
   111.6   887.2   223.3  844.79   263.9  827.01   345.1  785.24   375.5  770.69
     406  758.24   446.6  744.29   456.7  742.47   507.5  738.05   568.3  736.25
   649.5  732.86   659.7  731.54   672.6  728.86     680  727.69   690.1  727.61
   700.3  729.21   707.6  731.08   730.7  735.54   740.9  738.53     751  744.94
   791.6   780.4   801.8  788.43   811.9   795.4   974.3   887.3  1035.2  920.45
#Mann= 3 , 0 , 0
       0      .1       0   672.6    .045       0   707.6      .1       0
Bank Sta=672.6,707.6
XS Rating Curve= 0 ,0
Exp/Cntr=0.3,0.1

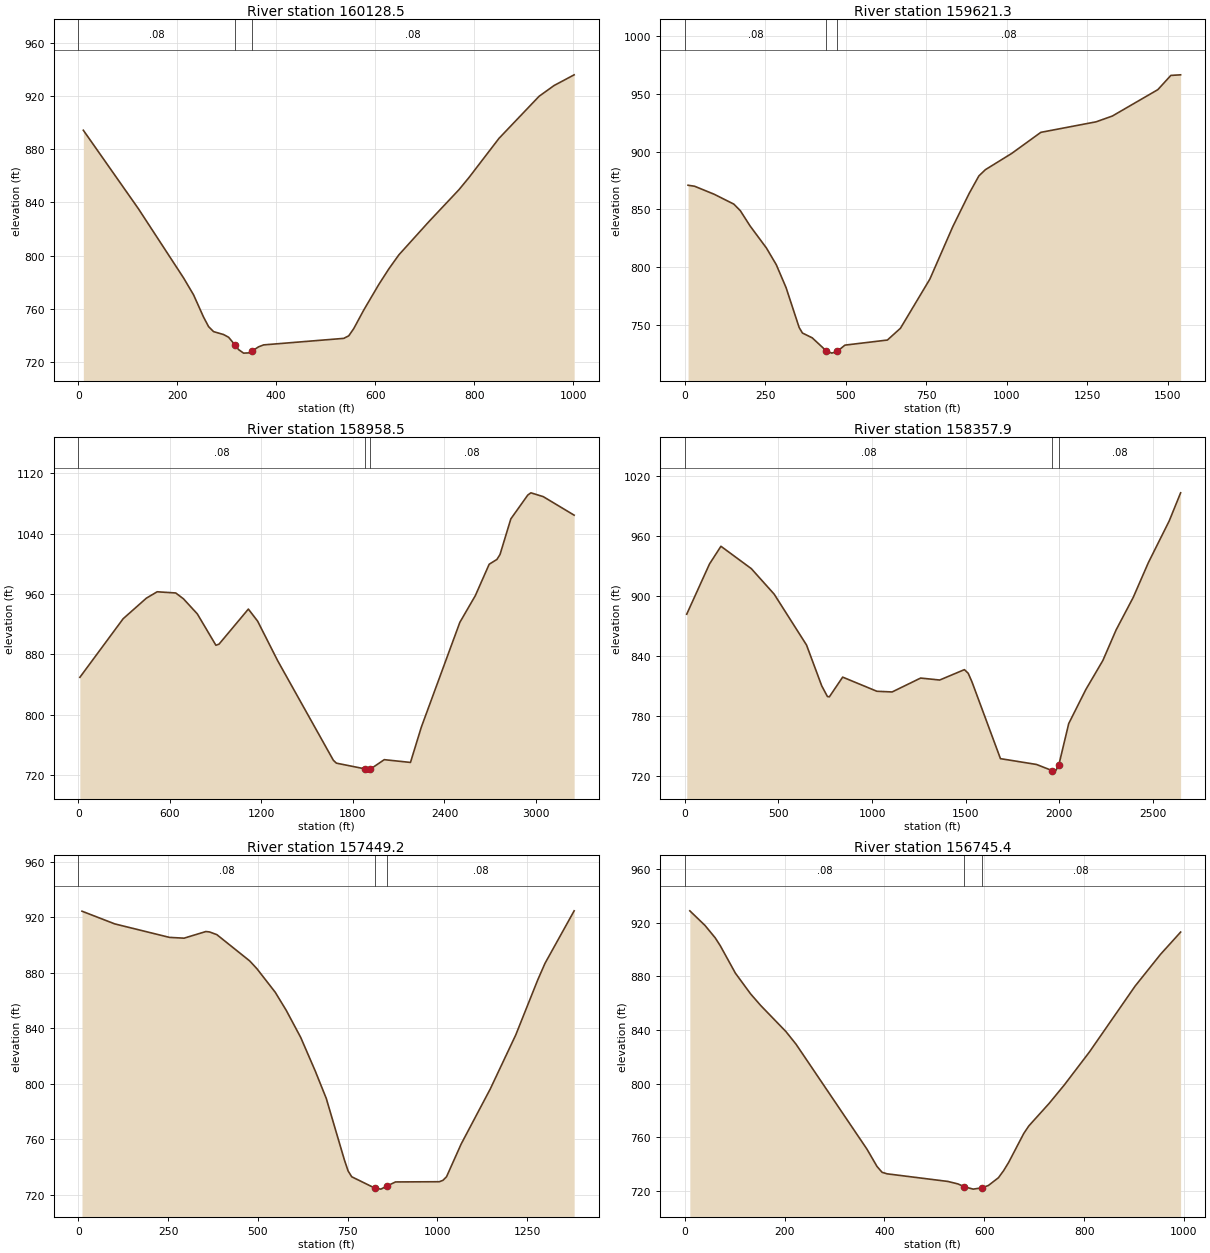
Type RM Length L Ch R = 1 ,160128.5,517.1,507.3,497.4
XS GIS Cut Line= 2
      1591573.08      369481.955     1592506.919      369118.515
#Sta/Elev= 30
    10.1  894.21   121.5  835.24   212.6  783.39   232.8  770.71     253     754
   263.2   746.8   273.3  743.03   293.5  740.82   303.7  738.79   316.5  733.07
   323.9  729.52     334  726.87   344.1  727.04   351.5  728.53   364.4  731.61
   374.5  733.05   536.5  737.95   546.6  739.88   556.7  745.32   576.9  759.25
   607.3  778.42   627.6  790.14   647.8  800.64   708.5  825.59   769.3  849.58
   789.5  858.69   850.2  888.12   931.2   919.7   961.6  927.81  1002.1  935.82
#Mann= 3 , 0 , 0
       0     .08       0   316.5    .045       0   351.5     .08       0
Bank Sta=316.5,351.5
XS Rating Curve= 0 ,0
Exp/Cntr=0.3,0.1

Type RM Length L Ch R = 1 ,159621.3,628.4,662.7,697
XS GIS Cut Line= 3
     1591921.377       369946.35     1592687.608      369280.823
     1593050.817      368901.813
#Sta/Elev= 30
    10.1   870.9    30.4  870.04    91.3   863.1   152.2  854.59   172.5  848.86
     203  835.59   253.7  816.52   284.2  802.12   314.6  782.27   355.2  747.81
   365.4  743.05   395.8  738.89   439.2  727.67   456.7  725.66   474.2  727.31
   497.3  732.57   629.2  736.98   669.8  747.19   761.2  789.74   832.2  835.01
     883  863.71   913.4  878.98   933.7  884.39  1014.9  898.35  1105.8  916.66
  1277.4  925.76  1327.9  930.77  1469.2  953.61  1509.6  965.92  1539.9  966.42
#Mann= 3 , 0 , 0
       0     .08       0   439.2    .045       0   474.2     .08       0
Bank Sta=439.2,474.2
XS Rating Curve= 0 ,0
Exp/Cntr=0.3,0.1

Type RM Length L Ch R = 1 ,158958.5,612.3,600.6,589.5
XS GIS Cut Line= 4
     1590526.462      369987.531     1592106.577      370029.969
     1592908.821       370338.22     1593718.484      370316.631
#Sta/Elev= 30
    10.1   849.6   293.8  927.29   445.8  954.52   516.8  963.03   638.4  961.44
     689  953.72   780.2  933.63   901.8  892.11   922.1  893.56  1114.6  940.08
  1175.4  924.04  1307.1  871.46  1671.7   739.6  1691.9  735.78  1876.6   728.3
  1894.1  725.22  1911.6  727.52  2005.3  740.42  2177.2  736.74    2248  783.37
  2500.9  922.53  2602.1  957.83  2693.2  999.57  2743.8 1005.91  2764.1 1012.45
    2835 1059.65  2946.3  1091.3  2966.6 1094.23  3047.6 1089.17  3250.1  1064.6
#Mann= 3 , 0 , 0
       0     .08       0  1876.6    .045       0  1911.6     .08       0
Bank Sta=1876.6,1911.6
XS Rating Curve= 0 ,0
Exp/Cntr=0.3,0.1

Type RM Length L Ch R = 1 ,158357.9,931.2,908.8,885.8
XS GIS Cut Line= 3
     1590465.119       370846.34     1591985.717      370645.591
     1593099.401      370676.385
#Sta/Elev= 30
    10.2  881.44     132  931.72     193  949.41   355.5  926.99   477.4   901.5
   650.1  850.64   731.3  809.81   761.8  799.13     772  798.83   843.1  818.54
  1025.9  804.38  1107.2   803.7  1259.5   817.6  1361.1  815.63  1493.2  826.01
  1513.5   822.4  1533.8  813.71  1685.7     737  1878.2  731.19  1961.9  725.04
  1979.4  724.52  1996.9  730.24  2050.3  772.08  2141.5  806.07  2232.6  835.16
  2303.5   865.8  2394.7  898.24  2475.7  933.05  2587.1  974.81  2647.9 1002.86
#Mann= 3 , 0 , 0
       0     .08       0  1961.9    .045       0  1996.9     .08       0
Bank Sta=1961.9,1996.9
XS Rating Curve= 0 ,0
Exp/Cntr=0.3,0.1

Type RM Length L Ch R = 1 ,157449.2,717,703.7,690.6
XS GIS Cut Line= 2
     1591900.555      371868.921     1592966.897       370991.87
#Sta/Elev= 30
    10.2  924.29   101.5  915.15   253.8  905.44   294.4  904.88   355.3  909.66
   365.5  909.35   385.8   907.4   477.2  888.51   497.5  882.84   548.2  865.99
   578.7  853.04   619.3  833.42   659.9  809.16   690.3  789.62   741.1   745.1
   751.3  737.29   761.4  733.13   825.1  725.06   842.6  724.25   860.1  726.57
   883.2  729.42  1005.1  729.58  1015.2  730.56  1025.4  733.21    1066  756.69
  1147.2   796.4  1218.3  835.36  1279.2  874.78  1299.5  886.76  1380.7  924.56
#Mann= 3 , 0 , 0
       0     .08       0   825.1    .045       0   860.1     .08       0
Bank Sta=825.1,860.1
XS Rating Curve= 0 ,0
Exp/Cntr=0.3,0.1

Type RM Length L Ch R = 1 ,156745.4,696.8,678.3,659.8
XS GIS Cut Line= 2
     1592582.004      372304.292     1593194.047      371521.887
#Sta/Elev= 30
    10.1  928.95    40.5  918.03    60.8  908.84      71  902.95   101.4  882.39
   131.8  866.96     152   858.3   202.7  838.76     223   829.3   364.9  751.04
   385.2  738.03   395.3   733.7   405.5  732.57   527.1  726.89   547.4  725.02
   560.3  722.89   577.8  721.15   595.3  722.12   608.2  723.86   628.4  729.67
   638.6  734.86   648.7     741   679.1  762.69   689.3  768.36   729.8  785.09
   760.2  798.85   810.9  823.67   902.1  872.69   952.8  896.33   993.4  913.07
#Mann= 3 , 0 , 0
       0     .08       0   560.3    .045       0   595.3     .08       0
Bank Sta=560.3,595.3
XS Rating Curve= 0 ,0
Exp/Cntr=0.3,0.1