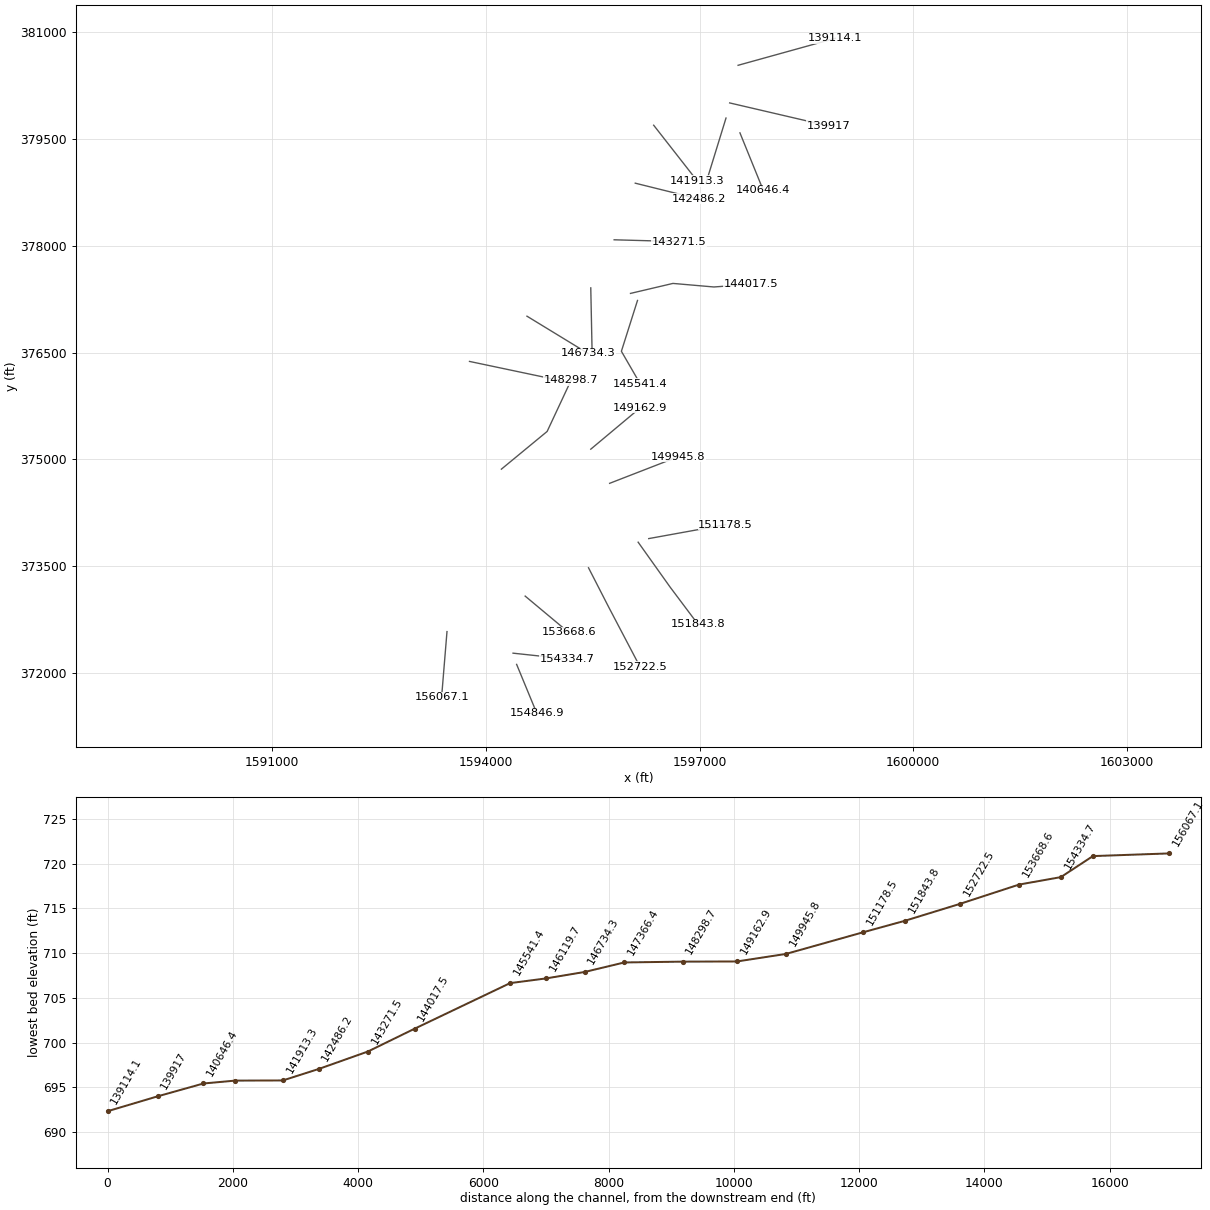
HEC-RAS study EFTWELVECR.prj: EFTWELVECR

--- EFTWELVECR.g01 (geometry) --- (continued)

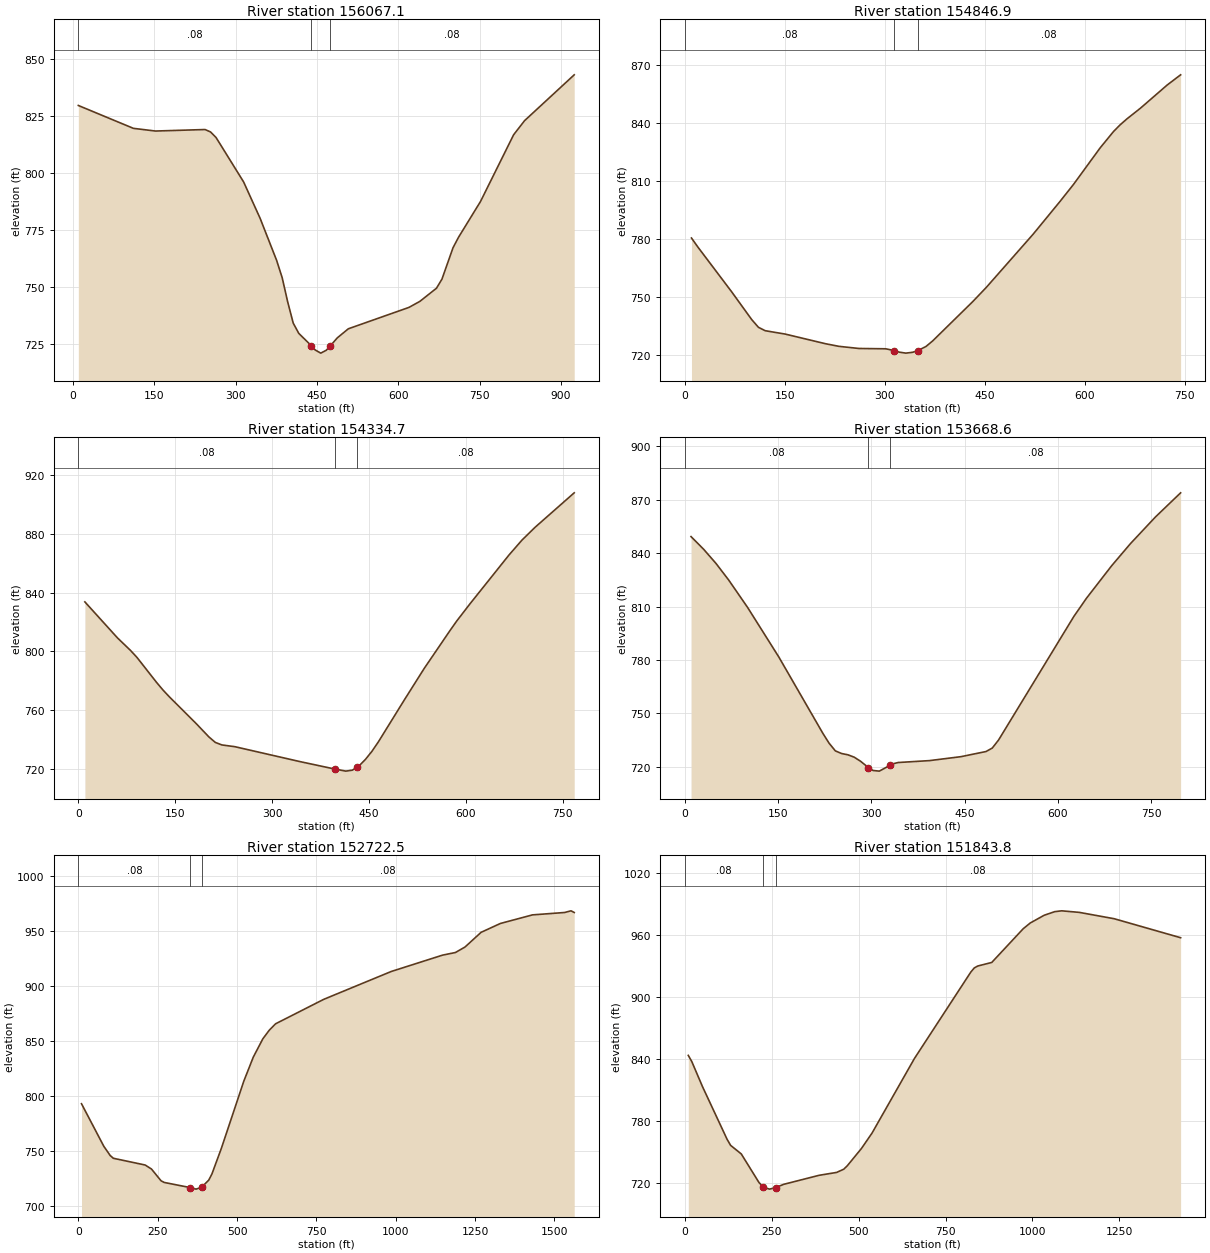
Type RM Length L Ch R = 1 ,156067.1,1204.6,1220.2,1235.7
XS GIS Cut Line= 2
     1593452.746       372581.92     1593377.029      371660.701
#Sta/Elev= 30
    10.2  829.82   111.7  819.78   152.4   818.6   243.8  819.26   253.9  818.21
   264.1  815.75   314.9  796.26   345.4  780.24   375.8  761.79     386   754.2
   396.1  743.64   406.3  734.32   416.5  729.82   439.6  724.41   446.9   722.5
   457.1  721.13   467.2  722.38   474.6  724.28   487.6  727.84   507.9  731.81
   619.6  741.19   639.9  743.86   670.4  749.62   680.5  753.61   700.9  767.38
     711  771.96   751.6   787.7   812.6  816.96   832.9  823.18   924.3  843.27
#Mann= 3 , 0 , 0
    10.2     .08       0   439.6    .045       0   474.6     .08       0
Bank Sta=439.6,474.6
XS Rating Curve= 0 ,0
Exp/Cntr=0.3,0.1

Type RM Length L Ch R = 1 ,154846.9,477.1,512.2,547.4
XS GIS Cut Line= 2
     1594430.752       372121.31     1594714.689      371433.551
#Sta/Elev= 30
    10.1  780.44    20.1  775.58    70.4  752.59   100.5  738.19   110.6   734.2
   120.7  732.44   150.8  730.69   211.2   725.7   231.3  724.35   261.4  723.24
   301.6  723.07   314.3  722.17   321.8  721.34   331.8  720.83   341.9  721.26
   349.3  722.06     362  724.27     372  727.14   432.4  747.58   452.5  754.85
   522.9  782.45   563.1  799.36   583.2   808.1   623.4  827.12   643.5   835.6
   653.6  839.11   663.6  842.13   683.7  847.61     724  859.66   744.1  864.92
#Mann= 3 , 0 , 0
       0     .08       0   314.3    .045       0   349.3     .08       0
Bank Sta=314.3,349.3
XS Rating Curve= 0 ,0
Exp/Cntr=0.3,0.1

Type RM Length L Ch R = 1 ,154334.7,685.4,666.1,646.6
XS GIS Cut Line= 2
     1594380.274      372279.053      1595143.75      372197.027
#Sta/Elev= 30
    10.1  833.78    60.6  809.25    80.8  800.71    90.9   795.9   121.2  778.89
   131.3  773.63   141.4   768.9   181.9  751.15   202.1  741.82   212.2  738.02
   222.3  736.32   242.5  735.12   343.5  724.94   396.7  719.94   414.2  718.48
   424.3  719.13   431.7  721.18   434.5  721.95   444.6  726.47   454.7     732
   464.8  738.53   505.2  767.25   535.5  788.37   575.9  814.47     586  820.76
   606.2  832.29   666.8  865.66     687  875.86   707.2  884.56   767.9  908.07
#Mann= 3 , 0 , 0
       0     .08       0   396.7    .045       0   431.7     .08       0
Bank Sta=396.7,431.7
XS Rating Curve= 0 ,0
Exp/Cntr=0.3,0.1

Type RM Length L Ch R = 1 ,153668.6,959.1,946,933.3
XS GIS Cut Line= 2
     1594550.637      373080.387      1595162.68        372569.3
#Sta/Elev= 30
    10.1  849.26    30.3  842.19    50.5   834.1    70.7  824.87   100.9  809.61
   151.4  781.63   222.1  738.87   232.1  733.33   242.2  729.02   252.3  727.52
   262.4  726.81   272.5  725.48   282.6  723.22   295.4  719.65   302.8  718.01
   312.9  717.65   330.4  720.98   333.1   721.6   343.2  722.48   393.6  723.55
   444.1  725.76   484.5  728.65   494.6  730.61   504.7  735.14   625.8  804.49
     646  814.66   686.3  832.81   716.6  845.26     757   860.3   797.4  873.82
#Mann= 3 , 0 , 0
       0     .08       0   295.4    .045       0   330.4     .08       0
Bank Sta=295.4,330.4
XS Rating Curve= 0 ,0
Exp/Cntr=0.3,0.1

Type RM Length L Ch R = 1 ,152722.5,874,878.7,883.6
XS GIS Cut Line= 3
     1595440.307        373477.9     1595723.974      372924.989
     1596161.297      372091.778
#Sta/Elev= 30
      10  793.01    80.2  754.42   100.2  746.06   110.3   743.5   210.5  737.38
   230.5  733.72   260.6  723.08   270.6  721.55   353.4  716.85   370.9  715.49
   388.4  717.16   410.9  723.66     421  729.32     451  752.79   521.2  813.38
   551.3  835.37   581.3  851.93   601.4  859.69   621.4  865.57   773.2  887.78
   985.7  913.05  1147.6  927.92  1188.1  930.29  1218.4  935.29    1269  948.62
  1329.7  956.65  1430.9  964.46  1532.1  966.62  1552.3  968.14  1562.4  966.63
#Mann= 3 , 0 , 0
       0     .08       0   353.4    .045       0   388.4     .08       0
Bank Sta=353.4,388.4
XS Rating Curve= 0 ,0
Exp/Cntr=0.3,0.1

Type RM Length L Ch R = 1 ,151843.8,628.9,665.4,702.1
XS GIS Cut Line= 3
     1596137.163      373837.554     1596585.129      373208.269
     1596977.335       372685.26
#Sta/Elev= 30
    10.2  843.19    20.3  837.21    50.8   813.1     122  761.74   132.1  755.95
   162.6  747.71   213.4  720.08   226.4  715.41   243.9   713.6   261.4  715.04
   284.6  718.25   386.2  726.97     437   729.8   457.4  732.91   467.5  736.23
   508.2  752.96   538.7  767.91   660.6  840.16   822.7  923.86   832.8  927.93
   842.8  929.78   883.1  933.24   973.6  965.94   993.7  971.46  1033.9  978.97
  1064.1  982.44  1084.2  983.25  1134.5  981.76  1235.1   975.6  1426.2   957.2
#Mann= 3 , 0 , 0
       0     .08       0   226.4    .045       0   261.4     .08       0
Bank Sta=226.4,261.4
XS Rating Curve= 0 ,0
Exp/Cntr=0.3,0.1

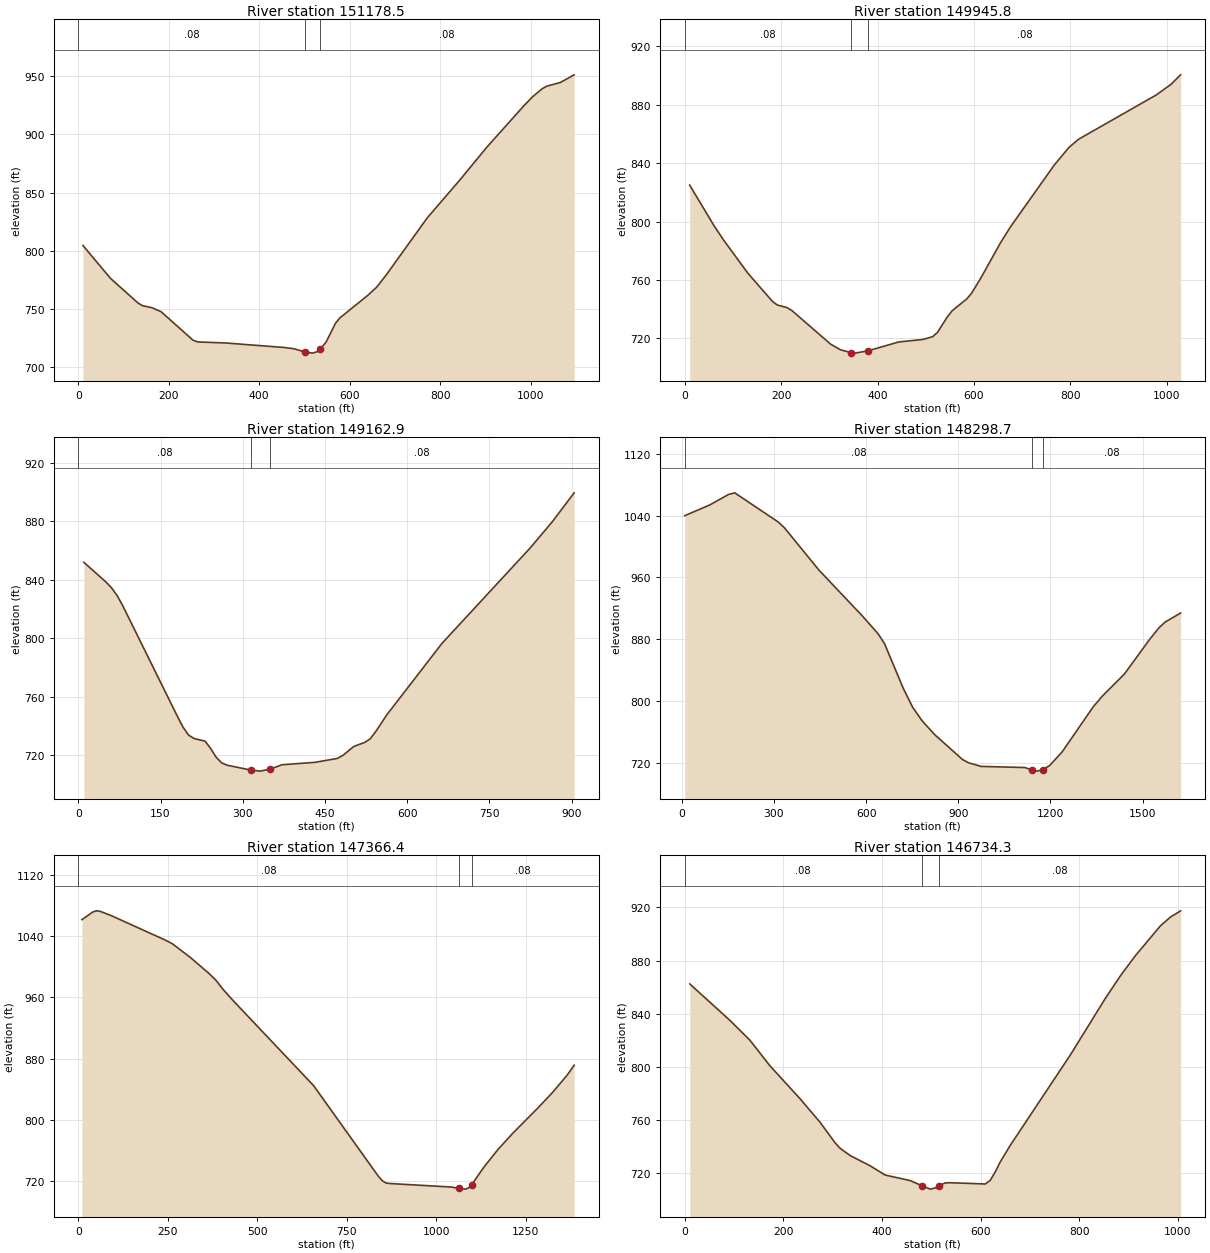
Type RM Length L Ch R = 1 ,151178.5,1217.4,1232.7,1247.6
XS GIS Cut Line= 2
     1596285.809      373888.031     1597364.771      374083.633
#Sta/Elev= 30
    10.2  804.59    71.1  776.41     132  755.29   142.1  752.98   162.5  751.29
   182.8   747.9   253.8  723.35     264  721.93   324.9  721.04   456.9  717.11
   477.2  716.02   500.3  713.46   517.8  712.32     528  713.48   535.3  715.76
   548.3   722.1   568.6  737.85   578.7  742.62   639.7  761.71     660  768.95
   680.3  779.02   771.6  828.26   842.7  860.27   903.6  888.95   984.9   924.2
  1005.2   932.3  1025.5  938.91  1035.6  941.12  1066.1  944.37  1096.5   950.9
#Mann= 3 , 0 , 0
       0     .08       0   500.3    .045       0   535.3     .08       0
Bank Sta=500.3,535.3
XS Rating Curve= 0 ,0
Exp/Cntr=0.3,0.1

Type RM Length L Ch R = 1 ,149945.8,784.5,782.8,784.6
XS GIS Cut Line= 2
     1595736.864      374664.127     1596695.941        375036.4
#Sta/Elev= 30
    10.1  824.93    60.5  797.24    80.7  787.22   131.1  764.52   181.6  745.43
   191.6  742.89   211.8  741.11   221.9  739.15   302.6  716.03   322.8  712.23
   345.6  710.17     353   709.9   380.6  711.51   443.8  717.54   494.2  719.25
   514.4  721.17   524.5  724.18   544.7  734.69   554.7  738.91     585  747.02
   595.1  750.91   615.3  761.92   655.6  785.76   675.8  796.37   766.6  838.66
   796.8  850.62     817  856.32   978.4  886.69  1008.6  893.87  1028.8  900.44
#Mann= 3 , 0 , 0
       0     .08       0   345.6    .045       0   380.6     .08       0
Bank Sta=345.6,380.6
XS Rating Curve= 0 ,0
Exp/Cntr=0.3,0.1

Type RM Length L Ch R = 1 ,149162.9,847.6,864.3,877.5
XS GIS Cut Line= 2
     1595471.856      375143.666     1596165.925       375724.16
#Sta/Elev= 30
    10.1  851.98    50.3  838.54    60.3  834.64    70.4  829.47    80.4  822.75
     181   746.4     191  739.16   201.1  733.74   211.1   731.4   231.2  729.59
   241.3  724.68   251.3  718.69   261.4  714.74   271.4  713.14   314.3   709.8
   331.8  709.06   349.3  710.35     372  713.44   432.3  715.09   472.5  717.74
   482.6  719.78   502.7  725.96   522.8  728.74   532.8  731.24   542.9  736.22
     563  747.63   663.5  796.44   824.4  861.74   864.6  879.59   904.8  899.54
#Mann= 3 , 0 , 0
       0     .08       0   314.3    .045       0   349.3     .08       0
Bank Sta=314.3,349.3
XS Rating Curve= 0 ,0
Exp/Cntr=0.3,0.1

Type RM Length L Ch R = 1 ,148298.7,974.2,932.3,890.3
XS GIS Cut Line= 3
     1594216.585      374863.126     1594859.162      375392.705
     1595194.228      376109.053
#Sta/Elev= 30
    10.2 1039.85    91.4 1053.74   152.3  1067.3   172.6 1069.45   314.8 1031.51
   335.1 1023.83   446.8  969.34     589  909.56   639.7  886.64   660.1  874.09
     721  816.29   751.4   791.9   781.9  774.43   822.5  756.58   913.8  724.06
   934.1  719.76   974.6  715.15  1116.6  713.69  1139.6  710.64  1157.1  709.04
  1174.6  710.98  1197.7  716.41  1238.2  734.05  1339.6  792.54    1370  806.74
    1441  835.01  1522.1  879.35  1552.5  894.43  1572.8  901.99  1623.5   913.8
#Mann= 3 , 0 , 0
    10.2     .08       0  1139.6    .045       0  1174.6     .08       0
Bank Sta=1139.6,1174.6
XS Rating Curve= 0 ,0
Exp/Cntr=0.3,0.1

Type RM Length L Ch R = 1 ,147366.4,643.3,632.1,621
XS GIS Cut Line= 2
     1593768.905       376376.02     1595124.821      376090.123
#Sta/Elev= 30
    10.1 1061.84    40.5 1071.95    50.6 1073.42    60.7 1072.76      91 1067.35
   242.8 1035.17     263 1030.25   313.6 1012.15   364.1  991.82   384.4  982.66
   404.6  970.51   434.9  954.71   657.5  844.52   829.4  731.76   839.5  725.26
   849.6  719.86   859.8     717   869.9  716.31  1041.8  711.71  1064.8  709.87
  1082.3  708.95  1092.4  711.01  1099.8  714.97  1132.9  737.46  1173.3  761.15
  1213.8  781.91  1284.6  815.36    1325  835.41  1365.5  857.86  1385.7  871.21
#Mann= 3 , 0 , 0
       0     .08       0  1064.8    .045       0  1099.8     .08       0
Bank Sta=1064.8,1099.8
XS Rating Curve= 0 ,0
Exp/Cntr=0.3,0.1

Type RM Length L Ch R = 1 ,146734.3,647.1,614.5,582
XS GIS Cut Line= 2
     1594575.876      377011.342     1595433.997      376487.636
#Sta/Elev= 30
    10.2  862.42    91.4  835.01     132  820.06   172.6   800.8   233.6  776.01
   274.2  758.27   304.6  742.85   314.8  738.68   335.1  733.22   375.7  725.48
   406.2  718.49     457  714.33   480.1  710.61   497.6  707.89   507.7  708.77
   515.1  710.47     528  712.55   538.2  712.71   609.3  711.77   619.4  714.56
   629.6  720.95   639.7  728.45     660  740.92   781.9  809.05     853  851.77
   883.5  868.68   913.9  883.84   964.7  906.34     985  912.87  1005.3  917.49
#Mann= 3 , 0 , 0
       0     .08       0   480.1    .045       0   515.1     .08       0
Bank Sta=480.1,515.1
XS Rating Curve= 0 ,0
Exp/Cntr=0.3,0.1

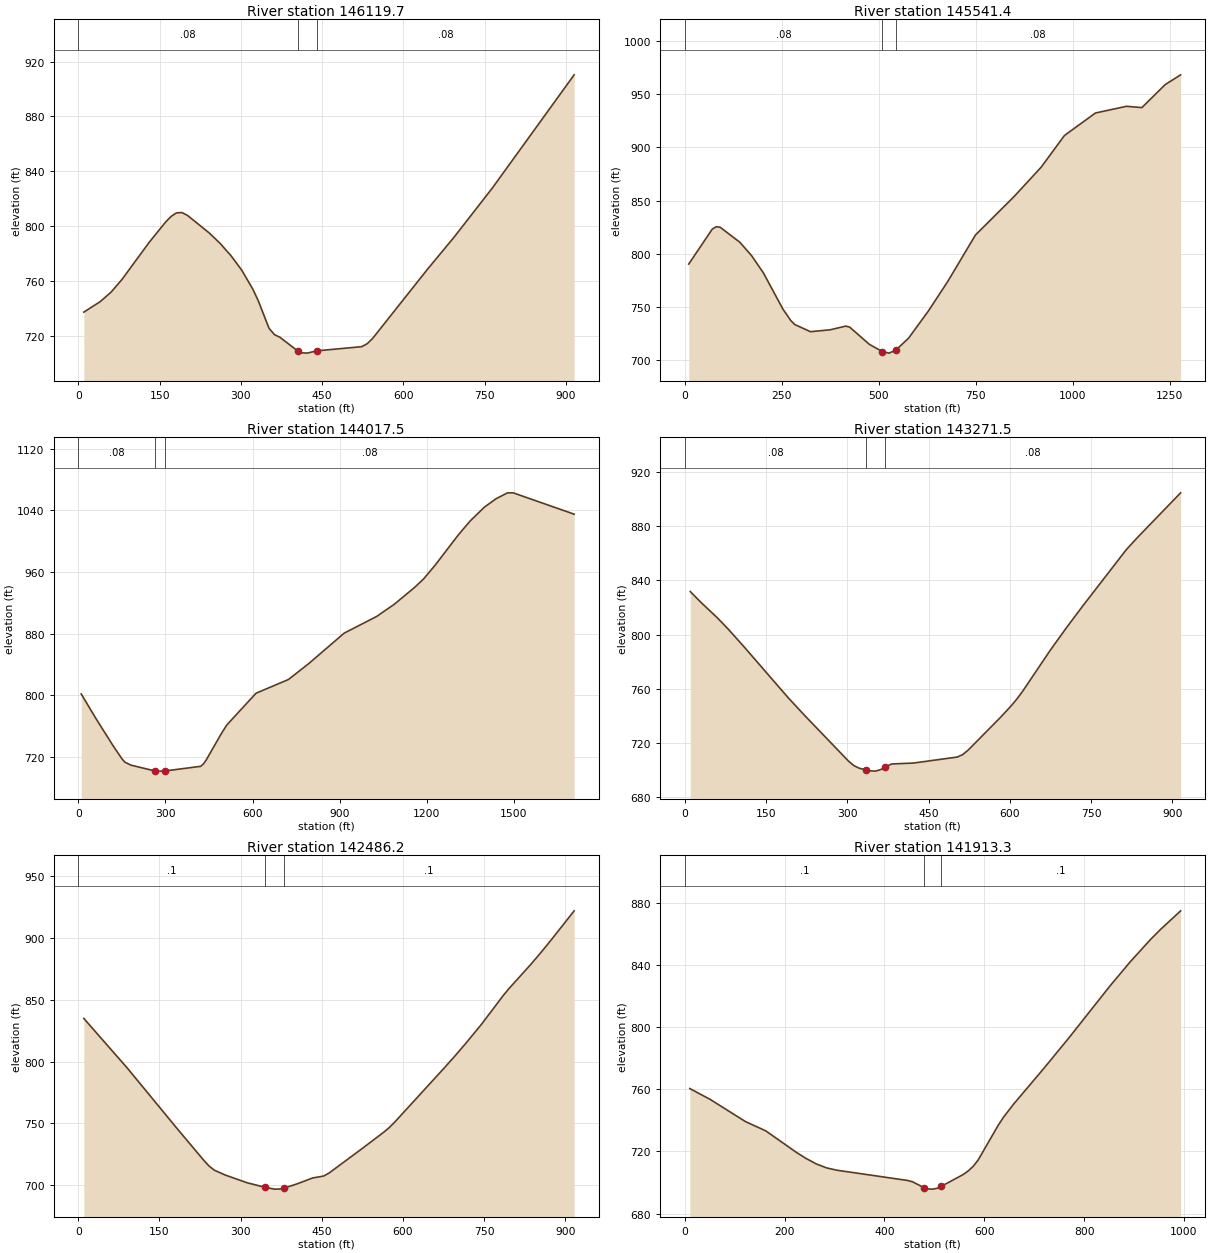
Type RM Length L Ch R = 1 ,146119.7,589.1,578.3,567.6
XS GIS Cut Line= 2
     1595471.856      377408.855     1595490.785      376493.945
#Sta/Elev= 30
    10.1  737.07    40.2   744.7    60.3  751.63    80.4  760.86   130.7  787.99
   160.9  802.76     171  806.87     181  809.53   191.1  809.75   201.1   807.8
   241.3  794.96   261.5  787.33   281.6  778.37   301.7  767.67   321.8  754.06
   331.9  745.59     352  725.26     362  720.67   372.1  718.73   404.9  708.76
   412.3  707.42   422.4  707.17   439.9  708.83   522.9  711.88     533     714
     543  717.83   643.6  767.98   693.9     792   764.3  827.77   915.1  910.28
#Mann= 3 , 0 , 0
       0     .08       0   404.9    .045       0   439.9     .08       0
Bank Sta=404.9,439.9
XS Rating Curve= 0 ,0
Exp/Cntr=0.3,0.1

Type RM Length L Ch R = 1 ,145541.4,1460.5,1523.9,1586.9
XS GIS Cut Line= 3
     1596128.067      377232.183     1595901.834      376518.278
     1596166.596      376060.687
#Sta/Elev= 30
    10.1  790.34    70.8   823.2      81  825.48    91.1  824.98   141.7  810.92
     172  798.32   202.4  782.13     253  747.93   273.2  737.22   283.4  733.53
   323.8  726.79   374.4  728.56   414.9  732.05     425  731.04   475.6  714.89
   508.7  708.15   526.2  706.64   543.7  709.43   576.8  720.79   627.5  746.15
   678.1  774.31   748.9  817.64   848.6  853.87   918.5  881.55   978.3  911.23
  1058.1  932.35  1137.9  938.66  1177.8  937.45  1237.7  959.02  1277.6  968.25
#Mann= 3 , 0 , 0
       0     .08       0   508.7    .045       0   543.7     .08       0
Bank Sta=508.7,543.7
XS Rating Curve= 0 ,0
Exp/Cntr=0.3,0.1

Type RM Length L Ch R = 1 ,144017.5,749,746,743.4
XS GIS Cut Line= 4
     1596029.851      377331.226      1596625.76       377471.44
     1597200.719      377421.474     1597718.116      377459.332
#Sta/Elev= 30
      10  801.76    60.2  770.09   120.4  734.13   150.5  717.43   160.6  713.19
   180.6  709.39   263.5  701.82     281  701.55   298.5  701.76   421.5   707.8
   431.5  711.12   441.6  716.67   491.8  749.74   511.8   761.6   612.2  802.71
   723.6  820.43   794.4  841.35   915.9  880.71  1027.3  902.25  1088.1  918.05
  1158.9  940.21  1189.3  951.03  1229.2  968.92    1309  1008.2  1348.9 1025.94
  1398.8 1044.23  1438.7 1055.09  1478.6 1062.85  1498.6 1062.78  1708.1 1035.13
#Mann= 3 , 0 , 0
       0     .08       0   263.5    .045       0   298.5     .08       0
Bank Sta=263.5,298.5
XS Rating Curve= 0 ,0
Exp/Cntr=0.3,0.1

Type RM Length L Ch R = 1 ,143271.5,792.4,785.3,778.2
XS GIS Cut Line= 2
     1595799.961      378083.995      1596714.87      378058.756
#Sta/Elev= 30
    10.1  831.78    30.2  823.64    60.3  812.27    80.5  803.86   110.6  790.38
   191.1  753.17   221.3  740.14   301.7  706.62   311.8  703.16   321.8  701.17
   334.5  699.87     342  699.25     352     699   362.1   700.2   369.5  702.09
   382.2   704.3   422.4  704.98   502.9  709.42   512.9  711.17     523  714.52
   583.4  739.01   603.5  747.73   613.5  752.56   623.6  758.01   673.9  787.93
     704  804.75   734.2  820.87   814.7  862.59   834.8   871.4   915.3  904.77
#Mann= 3 , 0 , 0
       0     .08       0   334.5    .045       0   369.5     .08       0
Bank Sta=334.5,369.5
XS Rating Curve= 0 ,0
Exp/Cntr=0.3,0.1

Type RM Length L Ch R = 1 ,142486.2,594.6,572.9,551.2
XS GIS Cut Line= 2
     1596096.518      378879.019     1596986.188      378658.179
#Sta/Elev= 30
    10.1  834.79    90.7  794.65   181.3   746.6   231.7  720.42   241.8  715.63
   251.8  712.25     272  708.35   312.3  702.15   345.1  698.54   362.6  697.05
   372.7  697.12   380.1  697.84   402.9  701.06   433.2  706.04   453.3  707.59
   463.4  709.97   523.8  729.49   564.1  742.79   574.2  746.45   584.3  750.81
   674.9  794.03   695.1  803.87   715.2  814.07   745.4  830.05   785.7  853.31
   795.8  858.65   836.1  878.14   856.2  888.42   876.4  899.27   916.7  921.58
#Mann= 3 , 0 , 0
       0      .1       0   345.1    .045       0   380.1      .1       0
Bank Sta=345.1,380.1
XS Rating Curve= 0 ,0
Exp/Cntr=0.3,0.1

Type RM Length L Ch R = 1 ,141913.3,793.7,762.4,731.1
XS GIS Cut Line= 2
     1596355.216      379692.973     1596967.259      378910.568
#Sta/Elev= 30
    10.1  760.48    50.7  753.53   121.6  739.22   162.2  733.27     223  719.55
   243.3  715.44   263.5  711.99   283.8  709.46   304.1  707.97     446  701.36
   456.1  700.53   479.2  696.73   486.5  695.91   496.7  695.77   506.8  696.38
   514.2  697.62   557.5  705.11   567.6  707.42   577.8  710.43   587.9   714.6
   628.4  737.09   638.6  742.05   658.9  750.52   719.7  773.58   770.4  793.42
   851.4  826.31     892  841.87   932.5  856.19   952.8  862.76   993.4  874.83
#Mann= 3 , 0 , 0
       0      .1       0   479.2    .045       0   514.2      .1       0
Bank Sta=479.2,514.2
XS Rating Curve= 0 ,0
Exp/Cntr=0.3,0.1

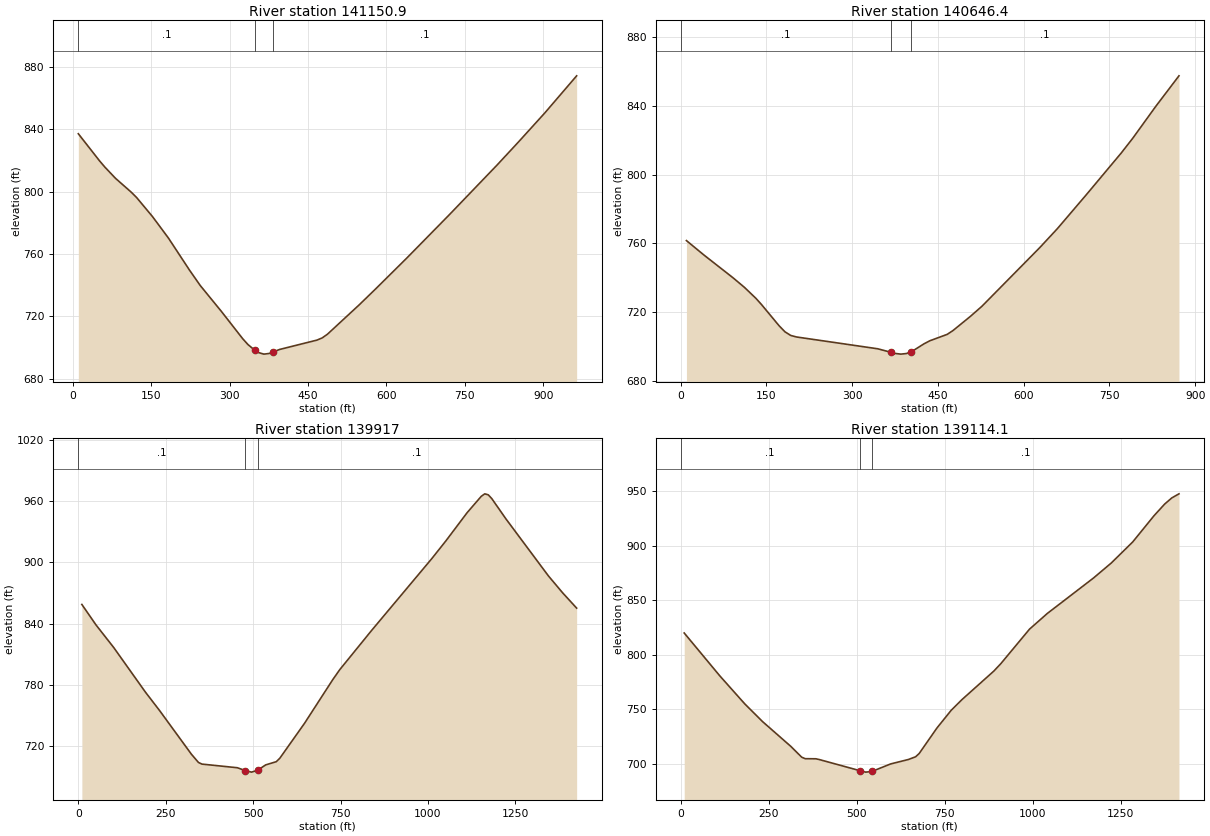
Type RM Length L Ch R = 1 ,141150.9,481.9,504.5,527
XS GIS Cut Line= 2
     1597371.081      379793.929     1597087.144      378872.709
#Sta/Elev= 30
    10.1  837.11    50.7  819.73    60.9  815.72    81.2  808.54   111.6  799.57
   121.8  796.15   152.2  783.92   182.6  770.19   223.2   749.5   243.5  739.75
   284.1  723.09   324.7  705.66   334.9  701.87   347.8  698.28   355.2  696.73
   365.3  695.75   375.4  696.16   382.8  697.13   395.7  698.77   466.8  704.74
   476.9  706.15   487.1  708.56   547.9  727.41   578.4  737.31   639.3  757.52
   720.5  785.24   811.8  817.08   852.4  831.74   903.1  850.47     964  874.26
#Mann= 3 , 0 , 0
    10.1      .1       0   347.8    .045       0   382.8      .1       0
Bank Sta=347.8,382.8
XS Rating Curve= 0 ,0
Exp/Cntr=0.3,0.1

Type RM Length L Ch R = 1 ,140646.4,698.6,729.4,760.3
XS GIS Cut Line= 2
     1597566.682      379585.708     1597894.788      378778.064
#Sta/Elev= 30
    10.1  761.57    40.5  753.23    91.2  740.02   111.5  734.35   131.8  727.88
   141.9  724.13   172.3  711.92   182.5  708.42   192.6  706.31   202.7  705.42
   344.6  698.55   367.7  696.51   375.1  695.84   385.2  695.43   395.3  695.79
   402.7  696.81   405.5  697.19   425.7  701.44   435.9  703.21   466.3  706.95
   476.4  709.17   506.8  717.41   527.1  723.34   628.5  757.59   658.9  768.49
   709.6  788.28   770.4  812.48   790.7  821.12   831.2  839.81   871.7  857.56
#Mann= 3 , 0 , 0
       0      .1       0   367.7    .045       0   402.7      .1       0
Bank Sta=367.7,402.7
XS Rating Curve= 0 ,0
Exp/Cntr=0.3,0.1

Type RM Length L Ch R = 1 ,139917  ,785.5,802.9,820.5
XS GIS Cut Line= 2
     1597422.348      380006.093     1598810.486       379682.72
#Sta/Elev= 30
    10.1  858.74    50.5  838.66   101.1  816.48   192.1  772.51   232.5  754.46
   323.5  711.57   343.7  703.47   353.8  701.88   454.9  698.31   477.8  695.48
   495.3     694   512.8  695.83   535.8   701.1   566.1  704.25   576.2   707.6
   646.9  741.93   727.8   784.9     748   794.8     839  833.27  1010.9  903.73
  1051.3  921.19  1111.9  948.85  1152.4  964.95  1162.5  967.43  1172.6  966.42
  1182.7   962.7  1223.1  942.79  1344.4  886.86  1384.9   870.3  1425.3  855.14
#Mann= 3 , 0 , 0
       0      .1       0   477.8    .045       0   512.8      .1       0
Bank Sta=477.8,512.8
XS Rating Curve= 0 ,0
Exp/Cntr=0.3,0.1

Type RM Length L Ch R = 1 ,139114.1,1221.2,1206.9,1192.4
XS GIS Cut Line= 2
     1597540.655      380534.532     1598905.132      380913.115
#Sta/Elev= 30
    10.1  819.95   111.3  780.62   182.1  754.97   232.6  738.72   313.5  715.82
   343.9  706.05     354  704.65   384.3  704.56   394.5  703.82   508.5  693.74
     526  692.33   543.5  692.98   596.8  699.85   647.3  703.93   667.6  706.42
   677.7  709.38   728.2  732.79   768.7  749.03     799  758.75   890.1  785.07
   910.3  792.02   991.2  823.43  1041.8  837.85  1173.3  870.43  1223.8   884.2
  1284.5  903.45  1345.2  927.56  1375.6  938.29  1395.8   943.9    1416  947.61
#Mann= 3 , 0 , 0
       0      .1       0   508.5    .045       0   543.5      .1       0
Bank Sta=508.5,543.5
XS Rating Curve= 0 ,0
Exp/Cntr=0.3,0.1