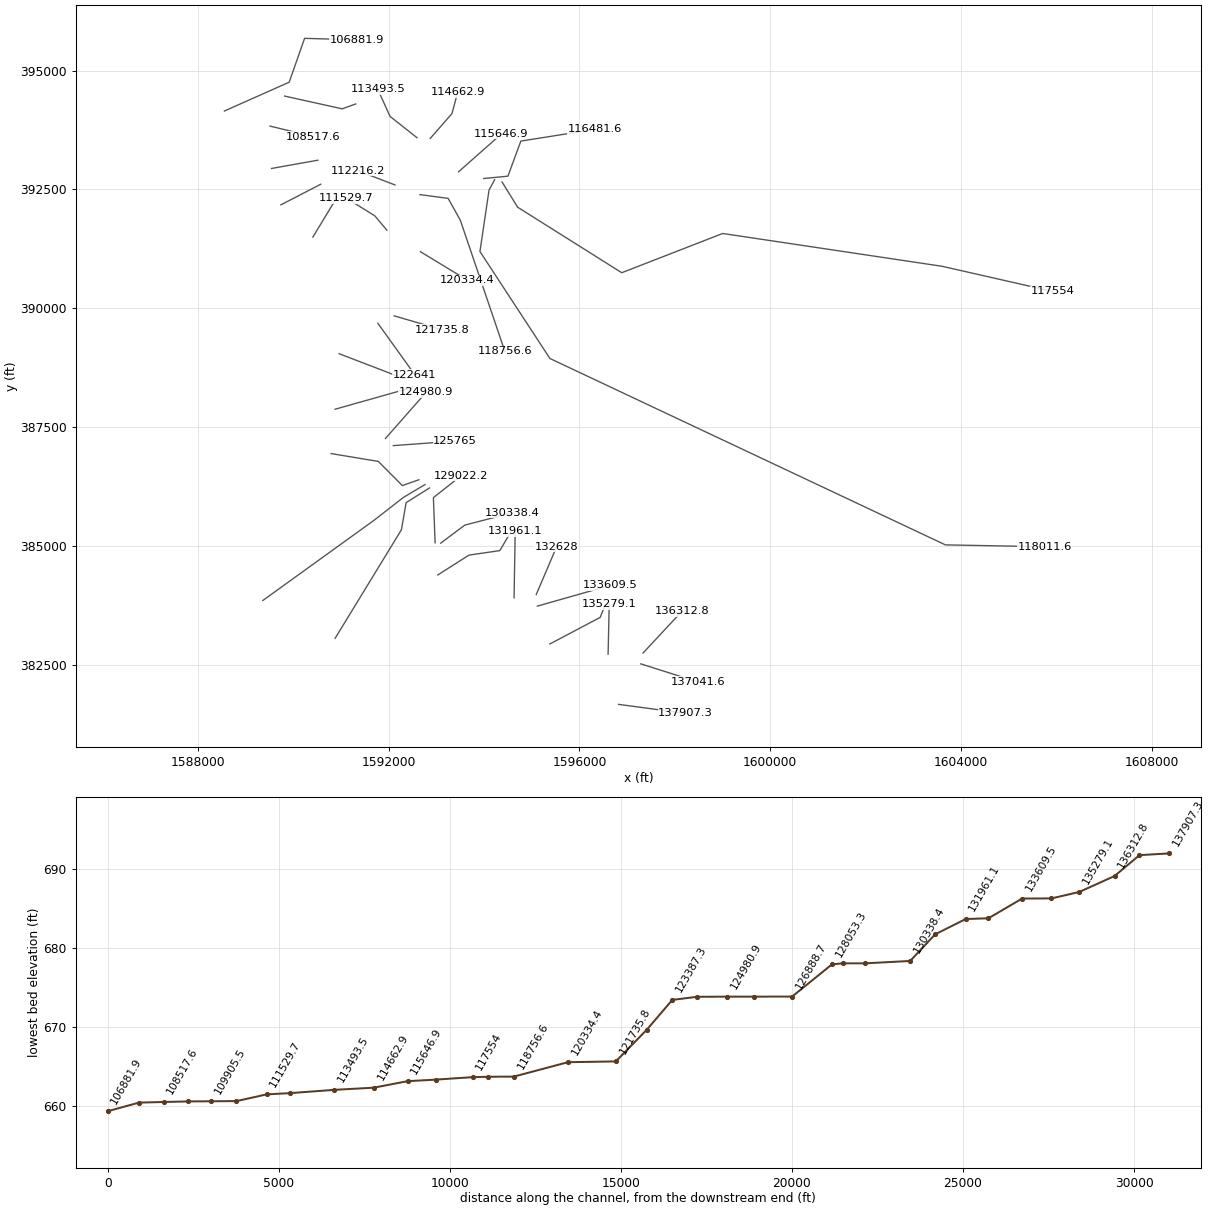
HEC-RAS study EFTWELVECR.prj: EFTWELVECR

--- EFTWELVECR.g01 (geometry) --- (continued)

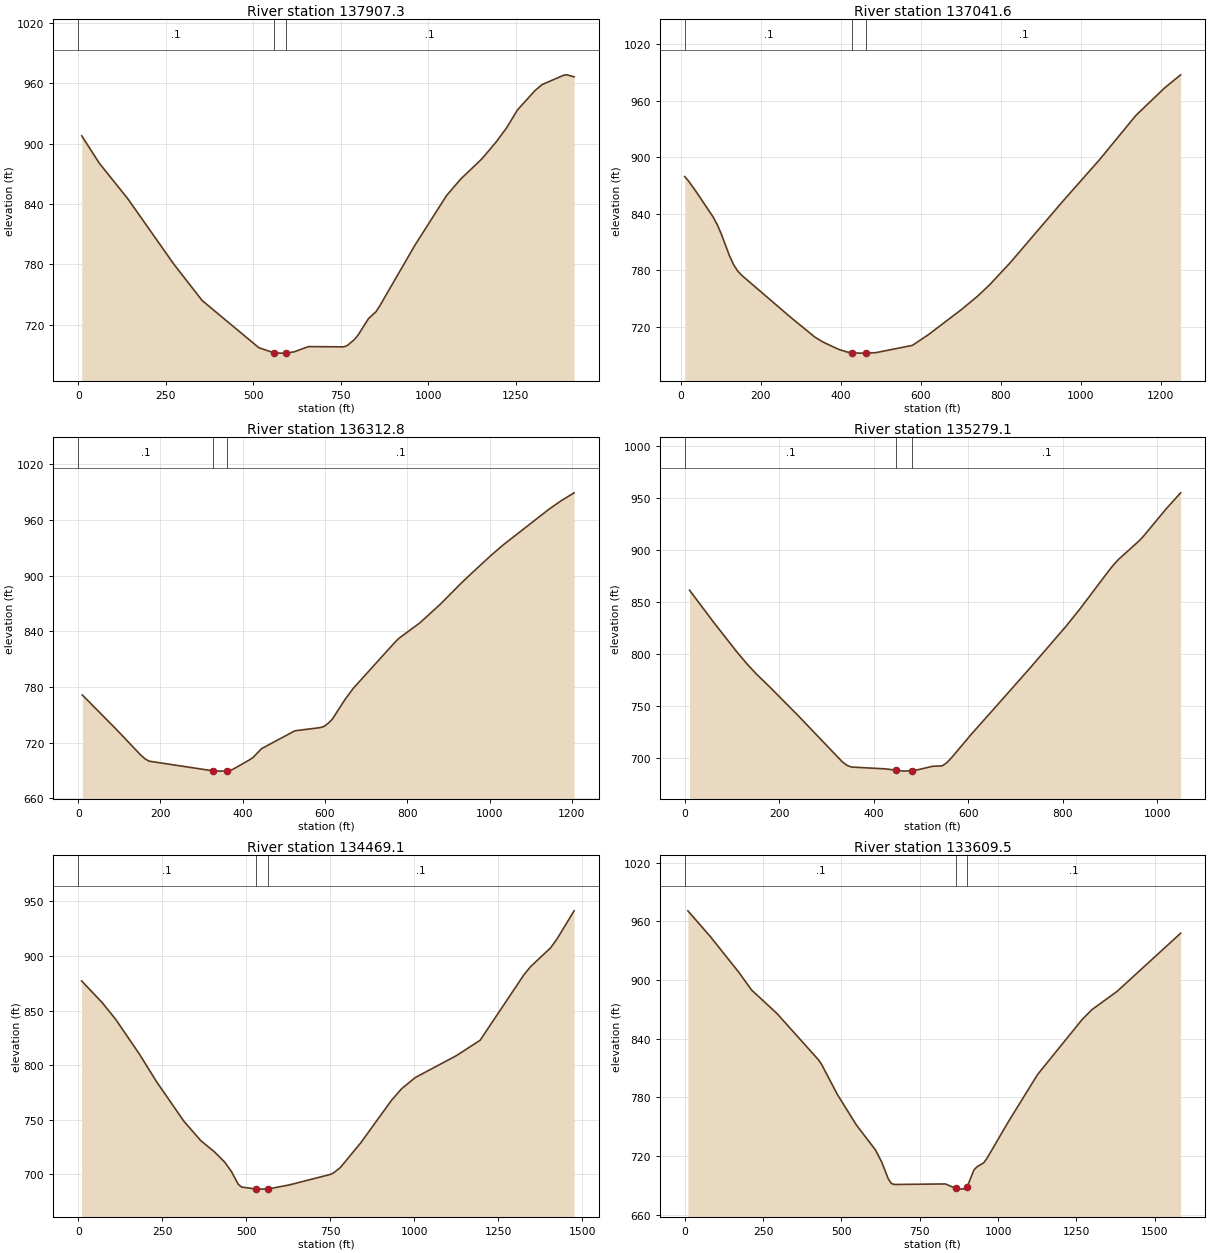
Type RM Length L Ch R = 1 ,137907.3,870.9,865.6,860.3
XS GIS Cut Line= 2
     1596822.924      381670.281     1598226.837       381480.99
#Sta/Elev= 30
    10.1  907.61    60.7  880.25   141.7  845.18   273.2  780.27   354.2  744.15
   516.1  697.36   559.3  692.31   576.8     692   594.3  692.01   617.2  693.33
   657.7  698.48   758.9  698.23     769  699.59   789.3  705.59   799.4  709.87
   829.7  726.48     850  732.83   860.1  738.07   961.3  798.72  1052.3  848.41
  1092.8  864.76  1153.5  884.88    1194  901.55  1224.4  915.88  1254.7  933.25
  1305.3  952.67  1325.5   958.5  1386.3  967.67  1396.4  968.14  1416.6  966.17
#Mann= 3 , 0 , 0
       0      .1       0   559.3    .045       0   594.3      .1       0
Bank Sta=559.3,594.3
XS Rating Curve= 0 ,0
Exp/Cntr=0.3,0.1

Type RM Length L Ch R = 1 ,137041.6,692.1,728.9,765.7
XS GIS Cut Line= 2
     1597288.266      382522.093     1598479.226       382143.51
#Sta/Elev= 30
    10.2   879.5    20.3  874.49    40.6  862.29    81.3  836.43    91.4  828.51
   101.6  818.45   121.9   795.5   132.1  786.06   142.2  779.29   152.4  774.63
   274.3   730.1   335.3  708.89   355.6   703.6   396.2  695.56   416.6  692.94
   429.5  692.11     447  691.78   464.5   691.8   487.7  692.28   579.1  700.01
   619.8  711.57     701  737.84   741.7  752.14   772.2  764.39     823  787.55
     955  853.15  1046.5   897.2  1137.9   944.5    1209  973.51  1249.7  987.68
#Mann= 3 , 0 , 0
    10.2      .1       0   429.5    .045       0   464.5      .1       0
Bank Sta=429.5,464.5
XS Rating Curve= 0 ,0
Exp/Cntr=0.3,0.1

Type RM Length L Ch R = 1 ,136312.8,1010.3,1033.7,1057.2
XS GIS Cut Line= 2
     1597335.589      382750.821     1598155.852      383634.181
#Sta/Elev= 30
    10.1  771.22    91.2  734.87     152  706.51   162.1  702.54   172.2   699.9
   326.9   689.5   344.4  689.14   361.9  689.34   374.8   690.8   415.3  700.98
   425.5  704.05   445.7   713.4   526.8  732.63   587.5  736.02   597.7  737.33
   607.8  740.76   617.9  745.24   648.3  766.23   668.6  778.38   769.9  828.08
     780  832.51   830.7  849.06   881.3  869.58     932  892.28   962.4  904.97
  1002.9  921.54  1033.3  933.16  1144.7  971.67  1175.1  981.05  1205.5  989.27
#Mann= 3 , 0 , 0
       0      .1       0   326.9    .045       0   361.9      .1       0
Bank Sta=326.9,361.9
XS Rating Curve= 0 ,0
Exp/Cntr=0.3,0.1

Type RM Length L Ch R = 1 ,135279.1,845.3,810,774.2
XS GIS Cut Line= 2
     1596602.084      382727.159     1596625.746       383776.15
#Sta/Elev= 30
    10.1  861.36    60.5  830.83     111  801.53   131.2  790.63   151.3  780.75
   181.6   767.4   242.1  739.56   332.9  696.34     343  692.72   353.1  691.04
   423.7  689.32   446.6  688.08   464.1  687.12   481.6   687.6   494.4  688.55
   524.6   691.8   544.8  692.17   554.9  695.37     565  700.27   605.3  722.03
   726.4  784.17   807.1  826.76   837.4  843.94   897.9  880.39     908  886.09
   918.1  891.07   958.5  907.61   968.5  912.13    1019  939.78  1049.3  955.07
#Mann= 3 , 0 , 0
       0      .1       0   446.6    .045       0   481.6      .1       0
Bank Sta=446.6,481.6
XS Rating Curve= 0 ,0
Exp/Cntr=0.3,0.1

Type RM Length L Ch R = 1 ,134469.1,866.5,859.5,852.5
XS GIS Cut Line= 3
     1595379.576      382940.112     1596436.454        383500.1
     1596538.987      383760.376
#Sta/Elev= 30
    10.1  877.15      71  857.38   111.5  841.97   182.5   809.9   233.1  784.82
   314.2  748.66   364.9  730.72   405.4  720.49   435.9  711.12   456.1  702.41
   476.4  690.71   486.5  688.21   529.9  686.38   537.2  686.31   564.9  686.43
   628.4  690.18   750.1  699.76   760.2  701.23   780.5  706.22   841.3  728.93
   932.5  767.76   962.9  778.46  1003.5  788.65  1125.1  808.57  1196.1  822.74
  1325.9  882.52  1345.9  890.11  1405.9  907.47  1425.9  916.03  1475.8  941.38
#Mann= 3 , 0 , 0
       0      .1       0   529.9    .045       0   564.9      .1       0
Bank Sta=529.9,564.9
XS Rating Curve= 0 ,0
Exp/Cntr=0.3,0.1

Type RM Length L Ch R = 1 ,133609.5,953.2,981.6,1009.9
XS GIS Cut Line= 2
       1595119.3      383736.714      1596641.52      384170.507
#Sta/Elev= 30
    10.1  970.76    81.2  944.66   172.5  908.01   213.1   889.9   294.2  865.88
   426.1  818.75   436.3  814.14     487  783.18   547.9  751.85   608.8  726.35
   629.1  713.68   649.4  696.98   659.5  692.02   669.7  691.05     832  691.59
   865.2  687.05   882.7  686.29   892.9  686.69   900.2  688.95     903  689.82
   923.3     706   933.5   709.3   953.8  713.05   963.9  717.35  1034.9  756.17
  1126.2  803.43  1268.3  859.61  1298.7   869.5  1379.9  888.39  1582.8  947.82
#Mann= 3 , 0 , 0
       0      .1       0   865.2    .045       0   900.2      .1       0
Bank Sta=865.2,900.2
XS Rating Curve= 0 ,0
Exp/Cntr=0.3,0.1

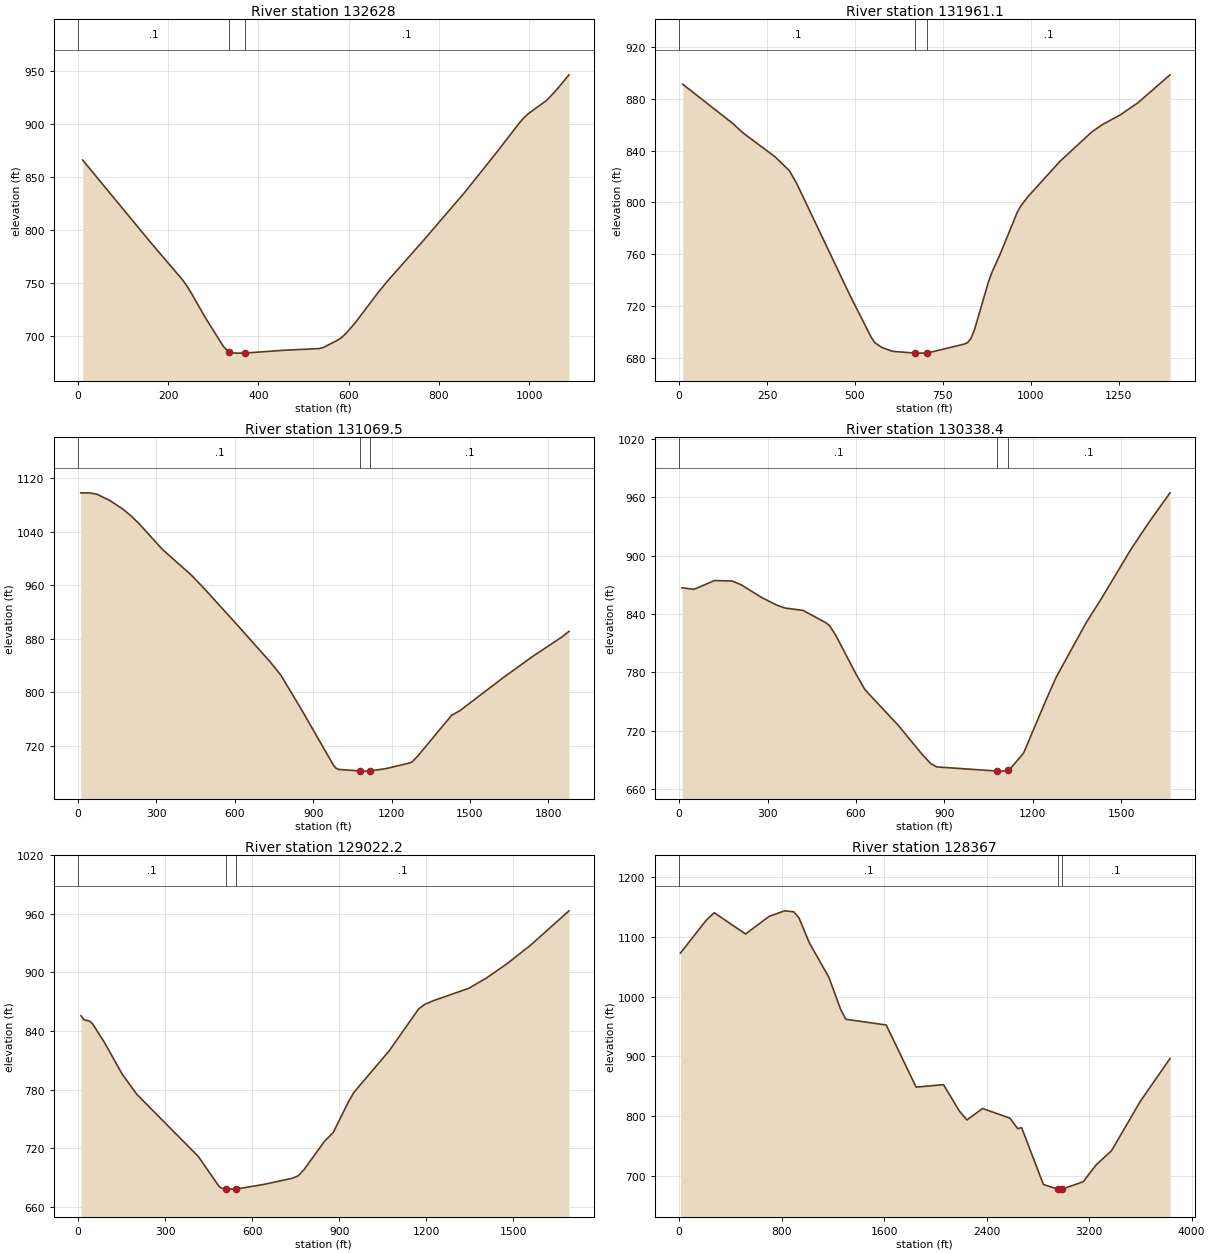
Type RM Length L Ch R = 1 ,132628  ,652.5,666.9,681.3
XS GIS Cut Line= 2
     1595095.639      383981.216     1595521.545      384982.884
#Sta/Elev= 30
    10.1   865.7   161.3  787.85   231.8  752.73   241.9   746.7     252  739.68
   282.2  717.16   322.5  689.97   332.6  685.54   335.2  685.15   342.7  684.01
   352.7   683.8   370.2  683.85   453.5  686.44   534.1  688.09   544.2  689.23
   574.5  695.76   584.5  698.57   594.6  702.65   614.8  712.53   665.2  740.83
   685.3  751.28   765.9  789.99   856.7  834.94   927.2   872.4   977.6  900.11
   987.7  905.12   997.8   909.2  1038.1  921.59  1058.2   930.4  1088.5  945.93
#Mann= 3 , 0 , 0
       0      .1       0   335.2    .045       0   370.2      .1       0
Bank Sta=335.2,370.2
XS Rating Curve= 0 ,0
Exp/Cntr=0.3,0.1

Type RM Length L Ch R = 1 ,131961.1,939.3,891.6,843.9
XS GIS Cut Line= 2
     1594630.297      383910.231     1594653.958      385306.257
#Sta/Elev= 30
    10.1  891.27   151.8  861.13   182.1  853.62   273.2  835.18   313.6  824.52
   333.9  814.94   485.6  728.49   546.3  695.96   556.5  691.79   576.7  688.06
   607.1  685.09   670.5  683.73   677.9   683.7   705.5  683.77   809.4  690.59
   819.5  691.61   829.6  694.79   839.8  701.55   880.2  739.07   890.3  746.49
   910.6  758.54   961.2  792.11   971.3  797.09   991.5   804.3  1082.6  831.59
  1173.6  854.42    1204  860.14  1254.6  867.59  1305.2     877  1396.2  898.51
#Mann= 3 , 0 , 0
       0      .1       0   670.5    .045       0   705.5      .1       0
Bank Sta=670.5,705.5
XS Rating Curve= 0 ,0
Exp/Cntr=0.3,0.1

Type RM Length L Ch R = 1 ,131069.5,727.6,731.1,734.6
XS GIS Cut Line= 4
     1593029.206      384391.347     1593683.839      384809.366
     1594330.585      384904.012     1594559.313      385290.482
#Sta/Elev= 30
    10.1 1098.42    40.3 1098.52    70.6 1096.67     121 1087.17   171.5 1074.15
   201.7 1064.34     232    1053   322.8 1013.83   433.7  975.29   484.2  954.66
   615.3  898.11   736.4  844.89   776.7  825.29   857.2  772.66   977.8  690.63
   987.9  686.05   997.9   684.3    1081     682  1098.5  681.77    1116  681.96
    1179  685.55  1269.5     694  1279.5  695.86  1299.6  703.96  1430.3   765.5
  1460.3  771.93  1629.9  822.37  1739.7  853.38  1849.5  881.88  1879.4  891.03
#Mann= 3 , 0 , 0
       0      .1       0    1081    .045       0    1116      .1       0
Bank Sta=1081,1116
XS Rating Curve= 0 ,0
Exp/Cntr=0.3,0.1

Type RM Length L Ch R = 1 ,130338.4,1272.2,1316.1,1360.1
XS GIS Cut Line= 3
     1593092.303      385061.755      1593597.08      385440.338
     1594598.748      385700.614
#Sta/Elev= 30
      10     867    50.1  865.37   120.2  874.43   180.3  873.95   210.3  870.13
   280.4  856.93   330.5  849.26   360.6  846.09   420.6  843.71   500.8  830.52
   510.8  827.81   530.8  818.54   600.9  777.87     631  762.04   742.6  725.87
   823.8  695.97   854.2  686.03   874.5  682.72  1080.2  678.46  1097.7   678.4
  1115.2   679.3  1128.1  682.52  1168.7  696.86  1249.9  754.94  1280.3  775.48
  1381.8  831.34  1432.5  855.62    1534  906.94  1594.9  934.55  1665.9  964.65
#Mann= 3 , 0 , 0
       0      .1       0  1080.2    .045       0  1115.2      .1       0
Bank Sta=1080.2,1115.2
XS Rating Curve= 0 ,0
Exp/Cntr=0.3,0.1

Type RM Length L Ch R = 1 ,129022.2,661.9,655.2,648.5
XS GIS Cut Line= 3
     1592973.996      385069.642     1592938.303      386018.933
     1593520.358      386478.613
#Sta/Elev= 30
    10.1  855.67    20.2  851.59    40.4  850.11    50.5  847.17      91  828.28
   151.6  796.08   202.1  775.32   414.3  711.55   485.1  681.16   495.2  678.93
     508  678.18   515.4   678.1     543  678.12   636.7  682.72   737.7  689.22
   757.9  691.63   778.2  697.94   848.9  727.05   879.2  736.06   929.7  766.35
     950  777.06  1071.9  819.72  1173.5  862.67  1193.8  867.19  1224.3  871.12
  1346.2  883.78  1407.2  894.34  1478.3  909.01  1559.6  928.05  1691.6  963.15
#Mann= 3 , 0 , 0
       0      .1       0     508    .045       0     543      .1       0
Bank Sta=508,543
XS Rating Curve= 0 ,0
Exp/Cntr=0.3,0.1

Type RM Length L Ch R = 1 ,128367  ,338.1,313.7,289.3
XS GIS Cut Line= 4
     1590876.863      383058.814     1592267.406      385341.638
     1592366.685      385913.567     1592855.688      386221.166
#Sta/Elev= 30
    10.2 1072.79   213.4 1128.09   274.4 1140.25   518.3 1104.68   701.3    1134
   823.2  1143.4   894.4 1141.76     935 1131.76  1016.3 1089.95  1168.8 1032.24
  1260.3  978.82  1300.9   962.1    1616  952.54  1849.8  848.68  2063.2  852.77
  2185.1  809.33  2246.1  793.71  2368.1  812.97  2581.5  796.79  2642.5   779.2
    2673  780.94  2843.1  685.79  2955.7  678.13  2973.2   678.1  2990.7  678.16
  3153.4  690.43  3253.5  718.46  3375.1   742.5  3598.1  824.54  3831.2  896.54
#Mann= 3 , 0 , 0
       0      .1       0  2955.7    .045       0  2990.7      .1       0
Bank Sta=2955.7,2990.7
XS Rating Curve= 0 ,0
Exp/Cntr=0.3,0.1

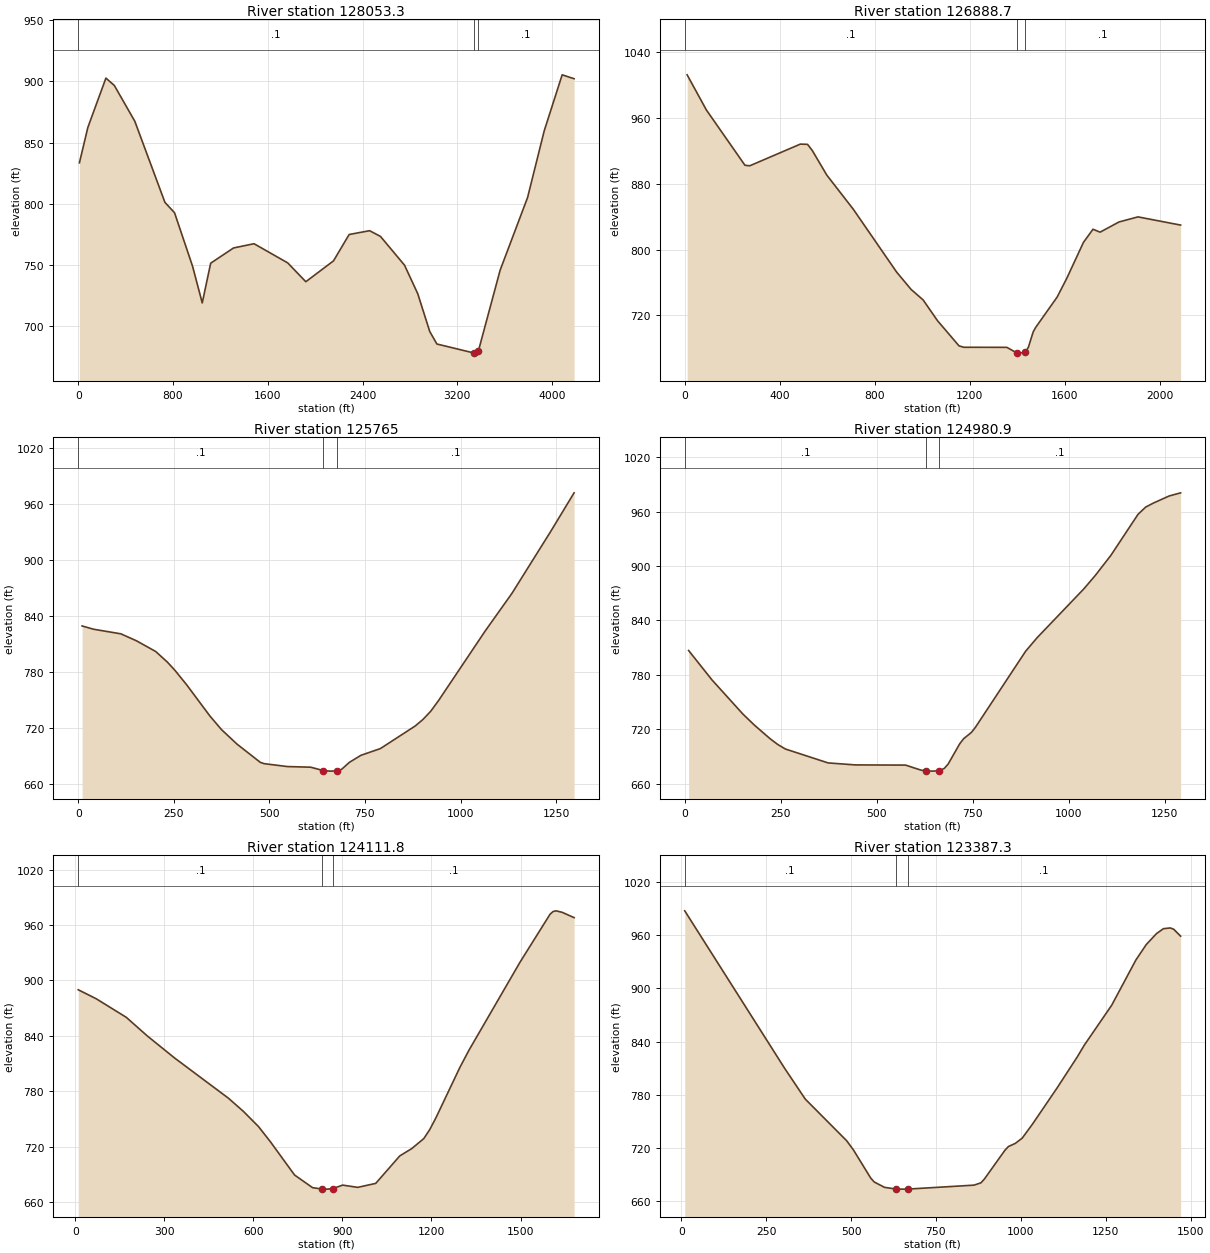
Type RM Length L Ch R = 1 ,128053.3,1211.9,1164.5,1117.2
XS GIS Cut Line= 4
     1589361.438      383855.294     1591683.955       385534.86
     1592311.475      386023.987     1592761.043       386292.15
#Sta/Elev= 30
    10.2  833.49    81.3  862.35   233.8  902.71   304.9  896.68   477.7  867.45
   731.8  801.18   813.1  792.68   965.6  748.87  1046.9     719    1118  751.44
  1311.1   763.9  1483.9  767.38  1768.5  751.69    1921  736.31  2154.7  753.36
  2286.9  774.91  2459.6  778.01  2551.1  773.35  2754.4   749.8  2866.2  726.44
  2966.9  695.68  3027.3  685.42  3342.2  678.03  3359.7  677.97  3377.2  679.59
  3561.1  745.73  3792.7  805.11  3933.6  859.74  4084.6  905.38  4185.3   902.2
#Mann= 3 , 0 , 0
       0      .1       0  3342.2    .045       0  3377.2      .1       0
Bank Sta=3342.2,3377.2
XS Rating Curve= 0 ,0
Exp/Cntr=0.3,0.1

Type RM Length L Ch R = 1 ,126888.7,1095.1,1123.8,1152.3
XS GIS Cut Line= 4
     1590793.466      386944.719     1591783.805      386779.948
     1592286.944      386271.623     1592634.848      386394.683
#Sta/Elev= 30
    10.1 1012.71    91.3  969.86   253.5  902.65   273.8  901.96   486.8  928.36
   517.2  928.08   537.5   920.4   598.3  890.62   709.9  849.03   892.4  772.54
   953.2  751.46    1004  738.64  1064.4   713.4  1155.1  682.71  1175.2  681.04
  1356.5  680.93  1399.5  673.98  1406.9   673.9  1434.5  674.94  1447.2  681.13
  1467.3  699.66  1477.4  705.02  1568.1   742.1  1608.4  764.72  1678.9  808.67
  1719.2  824.73  1749.1  821.17  1828.9   833.6  1908.7  839.77  2088.2  829.78
#Mann= 3 , 0 , 0
       0      .1       0  1399.5    .045       0  1434.5      .1       0
Bank Sta=1399.5,1434.5
XS Rating Curve= 0 ,0
Exp/Cntr=0.3,0.1

Type RM Length L Ch R = 1 ,125765  ,760.6,784,808.1
XS GIS Cut Line= 2
     1592098.522      387112.414     1593392.015       387207.06
#Sta/Elev= 30
    10.1  829.61    40.5  826.06   111.5  821.16     152  813.76   202.6  802.24
     233  790.93   253.3  781.86   283.7  766.48   344.5  733.01   374.9  718.37
   415.4  702.86   476.2  683.33   486.4  681.89   547.2  678.79   607.9  678.11
   641.1  674.47   658.6  673.89   676.1  674.08     689  675.83   709.3  683.33
   739.7  690.88   790.3  698.06   881.5  722.32   901.8  729.34   922.1  738.15
   942.3  749.46  1063.9  823.85  1134.8  864.77  1236.2  931.22    1297  972.39
#Mann= 3 , 0 , 0
       0      .1       0   641.1    .045       0   676.1      .1       0
Bank Sta=641.1,676.1
XS Rating Curve= 0 ,0
Exp/Cntr=0.3,0.1

Type RM Length L Ch R = 1 ,124980.9,884.9,869.1,852.7
XS GIS Cut Line= 2
     1591932.892       387262.27     1592784.704      388232.389
#Sta/Elev= 30
    10.1  806.88    70.6  774.62   151.3  736.86   181.5  724.56   221.9  709.74
   242.1  703.28   262.2  698.25   373.2  682.95   443.8  680.74   574.9  680.53
   615.2  674.97     628  674.12   645.5  673.89     663  674.36   675.8  676.91
   685.9  681.77   716.1  704.16   726.2  709.67   746.4  716.61   756.5  722.03
   887.6  806.13   917.8  821.16  1038.9  874.74  1069.1  889.72  1109.5   911.8
  1180.1  956.98  1200.2  965.01  1220.4  969.46  1260.8  977.15    1291  980.69
#Mann= 3 , 0 , 0
       0      .1       0     628    .045       0     663      .1       0
Bank Sta=628,663
XS Rating Curve= 0 ,0
Exp/Cntr=0.3,0.1

Type RM Length L Ch R = 1 ,124111.8,746.4,724.5,702.3
XS GIS Cut Line= 2
     1590876.014      387877.467      1592492.88      388334.922
#Sta/Elev= 30
    10.1  889.84    70.9  880.04   172.1  859.94   242.9  839.78     334  816.09
   516.2  772.33   566.9  757.96   617.5  741.58     658  724.94   738.9  689.13
   799.7  675.42   832.8   673.9   850.3  673.87   867.8  674.49   900.9  678.23
   951.5  675.78  1012.2  680.09  1093.2  709.85  1133.7  717.81  1174.2  728.65
  1194.5  738.56  1214.7  750.99  1295.7  805.74    1326  824.21  1498.1  919.64
  1599.4  971.65  1609.5  974.53  1619.6  975.31  1639.8  973.72  1680.3  967.96
#Mann= 3 , 0 , 0
    10.1      .1       0   832.8    .045       0   867.8      .1       0
Bank Sta=832.8,867.8
XS Rating Curve= 0 ,0
Exp/Cntr=0.3,0.1

Type RM Length L Ch R = 1 ,123387.3,764.5,746.3,729.5
XS GIS Cut Line= 2
     1590962.773      389044.765     1592335.137      388516.326
#Sta/Elev= 30
    10.1  987.66   304.3   809.9   365.1  775.12   486.8   728.2   507.1  717.67
   557.8     686     568   681.6   598.4  675.49   631.6  673.64   649.1  673.48
   666.6   673.5   862.1  677.98   882.4   680.6   892.5  684.79   953.3  717.44
   963.5  721.58   983.8  725.13  1004.1  731.09  1034.5  746.98  1105.5  786.97
  1166.3  822.79  1186.6  835.84  1267.7  881.16  1338.7  932.04  1369.2  949.49
  1399.6  961.97  1419.9  967.47  1440.2  968.34  1450.3  966.87  1470.6  959.07
#Mann= 3 , 0 , 0
    10.1      .1       0   631.6    .045       0   666.6      .1       0
Bank Sta=631.6,666.6
XS Rating Curve= 0 ,0
Exp/Cntr=0.3,0.1

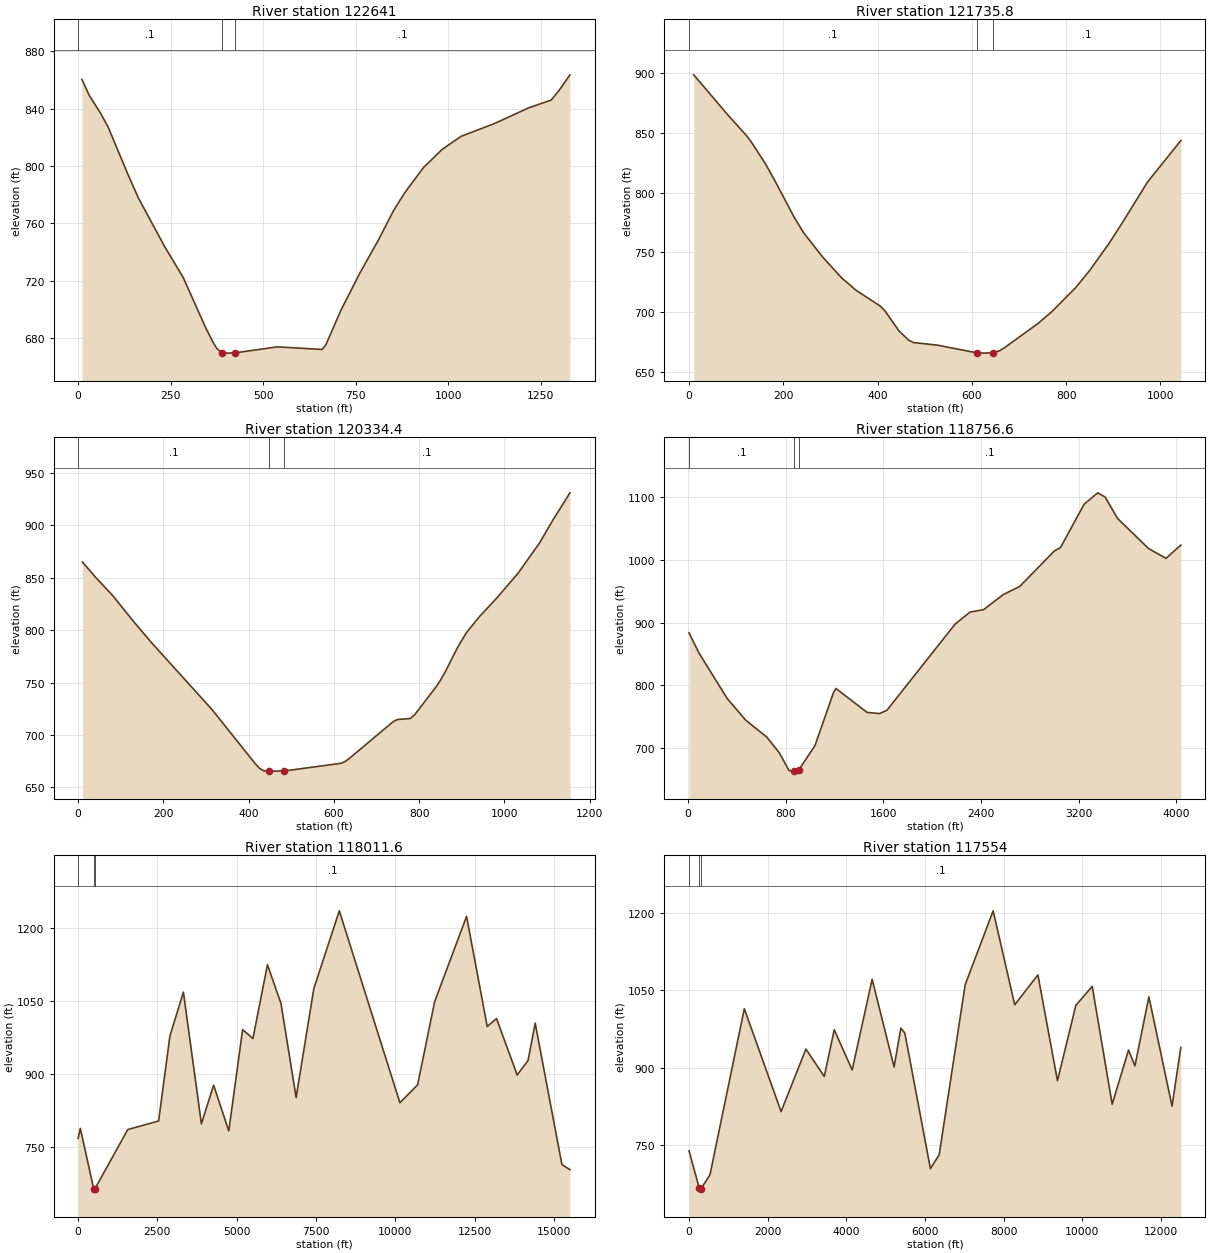
Type RM Length L Ch R = 1 ,122641  ,883.3,905.2,926.2
XS GIS Cut Line= 2
     1591775.149      389683.624      1592548.09      388603.085
#Sta/Elev= 30
    10.1  860.27    30.4  849.03    60.8  836.65    81.1  827.12   131.8  795.77
   162.3  777.97   233.3  744.08     284  722.29   344.8  687.23   365.1  676.96
   375.2   672.8   388.2  670.07   405.7  669.71   423.2  669.87   537.5  674.07
   659.2  672.28   669.3  675.63   709.9  699.56   760.6  725.27   811.3  748.57
   851.9  768.91   882.3  781.42     933  798.97   983.7  811.65  1034.4  820.65
  1125.7  829.68    1217  840.47  1277.8  845.92  1298.1  852.28  1328.5  863.48
#Mann= 3 , 0 , 0
       0      .1       0   388.2    .045       0   423.2      .1       0
Bank Sta=388.2,423.2
XS Rating Curve= 0 ,0
Exp/Cntr=0.3,0.1

Type RM Length L Ch R = 1 ,121735.8,1410.1,1401.4,1392.7
XS GIS Cut Line= 2
     1592114.297      389841.367     1593115.964      389549.543
#Sta/Elev= 30
    10.1  898.49      81  865.59   121.6   847.8   131.7  842.61   162.1  824.12
   182.3  809.82   222.8  779.57   243.1  766.42   283.6  746.06   324.1  728.53
   354.5  718.22   405.2   705.2   415.3  701.27   445.7  684.16   465.9  676.56
   476.1  674.54   526.7   672.4   610.5  665.95     628   665.7   645.5  666.14
   658.4  667.65   668.5  670.01   739.4  690.21   769.8  700.41   820.5  720.62
   850.9  735.28   891.4  757.76   921.8  776.34   972.4  808.66  1043.3  843.49
#Mann= 3 , 0 , 0
       0      .1       0   610.5    .045       0   645.5      .1       0
Bank Sta=610.5,645.5
XS Rating Curve= 0 ,0
Exp/Cntr=0.3,0.1

Type RM Length L Ch R = 1 ,120334.4,1595.1,1577.8,1560.3
XS GIS Cut Line= 2
     1592666.397       391190.07      1593652.29      390590.646
#Sta/Elev= 30
    10.1   864.9    40.5   850.5      81  832.96   131.6  807.42   172.1  788.06
   313.8  724.43     415  672.95   425.1  668.45   435.2  665.96   448.1  665.61
   455.5   665.6   483.1  665.73   617.4   673.1   627.5  675.04   637.6  678.16
   738.8  712.66     749  714.81   779.3  715.74   789.5  719.37   840.1  746.09
   850.2  752.37   860.3  759.49   890.7  783.87   910.9  797.53   941.3  812.76
   981.8  830.42  1032.4  854.35    1083  883.39  1113.3  904.53  1153.8   930.8
#Mann= 3 , 0 , 0
       0      .1       0   448.1    .045       0   483.1      .1       0
Bank Sta=448.1,483.1
XS Rating Curve= 0 ,0
Exp/Cntr=0.3,0.1

Type RM Length L Ch R = 1 ,118756.6,762.2,745,727.9
XS GIS Cut Line= 4
     1592656.427      392390.892     1593247.963       392312.02
     1593503.181      391852.628     1594437.553      389093.075
#Sta/Elev= 30
    10.1   883.8      91  851.92   323.7  779.06   475.4  744.69   647.3  717.86
   748.4  693.15   829.2  664.65   872.4   663.8   889.9  663.78   907.4  665.29
  1041.4  704.47  1193.4  788.99  1213.7  795.15  1467.4  757.24    1569  755.31
  1629.9  760.53  2188.2  897.65    2310  916.78  2421.7   920.7  2584.1  944.86
  2716.1  957.37  3000.3 1013.92  3051.1 1019.45  3243.9 1088.29  3355.6 1106.48
  3416.5  1099.7    3518 1065.75  3771.8 1017.82  3913.9 1002.23  4035.7 1023.36
#Mann= 3 , 0 , 0
    10.1      .1       0   872.4    .045       0   907.4      .1       0
Bank Sta=872.4,907.4
XS Rating Curve= 0 ,0
Exp/Cntr=0.3,0.1

Type RM Length L Ch R = 1 ,118011.6,439.4,457.6,475.9
XS GIS Cut Line= 6
     1594222.621      392704.402     1594105.297      392487.415
     1593914.535      391194.473     1595382.226      388944.602
     1603675.704      385024.638      1605755.63      384985.746
#Sta/Elev= 30
       0  767.91    69.1  788.56   492.6  663.84     500  663.76   527.6  664.15
    1565  786.11  2538.2  803.73    2893  978.22  3318.7 1068.25  3886.4  797.91
  4271.6  877.16  4749.1  783.34  5185.9   991.4    5511  973.08  5968.1 1124.72
  6394.8 1044.99  6872.2  851.98  7430.9 1075.66  8233.5 1235.33 10143.3  841.19
   10702  877.88 11240.4 1049.02 12246.1 1223.92 12896.3  997.76 13190.9 1014.03
 13840.6  898.09 14185.6  928.19 14408.8 1004.68 15251.1  714.23 15504.8  703.73
#Mann= 3 , 0 , 0
       0      .1       0   492.6    .045       0   527.6      .1       0
Bank Sta=492.6,527.6
XS Rating Curve= 0 ,0
Exp/Cntr=0.3,0.1

Type RM Length L Ch R = 1 ,117554  ,997.7,1072.4,1147
XS GIS Cut Line= 6
     1594377.908      392657.079      1594705.13      392126.241
     1596888.442      390748.505     1599004.502       391573.66
     1603604.313      390884.151     1605918.844      390356.973
#Sta/Elev= 30
       0  738.33   264.1  665.02   271.6  663.71   299.1  663.72   533.1  691.44
  1406.2 1014.43  2341.3  814.43  2971.5  936.01  3438.5  882.73    3692  973.53
  4148.2   895.4  4655.2 1071.55  5212.9  901.14  5385.3  976.76  5486.7  966.96
  6136.6  703.59    6360  730.62  7020.1 1061.05    7731 1204.79  8279.4 1022.08
  8868.4 1080.19  9366.1  874.53  9833.2 1020.98 10249.4 1057.94 10756.7  828.74
 11172.6  934.15 11334.9  903.28   11690 1037.62 12278.3  825.04 12501.5  939.22
#Mann= 3 , 0 , 0
       0      .1       0   264.1    .045       0   299.1      .1       0
Bank Sta=264.1,299.1
XS Rating Curve= 0 ,0
Exp/Cntr=0.3,0.1

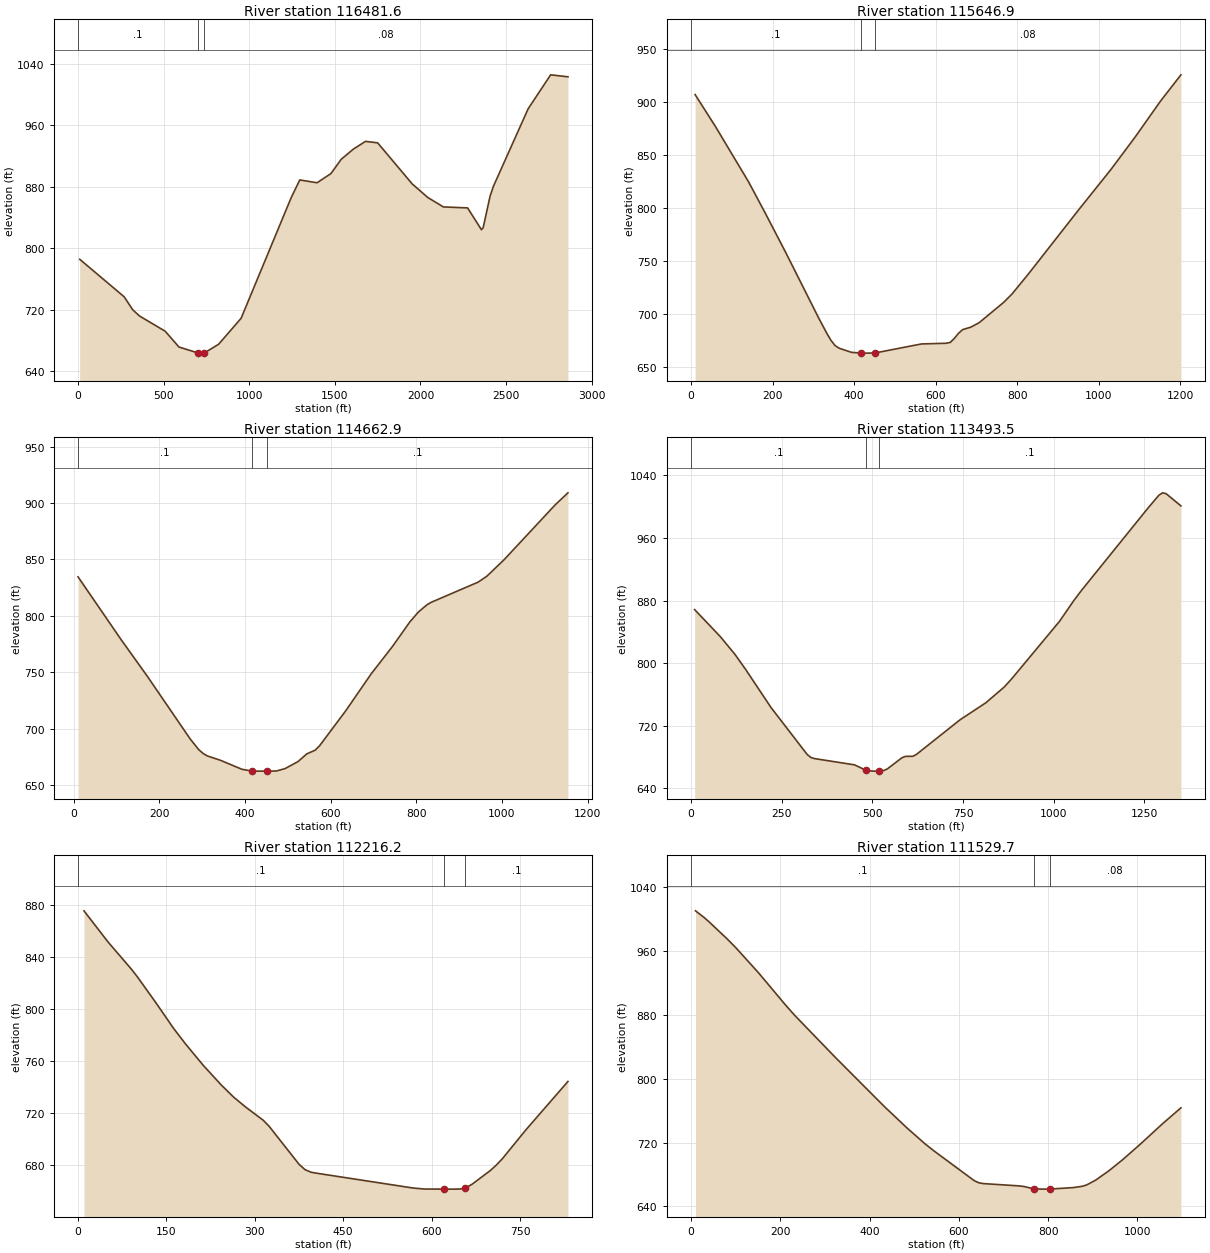
Type RM Length L Ch R = 1 ,116481.6,850.7,834.7,818.7
XS GIS Cut Line= 4
     1593994.579      392729.979     1594501.217      392778.925
     1594772.266      393516.779     1596319.042      393762.524
#Sta/Elev= 30
      10  785.45   269.5  736.64   319.4   719.8   359.3  711.66     509  691.88
   589.6  671.32   703.1  663.45   710.6   663.4   738.1  663.59   821.4  675.02
   952.4  708.71  1244.7  865.52  1295.1  888.65  1396.1  884.97  1476.9  896.91
  1537.6  915.65  1608.3  928.79    1679  938.81  1749.8  936.91  1951.8  883.45
  2042.8  865.81  2133.7  853.53  2275.2  852.29    2356  823.94  2366.1  826.47
  2406.5  867.62  2426.7  880.77  2628.8  981.17  2760.2 1025.36  2861.2 1022.78
#Mann= 3 , 0 , 0
       0      .1       0   703.1    .045       0   738.1     .08       0
Bank Sta=703.1,738.1
XS Rating Curve= 0 ,0
Exp/Cntr=0.3,0.1

Type RM Length L Ch R = 1 ,115646.9,979.8,984,988.2
XS GIS Cut Line= 2
     1593466.554      392871.704     1594365.689      393668.306
#Sta/Elev= 30
    10.1   906.8    60.6  876.29   141.3  824.47   181.7  795.38   232.2  758.07
   312.9   696.4   333.1  681.82   343.2  675.21   353.3  670.33   363.4   667.8
   393.7  663.92   416.6  663.27   434.1   663.2   451.6  663.39   565.3  671.86
   625.9   672.5     636  673.37   646.1  677.23   656.1  681.95   666.2  685.36
   686.4  687.72   706.6  691.89   767.2   711.2   787.4  719.04   827.8  738.01
   948.9  797.41  1029.6  836.17  1090.2  867.39  1150.8  900.42  1201.3  925.41
#Mann= 3 , 0 , 0
       0      .1       0   416.6    .045       0   451.6     .08       0
Bank Sta=416.6,451.6
XS Rating Curve= 0 ,0
Exp/Cntr=0.3,0.1

Type RM Length L Ch R = 1 ,114662.9,1116.6,1169.4,1222.3
XS GIS Cut Line= 3
     1592871.463      393571.989     1593328.298      394095.826
     1593446.038      394539.407
#Sta/Elev= 30
    10.1  834.59   110.8  778.88   171.2  746.84     272  690.89   292.1  681.36
   302.2  678.01   312.3   675.8   342.5  672.01   392.9     664   415.7  662.47
   433.2  662.38   450.7   662.4   473.4   662.5   493.6  664.63   523.8  670.85
     544  677.61   564.1  681.03   574.2  684.91   634.6  715.56   695.1  748.87
   744.9  773.18   784.8  794.62   804.8   803.4   824.8  809.82   834.7  812.02
   944.5  829.92   964.4  835.06  1004.3  849.53  1124.1  898.35    1154  909.06
#Mann= 3 , 0 , 0
    10.1      .1       0   415.7    .045       0   450.7      .1       0
Bank Sta=415.7,450.7
XS Rating Curve= 0 ,0
Exp/Cntr=0.3,0.1

Type RM Length L Ch R = 1 ,113493.5,1267.5,1277.3,1287.2
XS GIS Cut Line= 3
     1592594.208      393588.196     1592028.568      394036.383
     1591770.772      394610.393
#Sta/Elev= 30
      10  868.37    80.2   834.2   120.3  811.73   150.3  792.25   220.5  743.39
   320.7  683.18   330.8  679.47   340.8   678.1     451  670.11   483.7  662.91
   501.2   662.1   518.7  662.13   531.2  662.84   541.3  664.89   581.4  679.12
   591.4  680.95   611.4  681.03   621.4  683.37     742  727.72     813  749.39
   863.8  769.55   884.1  779.89    1016  853.33  1056.6  880.57  1076.9  892.98
  1259.6  997.76    1290 1014.37  1300.2 1017.51  1310.3 1016.38  1350.9 1000.83
#Mann= 3 , 0 , 0
       0      .1       0   483.7    .045       0   518.7      .1       0
Bank Sta=483.7,518.7
XS Rating Curve= 0 ,0
Exp/Cntr=0.3,0.1

Type RM Length L Ch R = 1 ,112216.2,693,686.4,679.9
XS GIS Cut Line= 2
       1592132.8      392594.394      1591357.13      392893.694
#Sta/Elev= 30
    10.1  875.55    50.7  851.74    91.3  830.33   101.4  824.41   131.8  805.14
   162.2  785.19   182.5  773.22   212.9  756.61   243.3  741.62   263.6  732.59
   283.9  724.96   314.3  714.62   324.5  709.86   375.1  680.77   385.3  676.63
   395.4  674.68   405.6  673.87   567.8  662.59   588.1  661.75   621.3   661.7
   638.8  661.69   648.9  661.78   656.3  662.58     659  662.87   669.2  665.59
   699.6  675.96   709.7  680.09   719.9  684.93   760.4  707.43   831.4  744.42
#Mann= 3 , 0 , 0
       0      .1       0   621.3    .045       0   656.3      .1       0
Bank Sta=621.3,656.3
XS Rating Curve= 0 ,0
Exp/Cntr=0.3,0.1

Type RM Length L Ch R = 1 ,111529.7,934.3,883.4,832.6
XS GIS Cut Line= 3
     1591962.433      391643.184     1591709.859      391944.663
     1591112.629      392317.932
#Sta/Elev= 30
    10.1 1010.64    30.3 1001.87    40.3  996.89    80.7   975.6   100.8  964.17
   151.3  932.87   211.8  892.48   231.9  879.78   322.7  827.15   433.5  764.96
   483.8  738.33   524.1  718.45   544.2  709.53   634.8  672.06   644.8  669.49
   654.9  668.47   735.4  665.58   745.4  664.87   768.2  661.89   785.7  661.53
   803.2  661.58   856.1  663.44   876.2  665.07   886.3  666.76   906.4  672.73
   936.6  684.72   966.8  698.32    1007  718.12  1057.3  743.99  1097.6   763.5
#Mann= 3 , 0 , 0
       0      .1       0   768.2    .045       0   803.2     .08       0
Bank Sta=768.2,803.2
XS Rating Curve= 0 ,0
Exp/Cntr=0.3,0.1

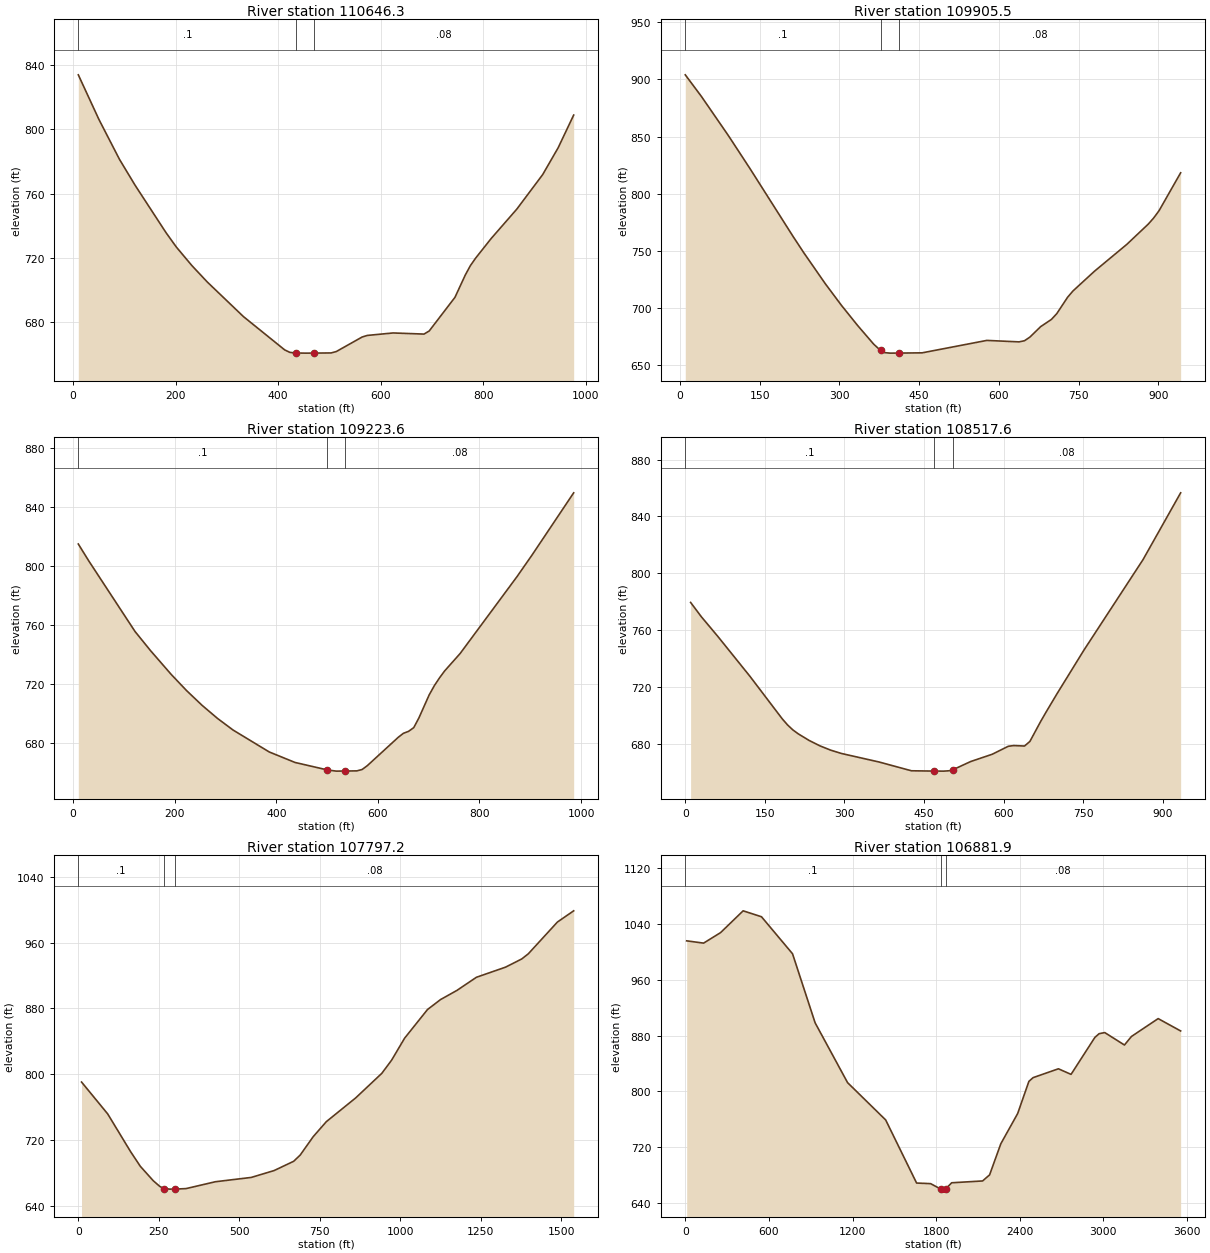
Type RM Length L Ch R = 1 ,110646.3,758.8,740.8,722.8
XS GIS Cut Line= 2
     1590410.672      391497.669      1590915.45      392333.706
#Sta/Elev= 30
    10.1  834.01    50.3  806.24    90.6  781.27   120.8  765.29   181.2  735.73
   201.4  726.74   231.6  715.24   261.8  704.96   332.2  683.46   412.8  662.68
   422.9  661.15   435.6  660.73   453.1  660.68   470.6   660.7   503.4   660.8
   513.5  661.67   563.8   670.7   573.9   671.7   624.2  673.24   684.6  672.54
   694.7  674.46     745  695.44   765.2  709.37   775.2  715.24   785.3  719.84
   815.5  732.01   865.9  750.46   916.2  771.91   946.4  788.63   976.6  808.94
#Mann= 3 , 0 , 0
    10.1      .1       0   435.6    .045       0   470.6     .08       0
Bank Sta=435.6,470.6
XS Rating Curve= 0 ,0
Exp/Cntr=0.3,0.1

Type RM Length L Ch R = 1 ,109905.5,691.8,681.9,672
XS GIS Cut Line= 2
     1589740.265      392175.963     1590576.302      392609.756
#Sta/Elev= 30
    10.1  904.03    40.5  885.09    91.1  850.96   131.7  822.12   212.7  762.82
   232.9  748.54   273.4  721.41   303.8  702.48   334.2  684.88   364.6  668.46
   377.5  662.98   384.9   661.1     395  660.66   412.5   660.7   455.7  660.92
   577.3  671.78     638   670.5   648.2  671.49   658.3  674.66   678.6  683.83
   698.8  690.13   708.9  695.19   729.2  709.49   739.3  714.99   779.8  732.28
   840.6  755.75   881.1  773.53   891.2  778.85   901.4  785.31   941.9  818.35
#Mann= 3 , 0 , 0
    10.1      .1       0   377.5    .045       0   412.5     .08       0
Bank Sta=377.5,412.5
XS Rating Curve= 0 ,0
Exp/Cntr=0.3,0.1

Type RM Length L Ch R = 1 ,109223.6,720.4,706.1,691.7
XS GIS Cut Line= 2
     1589543.086      392941.017     1590513.205      393114.534
#Sta/Elev= 30
    10.2  814.71    30.5   803.4   121.9  755.35   152.4  742.38     193  726.28
   223.5  715.22     254  705.24   284.5  696.33     315  688.49   386.1  673.64
   436.9  666.52   500.7  661.44   518.2  660.64   535.7   660.7   558.8  660.82
     569  661.74   579.1  664.31   640.1  683.58   650.2  686.28   660.4  687.62
   670.6  690.13   680.7  696.67     701  712.34   711.2  718.63   721.4  723.92
   731.5  728.63     762  740.44   873.8  792.51   904.2  807.56   985.5  849.42
#Mann= 3 , 0 , 0
    10.2      .1       0   500.7    .045       0   535.7     .08       0
Bank Sta=500.7,535.7
XS Rating Curve= 0 ,0
Exp/Cntr=0.3,0.1

Type RM Length L Ch R = 1 ,108517.6,718.3,720.4,722.5
XS GIS Cut Line= 2
     1589511.537      393832.265      1590418.56      393611.424
#Sta/Elev= 30
    10.1  779.35    30.4  769.22    60.9  755.64   121.8  727.37   182.6  697.45
   192.8  693.07   202.9  689.55   213.1  686.77   233.4  682.18   253.7  678.38
     274  675.34   294.3     673   365.3  666.99   426.2  660.81   469.6   660.6
   487.1  660.57   497.2  660.82   504.6  661.59   537.8  667.32   578.4  672.45
   608.8  678.08     619  678.57   639.3  678.24   649.4  681.47   669.7  695.54
   679.8  702.07   700.1   714.8   750.9  745.59   862.5  809.44   933.5  856.55
#Mann= 3 , 0 , 0
       0      .1       0   469.6    .045       0   504.6     .08       0
Bank Sta=469.6,504.6
XS Rating Curve= 0 ,0
Exp/Cntr=0.3,0.1

Type RM Length L Ch R = 1 ,107797.2,868.2,915.3,962.4
XS GIS Cut Line= 3
     1589819.136      394463.236      1591025.87      394195.073
     1591309.807      394297.606
#Sta/Elev= 30
    10.1  790.56    91.2   751.9   162.1  706.19   192.5  688.24     233  670.59
   253.3  663.71   266.2  661.22   283.7  660.49   301.2  660.54   334.4  661.12
   425.6  669.46     537   674.7     608  683.05   668.7  694.31     689   701.9
   729.5  724.29   770.1  742.45   861.3  771.32   942.3  801.13   972.7  817.09
  1013.3  843.95  1084.2  878.65  1124.7  890.77  1175.4  901.86  1236.2  917.87
  1326.7  930.17    1377  940.14  1397.2  946.36  1487.7  984.99  1538.1  998.59
#Mann= 3 , 0 , 0
       0      .1       0   266.2    .045       0   301.2     .08       0
Bank Sta=266.2,301.2
XS Rating Curve= 0 ,0
Exp/Cntr=0.3,0.1

Type RM Length L Ch R = 1 ,106881.9,2187.9,2131,2074.2
XS GIS Cut Line= 4
     1588555.112      394148.985     1589914.421      394755.761
     1590237.155      395677.857     1591325.582      395646.309
#Sta/Elev= 30
    10.1 1015.93   131.6 1012.67   253.2 1027.74   415.2 1059.05   546.8 1050.54
   769.6  997.39   931.6  898.26  1164.5  812.33    1438  758.73  1659.8  668.14
  1760.5  667.25  1833.7  659.41  1841.1   659.4  1868.7  659.76  1911.6  668.52
  2133.2  671.13  2183.5  679.84  2264.1  724.54    2385  767.95  2465.5  814.11
  2495.8  819.51  2677.3   832.2    2768  824.18  2939.4  877.37  2969.6  882.63
    3010  884.21  3151.1  866.36  3201.5  878.62  3393.1  904.27  3554.4  886.54
#Mann= 3 , 0 , 0
       0      .1       0  1833.7    .045       0  1868.7     .08       0
Bank Sta=1833.7,1868.7
XS Rating Curve= 0 ,0
Exp/Cntr=0.3,0.1