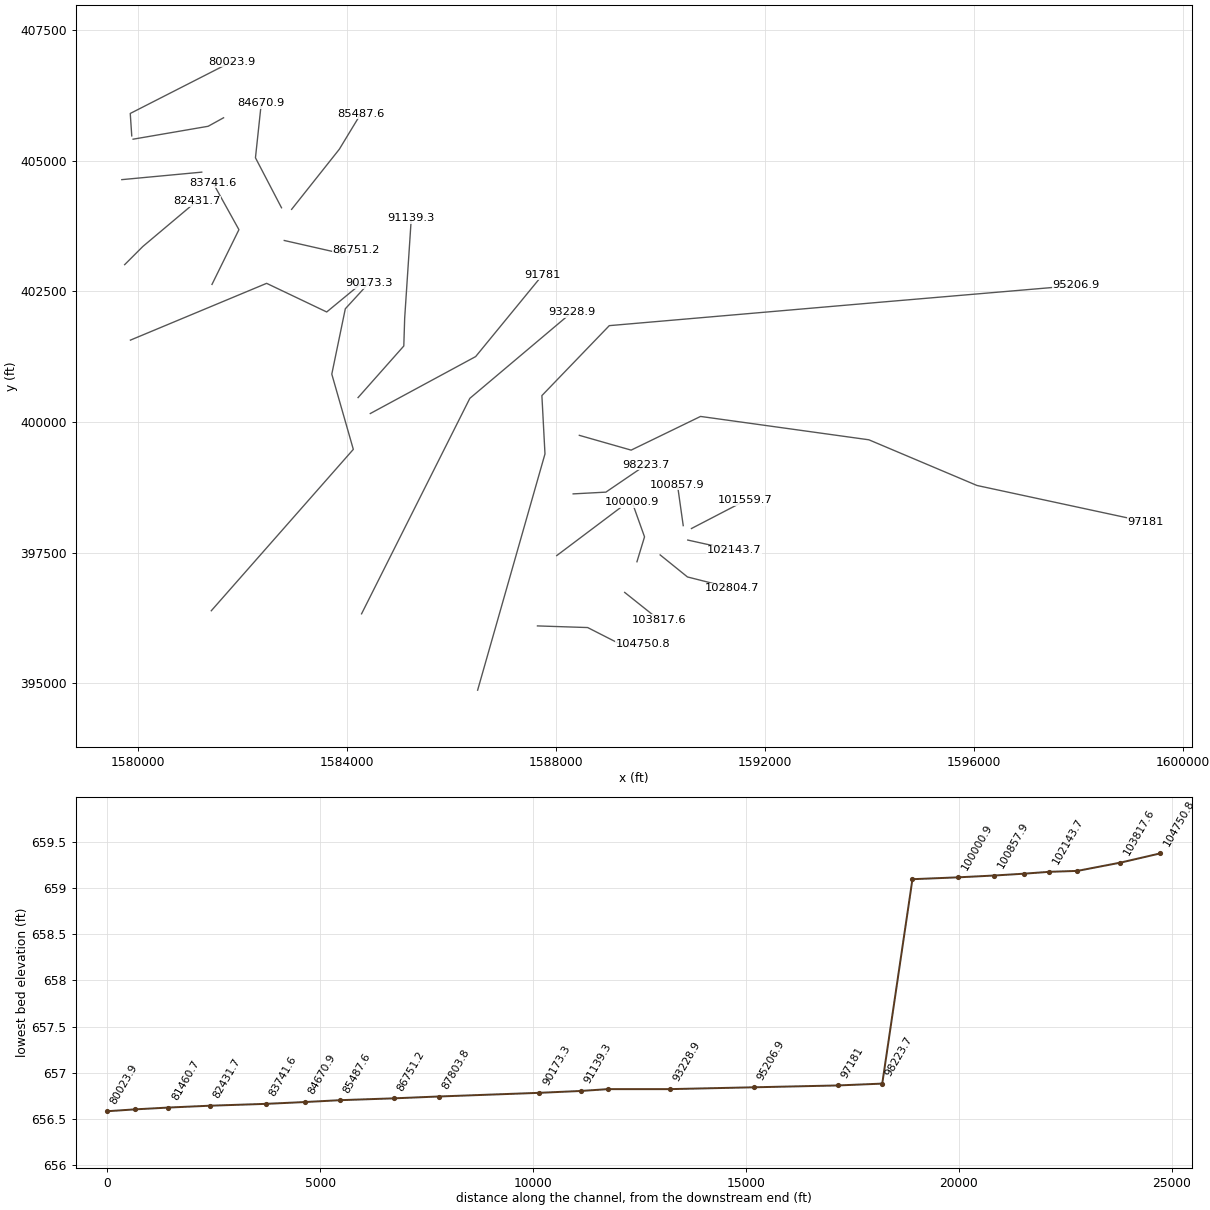
HEC-RAS study EFTWELVECR.prj: EFTWELVECR

--- EFTWELVECR.g01 (geometry) --- (continued)

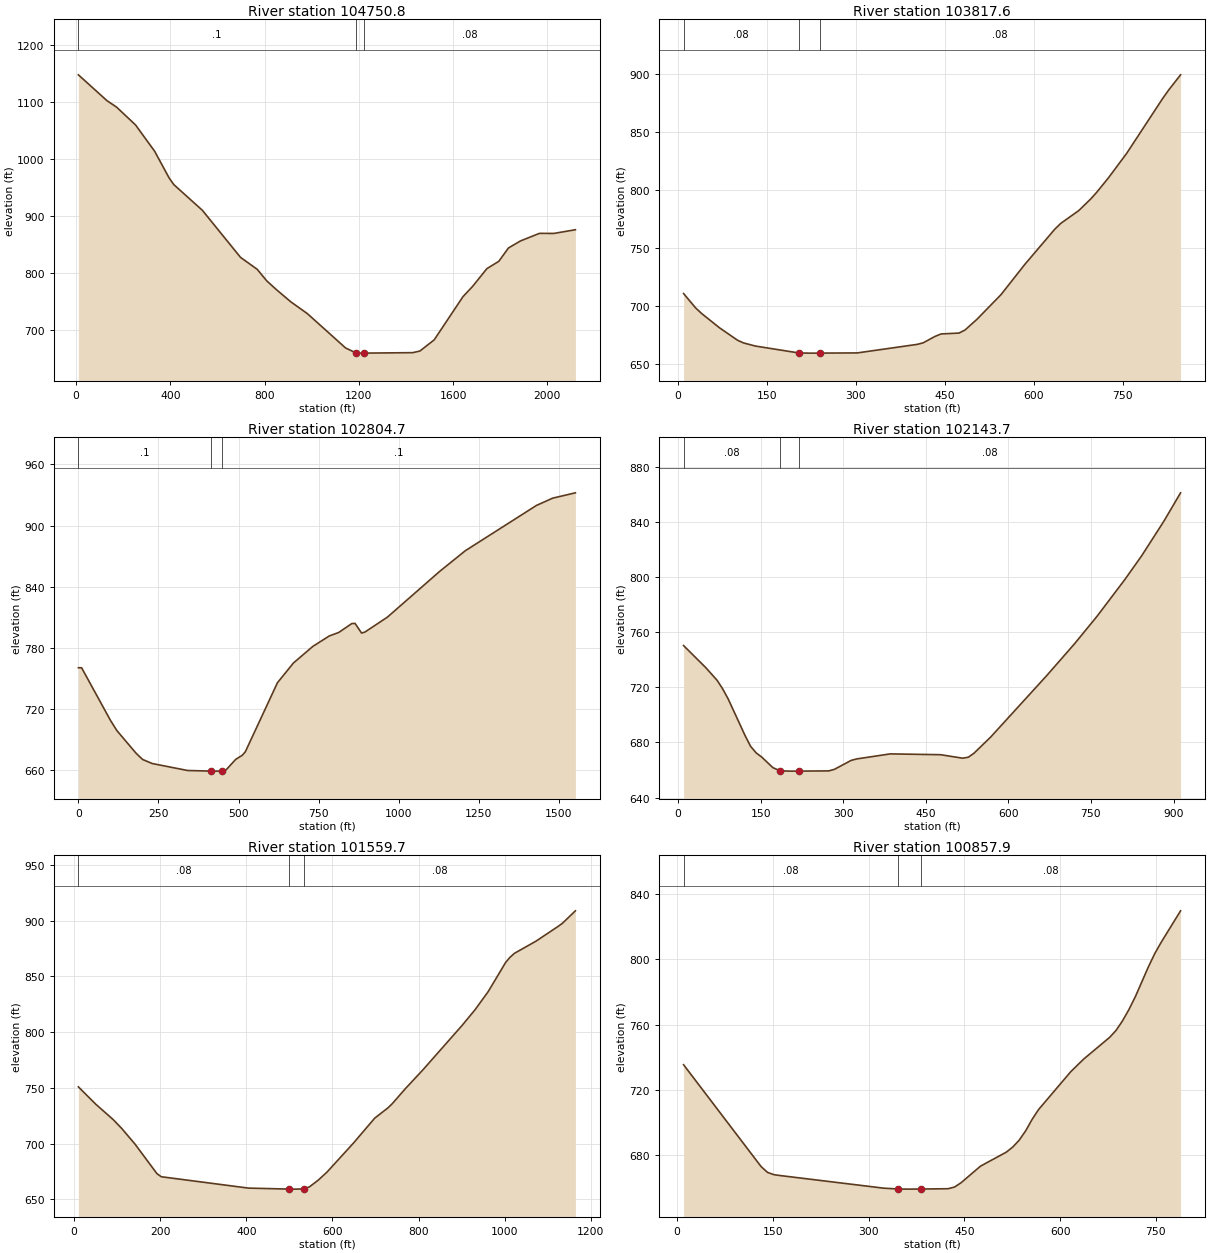
Type RM Length L Ch R = 1 ,104750.8,939.7,933.2,926.7
XS GIS Cut Line= 4
     1587645.439      396101.616     1588606.038      396070.271
     1589330.133      395701.519      1589669.28      395764.616
#Sta/Elev= 30
    10.1 1148.29   131.5 1102.84     172 1091.64   252.9 1060.12   333.9 1013.87
   394.6  967.49   414.8  955.51   536.2  910.27   698.1  827.56   768.9  806.62
   809.4  786.28   849.8  771.13   910.5  749.77   981.4  728.85  1143.9  668.41
  1187.4  659.84  1204.9  659.38  1222.4   659.4  1428.3   660.2  1458.8  662.99
  1519.8  682.72  1641.6  758.47  1682.3  776.45  1743.2  807.76    1794  820.73
  1834.6  844.03  1885.3   856.4  1966.5   869.8  2027.3  869.65  2118.7  876.16
#Mann= 3 , 0 , 0
    10.1      .1       0  1187.4    .045       0  1222.4     .08       0
Bank Sta=1187.4,1222.4
XS Rating Curve= 0 ,0
Exp/Cntr=0.3,0.1

Type RM Length L Ch R = 1 ,103817.6,1013.2,1012.9,1012.6
XS GIS Cut Line= 2
     1589314.359      396742.622     1589976.879      396214.183
#Sta/Elev= 30
    10.1  710.66    30.3  698.32    40.4  693.51    70.6  681.14   100.9  670.44
     111  668.09   131.2  665.37   204.5  659.42     222  659.28   239.5   659.3
   302.7  659.46   403.6  666.81   413.6  668.12   433.8   673.7   443.9  675.81
   474.2  676.57   484.3  679.21   504.4  688.44   544.8  709.62   585.1  735.79
   635.6  766.15   645.7  771.18   675.9  782.15   696.1  792.19   706.2  797.94
   726.4  810.69   756.7  831.53   817.2  878.73   827.3  886.01   847.5  899.24
#Mann= 3 , 0 , 0
    10.1     .08       0   204.5    .045       0   239.5     .08       0
Bank Sta=204.5,239.5
XS Rating Curve= 0 ,0
Exp/Cntr=0.3,0.1

Type RM Length L Ch R = 1 ,102804.7,645.5,661,676.5
XS GIS Cut Line= 3
     1589992.654      397460.353     1590515.231      397038.513
     1591368.547      396822.527
#Sta/Elev= 30
       0  760.61      10  760.61   100.2  708.97   120.3  698.91   180.4  676.65
   200.5  670.64   230.5  666.65   340.8  659.82   413.5   659.2     431  659.19
   448.5  659.23   461.1  660.38   491.2  670.72   511.2  674.61   521.2  678.13
   621.5  745.88   671.6  765.32   732.3  781.61   782.9  791.69   813.2  795.27
   853.7  803.94   863.8  804.12   884.1  794.68   894.2  795.52     965  810.29
  1126.9  854.82  1207.8  875.34  1430.4  919.87    1481  926.99  1551.8  932.21
#Mann= 3 , 0 , 0
       0      .1       0   413.5    .045       0   448.5      .1       0
Bank Sta=413.5,448.5
XS Rating Curve= 0 ,0
Exp/Cntr=0.3,0.1

Type RM Length L Ch R = 1 ,102143.7,561.1,584,606.8
XS GIS Cut Line= 2
     1590521.092       397744.29      1591412.34      397547.112
#Sta/Elev= 30
    10.1  750.48    50.7  734.32      71  725.23    81.1  719.01    91.3  711.52
   121.7  685.12   131.8  677.24     142  672.42   152.1  669.38   172.4  661.68
   185.3  659.47   202.8  659.18   220.3   659.2   273.8  659.35     284  660.47
   314.4  666.97   324.6  668.05   385.4  671.71   476.7  671.13   517.3  668.58
   527.4  669.32   537.5  672.17     568     684   669.4  728.52   720.1  751.73
   760.7  771.58   811.4  798.39   841.8  815.56   882.4  840.86   912.8  861.55
#Mann= 3 , 0 , 0
    10.1     .08       0   185.3    .045       0   220.3     .08       0
Bank Sta=185.3,220.3
XS Rating Curve= 0 ,0
Exp/Cntr=0.3,0.1

Type RM Length L Ch R = 1 ,101559.7,661.2,701.8,742.5
XS GIS Cut Line= 2
     1590592.077      397965.131     1591625.293      398501.457
#Sta/Elev= 30
    10.1  750.92    50.6  735.29    91.1  721.49   111.4   713.3   141.7  699.49
   192.3  673.16   202.5  670.27   404.9  660.08   498.8   659.2   516.3  659.16
   533.8  659.45   546.6  661.19   566.9  667.18   587.1  674.33   647.9  700.08
   698.5  722.96   728.8  732.01     739  735.84   769.3  749.27   809.8  766.04
   900.9  805.96   931.3  820.17   961.7  836.38  1002.2  862.53  1012.3  867.14
  1022.4  870.66    1073   881.7  1123.6  894.76  1133.8  897.57  1164.1  908.83
#Mann= 3 , 0 , 0
    10.1     .08       0   498.8    .045       0   533.8     .08       0
Bank Sta=498.8,533.8
XS Rating Curve= 0 ,0
Exp/Cntr=0.3,0.1

Type RM Length L Ch R = 1 ,100857.9,850.4,857,863.5
XS GIS Cut Line= 2
     1590434.334      398020.341     1590323.914      398801.168
#Sta/Elev= 30
    10.1  735.44   131.4  673.04   141.5  669.43   151.7  667.99   161.8  667.45
   323.5  659.73   346.5  659.21     364  659.14   381.5   659.2   424.6  659.39
   434.7  660.45   444.8  663.06   475.2  673.23   515.6  681.81   525.7  684.93
   535.8  689.16     546  694.91   556.1  701.94   566.2  707.95   616.7  731.21
   636.9  738.93   677.4  752.19   687.5  756.47   697.6  762.32   707.7  769.27
   717.8  777.21     738  795.29   748.2  803.62   758.3  810.57   788.6  829.83
#Mann= 3 , 0 , 0
    10.1     .08       0   346.5    .045       0   381.5     .08       0
Bank Sta=346.5,381.5
XS Rating Curve= 0 ,0
Exp/Cntr=0.3,0.1

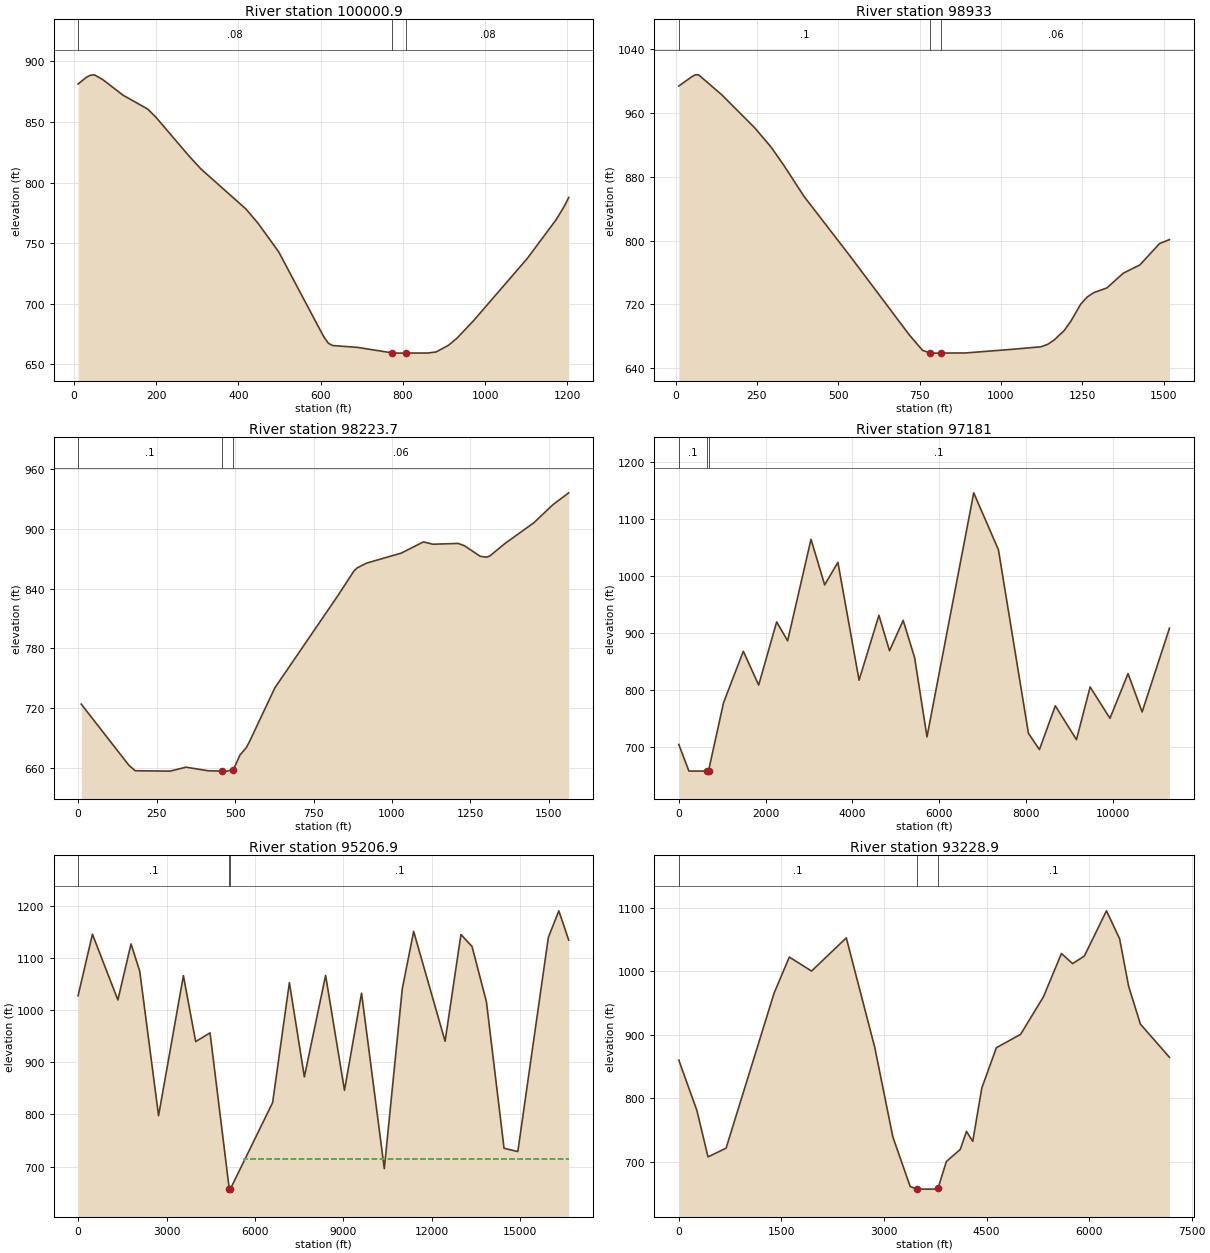
Type RM Length L Ch R = 1 ,100000.9,1110,1067.9,1025.8
XS GIS Cut Line= 3
     1589548.914      397329.151     1589693.985      397805.865
     1589456.327      398469.908
#Sta/Elev= 30
      10  881.32    29.9   886.8    39.9  888.57    49.8  888.91    69.8  885.03
   119.6  872.06   179.4  860.64   199.3  853.95     279  822.24   308.9  811.19
   418.6  778.05   448.5  766.08   498.3  742.61   599.1  678.09   609.1  671.92
   619.2  667.21   629.3  665.39   689.7  663.87     773  659.39   790.5  659.12
     808   659.2     861   659.2   881.2   660.1   911.4  665.68   931.5  671.37
   971.9  685.81  1102.8  737.29  1173.4  769.47  1193.5  780.78  1203.6  787.63
#Mann= 3 , 0 , 0
      10     .08       0     773    .045       0     808     .08       0
Bank Sta=773,808
XS Rating Curve= 0 ,0
Exp/Cntr=0.3,0.1

Type RM Length L Ch R = 1 ,98933   ,728.9,709.3,689.7
XS GIS Cut Line= 2
     1588014.362      397447.102       1589227.6      398359.488
#Sta/Elev= 30
    10.1  993.49    50.6 1005.29    60.7 1007.48    70.8 1007.47   141.7  982.64
   242.9  941.32   293.5   917.1     334  893.49   394.7  855.41   536.4  780.56
   718.5   681.9     759  662.58     782  659.45   799.5   659.1     817   659.2
   890.6   659.3  1032.3  663.79  1123.3  667.06  1143.6  670.11  1163.8  675.56
  1194.2  687.27  1214.4  698.74  1244.8  720.12    1265  729.29  1285.3  734.77
  1325.7  740.74  1376.3  759.23  1426.9  769.44  1487.7  796.29    1518  801.22
#Mann= 3 , 0 , 0
    10.1      .1       0     782    .045       0     817     .06       0
Bank Sta=782,817
XS Rating Curve= 0 ,0
Exp/Cntr=0.3,0.1

Type RM Length L Ch R = 1 ,98223.7 ,1053.5,1042.7,1032
XS GIS Cut Line= 3
     1588328.465      398627.651     1588954.584      398661.193
     1589728.233       399188.08
#Sta/Elev= 30
    10.1  724.11   161.8  662.83     182  657.25   293.3   656.9   343.8  660.85
   414.6  657.23   457.8   656.9   475.3  656.88   492.8  658.39   495.5   658.9
   515.8  673.06     536  680.49   546.1  686.51     627  740.49   828.3  833.27
   878.6  857.61   888.7  860.73   918.9  865.61  1029.6  875.67  1100.1  886.89
  1130.3  884.57  1210.8  885.38  1230.9  883.04  1281.2  872.46  1301.4  871.56
  1311.4  872.74  1361.7  885.72  1452.3  906.18  1512.7  924.24    1563  936.15
#Mann= 3 , 0 , 0
       0      .1       0   457.8    .045       0   492.8     .06       0
Bank Sta=457.8,492.8
XS Rating Curve= 0 ,0
Exp/Cntr=0.3,0.1

Type RM Length L Ch R = 1 ,97181   ,1913.4,1974.1,2034.8
XS GIS Cut Line= 6
     1588446.772      399747.626     1589437.891       399464.91
     1590765.787      400109.512     1593986.367      399662.539
     1596055.072       398788.41     1599281.574      398093.877
#Sta/Elev= 30
       0  703.62   232.4  656.98   649.4  656.91     677  656.86   684.4  657.47
  1030.7  777.04  1485.6   867.2  1839.5  807.87    2254  918.65  2506.7  885.53
  3045.3 1063.61  3360.2  983.61  3665.1 1023.22  4152.8  816.49    4610  930.27
  4853.9   868.1  5168.9   921.4    5433  855.91  5717.5  716.99  6794.7 1145.16
  7363.8 1045.23  8054.8  723.23  8308.6  694.61  8674.2  771.47  9161.7   712.1
  9476.5  804.54  9933.5  749.52 10349.8  828.03 10674.8   760.7 11304.4  907.75
#Mann= 3 , 0 , 0
       0      .1       0   649.4    .045       0   684.4      .1       0
Bank Sta=649.4,684.4
XS Rating Curve= 0 ,0
Exp/Cntr=0.3,0.1

Type RM Length L Ch R = 1 ,95206.9 ,1997.5,1978,1958.5
XS GIS Cut Line= 6
     1586500.852      394872.305     1587789.352      399391.887
     1587730.296      400508.043     1589019.589      401846.478
     1594160.052      402291.035     1597953.499      402615.211
#Sta/Elev= 30
       0 1027.71   487.2 1145.79    1350 1019.59  1796.6 1127.13    2091 1074.94
  2730.5  797.78    3573 1066.28  3989.1  939.79  4476.4  956.58  5129.3  656.91
    5140  656.84  5164.3  656.91  6599.3  822.79    7168  1052.9  7675.8  872.18
  8396.9 1066.73  9036.8  846.27  9615.7 1032.74 10387.7  696.22 10997.1 1040.78
   11383 1151.09 12449.5  940.43 12987.7 1145.16 13363.4 1122.21 13850.7 1016.34
 14449.7  735.21 14916.8  728.89 15952.3  1139.6 16307.7 1190.58 16642.7 1134.44
#Mann= 3 , 0 , 0
       0      .1       0  5129.3    .045       0  5164.3      .1       0
#XS Ineff= 2 , 0
                         5626.17          714.71
Permanent Ineff=
       F       F
Bank Sta=5129.3,5164.3
XS Rating Curve= 0 ,0
Exp/Cntr=0.3,0.1

Type RM Length L Ch R = 1 ,93228.9 ,1463.3,1447.9,1432.5
XS GIS Cut Line= 3
     1584280.304        396333.2      1586351.67      400455.696
     1588310.257      402106.949
#Sta/Elev= 30
       0  859.93   264.2  780.71   426.8   707.6     691  721.31  1392.2  965.19
  1615.8 1022.24    1941 1000.24  2449.1 1052.48  2865.7  879.83  3129.9  739.06
    3384  660.85    3490   656.9    3760  656.82    3790 657.947  3912.4  700.24
  4115.7  719.36  4207.1  747.74  4298.6     732  4430.7  815.96    4644  879.49
  4998.4   900.6  5332.5  959.72  5595.8 1027.91  5757.8 1011.92    5930 1023.76
    6254 1095.08  6446.4 1051.11    6578  976.39  6750.1  916.75  7175.4  864.36
#Mann= 3 , 0 , 0
       0      .1       0    3490    .045       0    3790      .1       0
Bank Sta=3490,3790
XS Rating Curve= 0 ,0
Exp/Cntr=0.3,0.1

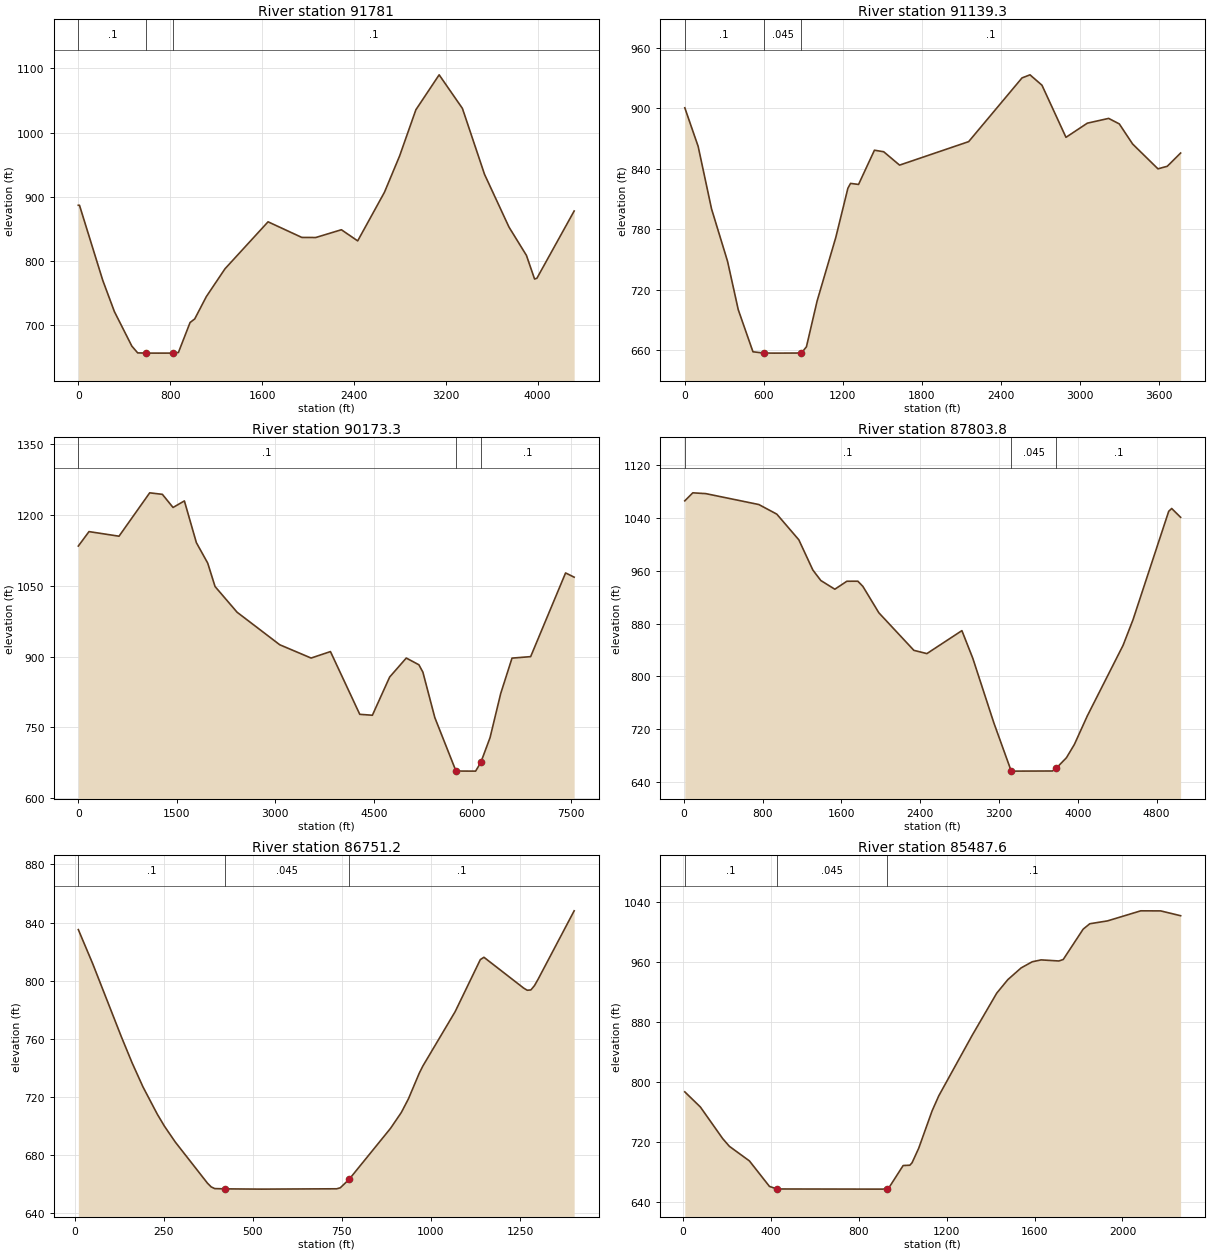
Type RM Length L Ch R = 1 ,91781   ,630.3,641.7,653.2
XS GIS Cut Line= 3
     1584447.377      400165.092     1586462.851      401254.537
     1587747.689      402822.563
#Sta/Elev= 30
       0  886.92    10.1  886.92   212.9     770   314.3  721.38   466.3  667.68
     517  657.17     591   656.9   699.5  656.82     824   656.9   871.8  657.85
   973.2  704.46  1013.8  710.07  1115.1  744.88  1277.3  788.06  1652.4  861.18
  1946.4   836.9  2068.1  836.75  2291.1  848.84    2433   831.5  2666.1  907.17
  2797.9  963.57  2939.8 1035.54  3142.5 1089.94  3345.2 1037.66  3537.8  935.05
  3750.7  853.01  3902.7  808.93  3973.6  772.14  3993.9  773.36  4318.3     878
#Mann= 3 , 0 , 0
       0      .1       0     591    .045       0     824      .1       0
Bank Sta=591,824
XS Rating Curve= 0 ,0
Exp/Cntr=0.3,0.1

Type RM Length L Ch R = 1 ,91139.3 ,948.9,966,983.1
XS GIS Cut Line= 4
     1584213.405      400470.272     1585088.256      401457.023
     1585105.053      401988.944     1585231.284      403896.818
#Sta/Elev= 30
       0  900.57   101.4  862.21   202.9  800.17   324.6  747.97   405.8  699.92
   517.3  658.13     598   656.9   679.7   656.8     885   656.9   923.1  663.06
  1004.3  708.67  1146.3   771.9  1237.6  820.56  1257.9  825.45  1318.7  824.41
  1439.2   858.4  1509.5   856.9    1630   843.6  2154.4  866.94  2559.1  930.23
  2619.8  933.32  2710.8     923  2892.9  871.22  3054.8  885.27  3216.7  890.03
  3297.6  884.55  3398.8  864.57    3591  839.92  3661.8  842.46    3763  855.62
#Mann= 3 , 0 , 0
       0      .1       0     598    .045       0     885      .1       0
Bank Sta=598,885
XS Rating Curve= 0 ,0
Exp/Cntr=0.3,0.1

Type RM Length L Ch R = 1 ,90173.3 ,2431.2,2369.5,2307
XS GIS Cut Line= 5
      1581405.17       396391.75     1584122.416      399479.406
      1583710.57      400918.776      1583969.26      402169.112
     1584416.858      402657.401
#Sta/Elev= 30
       0 1134.47   162.5 1165.08   619.5 1155.33  1086.7 1247.39  1279.6 1244.18
  1442.1 1216.32  1614.7  1230.2  1797.5 1141.63  1970.2 1098.17  2081.9 1048.48
    2417  994.02    3067  924.95  3544.3  896.76  3838.8  910.48    4285  777.36
  4477.2  775.36  4740.2  856.43  4993.1  896.77  5185.3  882.48    5246  866.92
  5428.1  770.33    5750 656.966  6048.7  656.78    6128  675.15  6268.8  727.83
    6431  821.45  6603.2  896.59    6887  899.78  7418.9 1077.37  7549.4  1068.4
#Mann= 3 , 0 , 0
       0      .1       0    5750    .045       0    6128      .1       0
Bank Sta=5750,6128
XS Rating Curve= 0 ,0
Exp/Cntr=0.3,0.1

Type RM Length L Ch R = 1 ,87803.8 ,1045.5,1052.6,1059.9
XS GIS Cut Line= 4
     1579857.953      401569.625     1582463.643      402655.919
     1583613.216      402108.075     1584343.873      402710.494
#Sta/Elev= 30
    10.2  1065.7    91.4 1077.83   223.4 1076.62   761.6 1060.13   944.4 1045.56
  1167.8 1006.76    1310  961.05  1391.2  945.13  1533.4  931.98  1655.2  944.04
  1766.9  944.09  1817.7  936.32  1980.2  896.32  2335.6   839.5  2467.6  834.56
  2823.1  869.32  2934.2  827.32  3146.5   730.2    3323 657.171  3328.4  656.74
  3742.8  656.95    3779 660.855  3884.3  676.98  3965.1  697.15  4096.5  740.38
  4459.2  847.05  4559.9  885.68  4922.6 1049.87  4952.8 1054.12  5043.5 1040.77
#Mann= 3 , 0 , 0
    10.2      .1       0    3323    .045       0    3779      .1       0
Bank Sta=3323,3779
XS Rating Curve= 0 ,0
Exp/Cntr=0.3,0.1

Type RM Length L Ch R = 1 ,86751.2 ,1226.1,1263.6,1301.2
XS GIS Cut Line= 3
     1582801.264      403475.783     1583862.143      403234.674
     1584172.021      403285.092
#Sta/Elev= 30
    10.1  835.11    50.4  811.72     131  761.38   161.2  743.45   191.4  727.08
   231.7  708.26   251.8     700   282.1  689.14   372.7  660.78   382.8  658.29
   392.9  657.09     422   656.9   523.8  656.72   735.4  656.95   745.4  657.64
     770 663.381   886.5  698.52   916.7  709.39   936.8  718.83   967.1  736.43
   977.1   741.3  1067.8   778.7  1138.6  814.53  1148.7  816.09  1260.1  794.93
  1270.2  793.43  1280.4  793.65  1290.5   796.6  1300.6  800.97  1401.9  848.03
#Mann= 3 , 0 , 0
    10.1      .1       0     422    .045       0     770      .1       0
Bank Sta=422,770
XS Rating Curve= 0 ,0
Exp/Cntr=0.3,0.1

Type RM Length L Ch R = 1 ,85487.6 ,777.5,816.7,855.8
XS GIS Cut Line= 3
     1582941.818      404071.405     1583854.803      405221.948
     1584267.374      405902.133
#Sta/Elev= 30
    10.1  786.49      81  766.28   182.3  724.15   212.7  713.84   303.9  694.36
     395  660.32     429   656.9   911.7   656.7     928 657.424     942  660.32
  1002.8   688.2  1033.2  688.59  1043.3  691.87  1073.7  711.39  1134.5  761.21
  1164.9  781.28  1316.8  862.04  1428.3  918.26  1478.8   936.3  1539.3  951.95
  1589.6  960.09  1629.9  962.62  1710.5  961.17  1730.6  963.16  1821.2 1003.65
  1851.4 1010.86    1932 1014.67    2083  1028.1  2173.7    1028  2264.3 1021.56
#Mann= 3 , 0 , 0
    10.1      .1       0     429    .045       0     928      .1       0
Bank Sta=429,928
XS Rating Curve= 0 ,0
Exp/Cntr=0.3,0.1

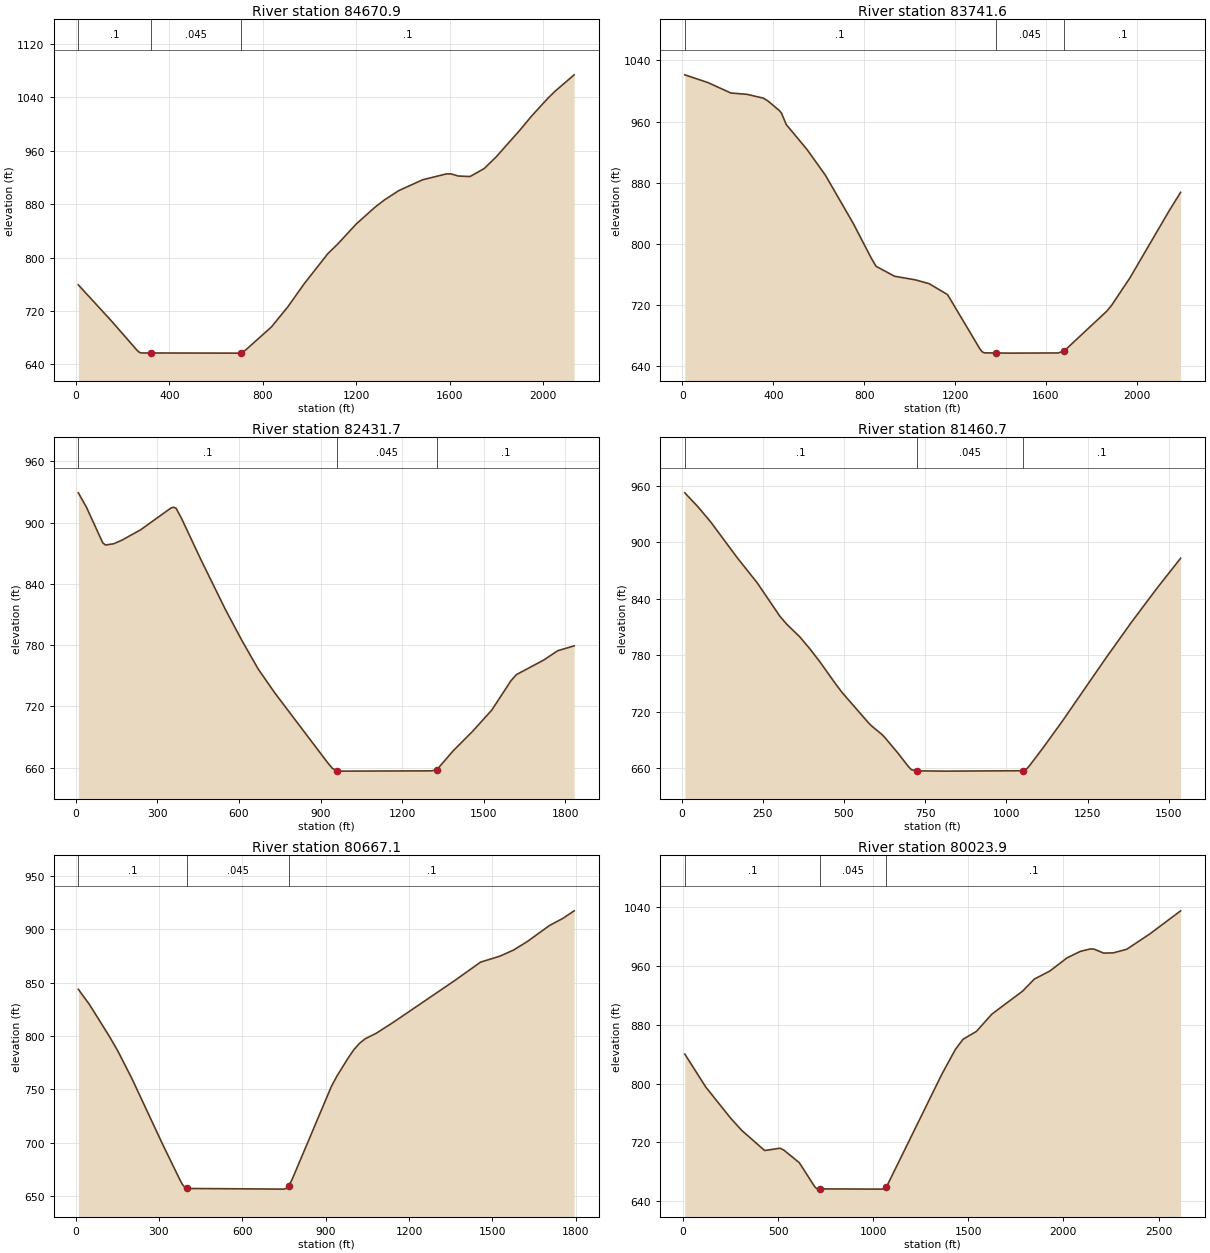
Type RM Length L Ch R = 1 ,84670.9 ,928.5,929.3,930.1
XS GIS Cut Line= 3
     1582748.537      404101.923     1582250.076      405058.156
     1582361.975      406105.943
#Sta/Elev= 30
    10.1  759.02   151.2  705.15     262  660.73   272.1  657.68   282.2  656.91
     319   656.9   695.4  656.68     706 657.024   725.6  661.15   836.5  695.96
     907  726.19   977.6  761.11  1078.4  805.99  1118.9  819.72  1199.9   850.4
    1281  875.82  1321.5  886.64  1382.3  900.44  1483.6  916.55    1585  925.34
  1605.2  925.39  1635.6  922.21  1686.3  921.42  1747.1  933.35  1797.7  950.67
  1899.1  990.64  1949.7    1012  2020.6 1039.11    2051 1049.52  2132.1 1073.89
#Mann= 3 , 0 , 0
    10.1      .1       0     319    .045       0     706      .1       0
Bank Sta=319,706
XS Rating Curve= 0 ,0
Exp/Cntr=0.3,0.1

Type RM Length L Ch R = 1 ,83741.6 ,1356.1,1309.9,1263.7
XS GIS Cut Line= 3
     1581418.492      402635.359     1581933.772      403682.741
      1581436.26      404580.039
#Sta/Elev= 30
    10.2 1021.16   111.7 1011.05   213.2  997.33   284.2  995.62   355.3  990.67
   375.6  987.08   426.3  974.43   436.5  970.65   456.8  956.09   548.1  923.49
   629.3  889.66   751.1  826.99   832.3  780.49   852.6  770.34   933.8  757.35
  1025.2  752.64  1086.1  747.62  1167.3  733.25  1309.5  662.21  1319.6  658.36
  1329.8     657    1379   656.9  1441.5  656.66  1654.9   656.9    1681 659.661
  1868.2  711.62  1888.5  718.88  1969.8  755.09  2142.5  842.94  2193.3  867.26
#Mann= 3 , 0 , 0
    10.2      .1       0    1379    .045       0    1681      .1       0
Bank Sta=1379,1681
XS Rating Curve= 0 ,0
Exp/Cntr=0.3,0.1

Type RM Length L Ch R = 1 ,82431.7 ,991.9,970.9,949.9
XS GIS Cut Line= 3
     1579747.594      403013.445     1580093.465      403359.316
     1581120.907      404223.995
#Sta/Elev= 30
      10  929.21    39.9  915.11    99.8  880.22   109.8   878.1   139.8  879.31
   169.7  882.78   239.6  893.12   349.4  914.16   359.4  915.16   369.3  914.04
   389.3  904.14   459.2  864.43   549.7  815.33   610.3  784.96   670.9  756.67
   731.5  733.41   923.3  665.91   943.5  659.35     961 657.052   973.8  656.64
    1307   656.9    1327 657.911  1387.7  676.59  1458.4  695.51  1529.1  716.36
  1599.8   745.2    1620   751.2  1720.9  765.53  1771.4  774.56    1832  779.31
#Mann= 3 , 0 , 0
      10      .1       0     961    .045       0    1327      .1       0
Bank Sta=961,1327
XS Rating Curve= 0 ,0
Exp/Cntr=0.3,0.1

Type RM Length L Ch R = 1 ,81460.7 ,791.1,793.7,796.2
XS GIS Cut Line= 2
     1579693.018      404639.954     1581222.634      404783.493
#Sta/Elev= 30
    10.1  952.48    50.5   937.7      91  921.01   171.8  883.35   232.5  857.05
   303.2  821.09   323.4  812.99   363.9  799.43   394.2  787.03   424.5  773.51
   475.1  748.98   495.3   739.8   576.1  707.78   586.2  704.34   616.6  695.66
   626.7  692.03   667.1  675.39   697.4  661.89   707.5  658.14     724   656.9
   808.6  656.62    1052 657.031  1061.3  658.55  1071.4   662.5  1111.8  680.89
  1172.5  709.88  1303.9  775.66  1384.7  814.79  1465.6  851.98  1536.3  882.95
#Mann= 3 , 0 , 0
    10.1      .1       0     724    .045       0    1052      .1       0
Bank Sta=724,1052
XS Rating Curve= 0 ,0
Exp/Cntr=0.3,0.1

Type RM Length L Ch R = 1 ,80667.1 ,633.3,643.1,653
XS GIS Cut Line= 3
     1579908.703      405413.879      1581344.82      405660.859
     1581639.828      405823.622
#Sta/Elev= 30
    10.1  843.75    50.6  829.32   121.4  799.83   151.8  786.19   202.4  760.39
   313.7  698.44   374.4  665.98   384.5  661.06   394.7  657.89     402 657.211
   748.8   656.6     759   657.3   766.3  659.38   779.2   665.6   920.9  752.95
   941.1  762.71   981.6  779.67  1001.8  787.29  1022.1   793.2  1042.3  797.43
  1082.8  802.71  1143.5  812.84  1366.1  852.25  1457.2  869.17  1526.6  874.76
  1576.1  880.51  1625.7  888.51  1704.9  903.42  1754.5  910.33  1794.1  917.24
#Mann= 3 , 0 , 0
    10.1      .1       0     402    .045       0   766.3      .1       0
Bank Sta=402,766.3
XS Rating Curve= 0 ,0
Exp/Cntr=0.3,0.1

Type RM Length L Ch R = 1 ,80023.9 ,1529.2,1583.9,1638.6
XS GIS Cut Line= 3
     1579883.328      405477.316      1579854.71      405906.129
     1581802.477      406899.412
#Sta/Elev= 30
      10  840.15   119.9  795.49   249.9  753.36   309.8   736.3   429.8  709.05
   510.7   712.2     531  709.57     612  692.48   692.9  659.87   703.1  657.43
     723 656.901  1047.2  656.58    1069 659.034    1361  812.68  1431.9  846.33
  1472.4  860.29  1543.2  871.07  1624.2  894.51  1786.2  925.83  1846.9  942.06
  1927.9   952.9    2019   970.9  2089.8  979.83  2140.4     983  2160.7  982.87
  2211.3  977.43  2261.9  977.71  2332.8   982.6  2454.2 1003.43  2616.2 1034.87
#Mann= 3 , 0 , 0
      10      .1       0     723    .045       0    1069      .1       0
Bank Sta=723,1069
XS Rating Curve= 0 ,0
Exp/Cntr=0.3,0.1