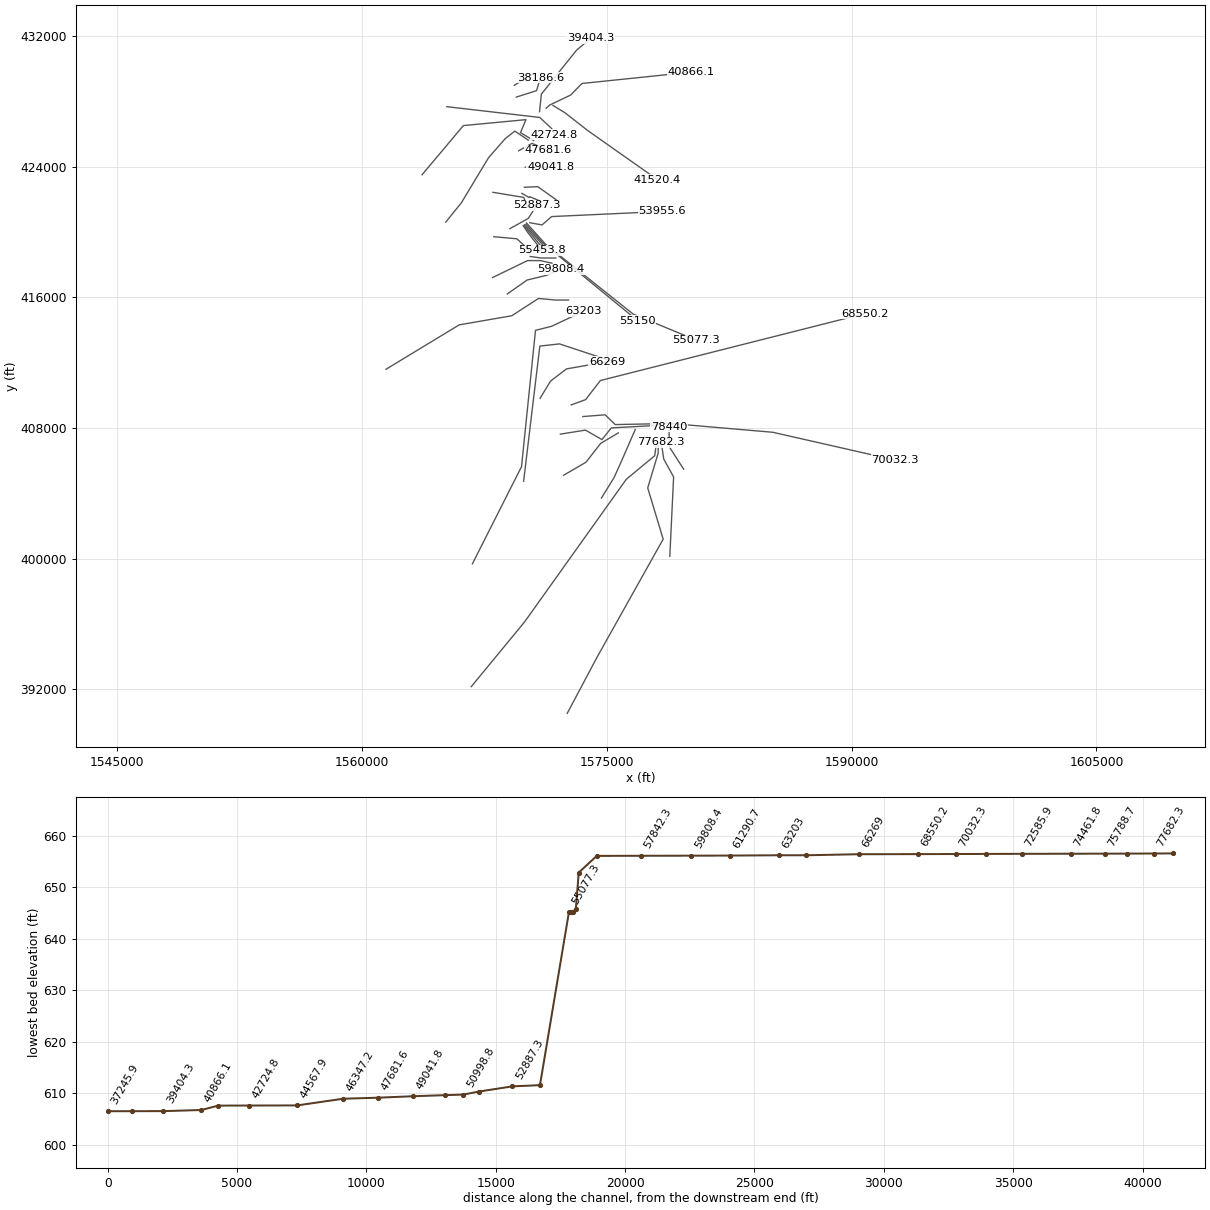
HEC-RAS study EFTWELVECR.prj: EFTWELVECR

--- EFTWELVECR.g01 (geometry) --- (continued)

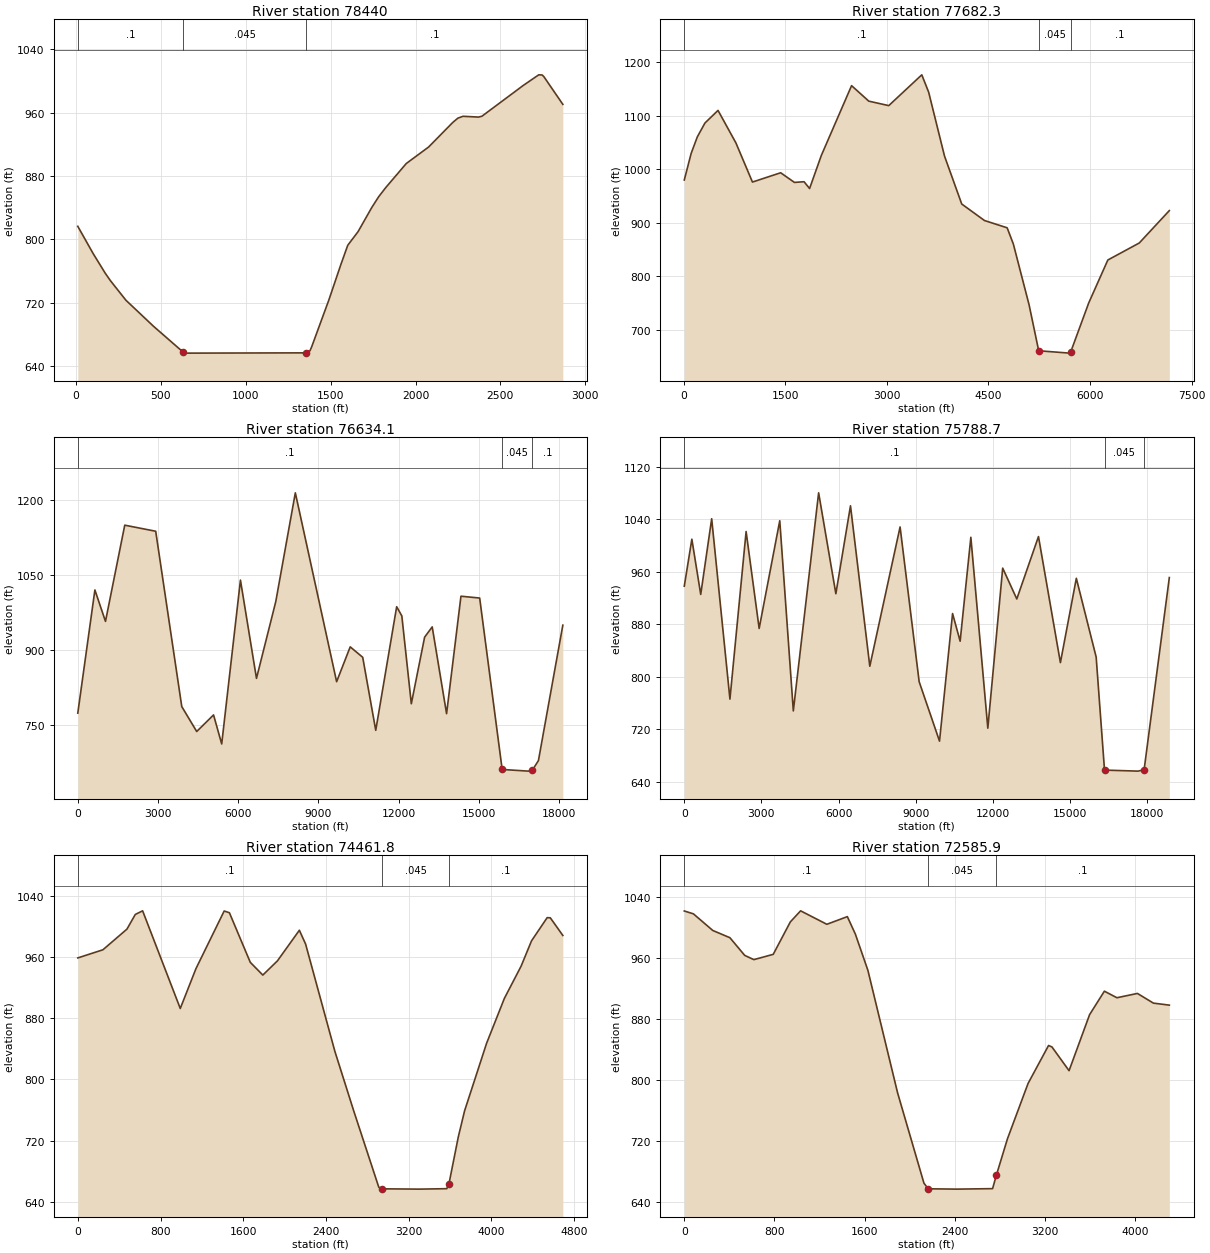
Type RM Length L Ch R = 1 ,78440   ,759.2,757.7,756.2
XS GIS Cut Line= 3
     1579717.076      405475.236     1578850.069      406820.902
     1578814.747      408087.644
#Sta/Elev= 30
    10.1  816.57   101.3  781.93   172.2  757.28   202.6  747.93   293.8  723.27
   455.9  690.51   630.9  657.83   648.4  656.56  1357.6   656.9  1377.9  659.47
    1388   664.4  1489.3  723.54  1560.3  768.44  1600.8  792.66  1661.6  809.87
  1742.7  840.45  1783.3  854.01  1823.8  865.23  1945.5  895.81  2077.3  916.65
  2219.2  947.58  2249.6  953.06    2280  955.41  2371.3  954.41  2391.5  955.52
  2634.8  994.33  2726.1 1007.73  2746.4 1007.52  2756.5 1005.36    2868  970.48
#Mann= 3 , 0 , 0
    10.1      .1       0   630.9    .045       0  1357.6      .1       0
Bank Sta=630.9,1357.6
XS Rating Curve= 0 ,0
Exp/Cntr=0.3,0.1

Type RM Length L Ch R = 1 ,77682.3 ,1074,1048.2,1022.4
XS GIS Cut Line= 4
     1578868.343       400135.96     1579102.198      404998.225
     1578496.353       406095.77     1578343.763      407133.384
#Sta/Elev= 30
    10.2  980.17   111.8 1029.99   203.3 1060.96     315 1086.64   508.1 1110.24
   772.4 1049.45  1016.3  976.31  1432.9  993.69  1636.2  975.64  1778.5  976.91
  1859.8   964.2  2032.5 1025.84  2479.7 1156.52  2733.7 1127.54  3028.5  1119.2
  3516.3 1176.75  3617.9 1144.21  3851.6 1024.87  4105.7  935.29  4441.1  904.43
  4776.4  890.81  4867.9  860.39  5100.4  746.71    5242  660.97  5696.9  656.54
  5714.4  658.69    5980  750.21  6262.7  830.61  6726.6  862.41  7170.3  922.95
#Mann= 3 , 0 , 0
    10.2      .1       0    5242    .045       0  5714.4      .1       0
Bank Sta=5242,5714.4
XS Rating Curve= 0 ,0
Exp/Cntr=0.3,0.1

Type RM Length L Ch R = 1 ,76634.1 ,864.9,845.3,825.8
XS GIS Cut Line= 6
     1572585.177      390517.596     1574419.585      393970.771
     1578462.349      401189.006     1577515.642      404326.676
     1578151.435      406440.688      1578167.33      406917.533
#Sta/Elev= 30
       0  772.92   639.8 1020.14  1035.9  957.07    1757 1150.19  2914.9 1138.02
  3889.9   786.1  4448.9  736.06    5079  769.32  5383.9  711.08  6085.2 1039.94
  6684.9  842.73  7406.5  996.77  8138.3 1215.13  9683.2  836.02 10191.3  905.95
 10658.9  884.98 11146.7  738.46 11929.3  986.52 12122.5  968.09 12477.7  791.76
 12974.9   925.4   13259  946.02 13796.8  771.88 14334.5 1007.61 15034.7 1003.93
   15876  659.86 16850.9  656.52   17000  657.92 17232.9  677.66 18145.5  949.46
#Mann= 3 , 0 , 0
       0      .1       0   15876    .045       0   17000      .1       0
Bank Sta=15876,17000
XS Rating Curve= 0 ,0
Exp/Cntr=0.3,0.1

Type RM Length L Ch R = 1 ,75788.7 ,1310.1,1326.9,1343.8
XS GIS Cut Line= 5
     1566706.401      392153.045     1569970.597       396115.79
     1576204.009      404855.638     1577944.802      406297.634
     1578040.171      407028.796
#Sta/Elev= 30
       0   938.4   294.2    1010   639.2  925.81  1065.4 1041.14  1775.6  766.27
  2404.7 1021.66    2912  873.97  3713.6 1038.11  4241.2  748.31  5225.4 1080.65
  5895.7  926.85  6464.5 1060.86    7216  816.36  8394.1 1028.62  9135.5  792.82
  9927.7  702.23 10435.5  896.66 10730.1  854.52 11146.5 1012.89 11806.6  721.98
 12385.5  965.91 12933.9  918.89 13776.9 1013.98   14630  821.86 15249.5  950.34
 16021.1  830.31 16345.5  658.08 17650.3  656.51 17886.2  658.62 18866.9  951.51
#Mann= 3 , 0 , 0
       0      .1       0 16345.5    .045       0 17886.2      .1       0
Bank Sta=16345.5,17886.2
XS Rating Curve= 0 ,0
Exp/Cntr=0.3,0.1

Type RM Length L Ch R = 1 ,74461.8 ,1884.4,1875.9,1867.5
XS GIS Cut Line= 5
     1574680.041      403705.512      1575460.22      404970.964
     1575874.956      405891.257     1576530.163      407394.377
      1576752.69      407903.012
#Sta/Elev= 30
       0  959.08   242.7   969.7   475.3  996.74   556.2 1015.97     627 1020.71
   991.1  892.91  1142.8  945.05  1415.8 1020.48  1466.4 1018.19  1668.3   953.3
  1789.5  936.62  1930.8  955.23  2142.8  995.28  2203.3  977.18    2486  836.96
  2668.1   759.1    2911  658.99    2943   656.9  3305.8   656.5    3569  657.08
    3590 663.702  3680.3     725    3741  759.05  3953.6  847.37  4125.6  906.12
  4287.2  948.23  4388.1   981.4  4539.5 1011.79  4569.8 1011.56  4690.9   988.5
#Mann= 3 , 0 , 0
       0      .1       0    2943    .045       0    3590      .1       0
Bank Sta=2943,3590
XS Rating Curve= 0 ,0
Exp/Cntr=0.3,0.1

Type RM Length L Ch R = 1 ,72585.9 ,1437.4,1388.6,1339.7
XS GIS Cut Line= 4
     1572369.657      405103.515     1573732.673      405900.264
     1574638.678      407060.586     1575719.526      407696.379
#Sta/Elev= 30
       0 1021.29      81 1017.53     253  995.72   404.8  986.25   536.4  963.03
   617.4  957.48   789.4  964.43   941.2 1006.96  1032.3  1021.5  1265.1 1003.85
  1447.2 1013.88  1518.1  991.06  1629.6  943.46  1893.5  782.54    2127   664.3
    2165 656.905  2421.5  656.48  2736.2  657.11    2770 674.845  2868.2  722.48
  3050.9     795    3233  844.88  3263.3  842.94    3415  811.82    3597  885.25
  3728.5  916.12  3839.7   907.5  4021.8  913.15  4163.3  900.46  4304.9  897.79
#Mann= 3 , 0 , 0
       0      .1       0    2165    .045       0    2770      .1       0
Bank Sta=2165,2770
XS Rating Curve= 0 ,0
Exp/Cntr=0.3,0.1

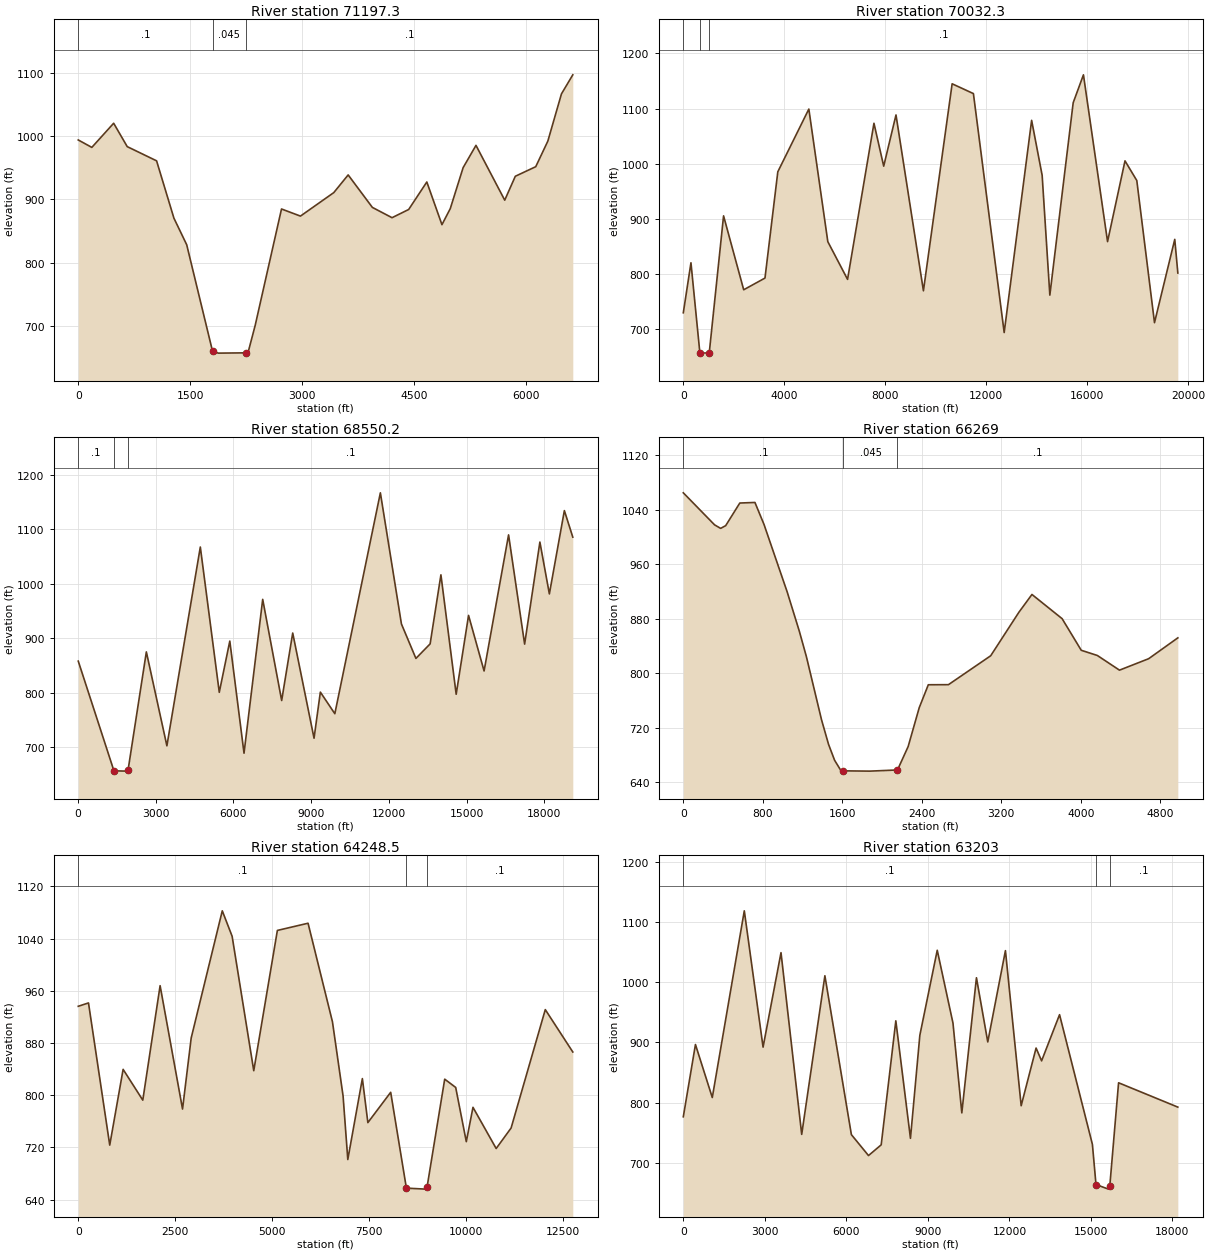
Type RM Length L Ch R = 1 ,71197.3 ,1145.5,1165,1184.6
XS GIS Cut Line= 5
     1572164.827      407620.714     1573700.163      407867.879
      1574715.52      407286.197     1575283.389      408002.532
     1578270.701      408164.406
#Sta/Elev= 30
       0  994.35   181.8  982.57   474.6 1020.86   656.4   983.8  1050.2  961.26
  1282.5  870.43  1454.1  828.24    1800 659.658  1877.9  656.46    2250   656.9
  2281.4  659.51  2372.2  700.41  2725.3  884.94  2979.2  873.66  3426.1  910.89
  3619.1  938.92  3943.6  887.45  4207.3  871.13  4430.4  884.14  4673.8  927.74
  4876.6  860.08  4988.2  885.52  5160.6  950.49    5333  985.78  5718.4  898.93
  5860.3   936.8  6134.2  951.98  6296.4  992.51    6479 1067.37  6631.1  1097.6
#Mann= 3 , 0 , 0
       0      .1       0    1800    .045       0    2250      .1       0
Bank Sta=1800,2250
XS Rating Curve= 0 ,0
Exp/Cntr=0.3,0.1

Type RM Length L Ch R = 1 ,70032.3 ,1454,1482.1,1510.1
XS GIS Cut Line= 6
     1573541.935      408697.753     1574910.762       408804.07
     1575523.936      408206.118     1578926.521      408273.285
     1585177.428      407734.593     1592667.619      406033.018
#Sta/Elev= 30
       0  729.66   302.9  820.31     656 656.871  1012.2  656.44    1028 657.186
  1594.6  905.39    2392  771.34  3235.1  792.57  3743.1  985.33  4972.3 1099.11
    5724  858.58  6505.8  790.17  7551.4  1073.3  7937.2  995.54  8424.5  1088.4
  9510.8   769.5 10647.9 1144.94 11490.5 1127.17 12709.4  693.75 13796.5 1078.64
 14213.1  978.92 14517.9  761.65 15442.5 1110.57 15848.9  1161.2 16803.9  858.71
 17494.8 1005.16 17962.2  969.48 18663.2  711.68 19465.9  862.75 19587.8  801.75
#Mann= 3 , 0 , 0
       0      .1       0     656    .045       0    1028      .1       0
Bank Sta=656,1028
XS Rating Curve= 0 ,0
Exp/Cntr=0.3,0.1

Type RM Length L Ch R = 1 ,68550.2 ,2289.6,2281.2,2272.7
XS GIS Cut Line= 4
     1572832.293      409413.051       1573710.4      409733.629
     1574616.383      410904.439     1590791.305      414997.836
#Sta/Elev= 30
    10.2  858.04    1387 656.949  1900.9  656.42  1935.9  659.28  2638.7  874.97
  3431.3  702.78  4721.8 1067.23  5453.4  800.86  5859.9  894.81  6408.6   689.3
    7130  971.27  7861.7  785.83  8288.4  909.56  9111.5  716.75  9355.4  801.25
  9914.2  761.67 11672.1 1166.58   12485   926.2 13043.9  863.02 13592.6  889.67
 14009.2 1016.25 14598.6  797.33 15076.2  941.88 15675.7  840.01 16620.7 1089.48
 17240.5  889.26 17829.9  1076.3 18195.7  981.26 18774.9 1133.98   19100 1085.37
#Mann= 3 , 0 , 0
    10.2      .1       0    1387    .045       0  1935.9      .1       0
Bank Sta=1387,1935.9
XS Rating Curve= 0 ,0
Exp/Cntr=0.3,0.1

Type RM Length L Ch R = 1 ,66269   ,2038.2,2020.6,2002.9
XS GIS Cut Line= 4
     1570923.077      409815.947     1571567.226       410873.59
     1572542.965      411617.215     1575015.785      412051.061
#Sta/Elev= 30
       0 1064.46   314.7 1017.49   375.6 1012.33   426.3 1016.33   568.4  1049.5
   720.7 1050.34     812 1018.12  1045.5     919  1167.3  861.58  1238.4  824.29
  1390.4  731.89  1461.4  695.64  1522.2  672.36  1583.1  657.85    1611   656.8
  1877.1   656.4    2155 658.089  2262.4  692.48  2373.9  749.48  2465.2  783.04
  2667.6  783.16  3092.8  825.55  3376.3  889.28  3507.9  915.43  3811.6  879.91
  4003.9  833.59  4165.9  825.97  4388.6  804.45  4682.2  821.24  4975.8  851.81
#Mann= 3 , 0 , 0
       0      .1       0    1611    .045       0    2155      .1       0
Bank Sta=1611,2155
XS Rating Curve= 0 ,0
Exp/Cntr=0.3,0.1

Type RM Length L Ch R = 1 ,64248.5 ,1041,1045.5,1049.9
XS GIS Cut Line= 4
      1569914.75      404734.978     1570908.213      413013.254
     1572111.401      413148.305      1575163.65      412138.152
#Sta/Elev= 30
       0  936.34     264  941.46   812.4  723.63  1157.7  839.69  1665.5   792.5
  2112.3   967.9  2691.2  778.87  2914.6  887.77  3716.9 1082.58  3970.8 1043.66
  4529.4  837.65  5138.7 1052.54  5930.8 1063.57  6560.5  912.54  6834.7  798.84
  6956.5  701.52  7332.3  825.55  7474.5  758.12  8063.5  804.53  8468.8  657.69
  8973.3   656.2  9003.6  659.83  9457.6  824.68  9741.1  811.99   10015  728.92
 10187.4  781.53 10785.8  718.41 11171.2  749.83 12053.5  931.23 12763.5  866.31
#Mann= 3 , 0 , 0
       0      .1       0  8468.8    .045       0  9003.6      .1       0
Bank Sta=8468.8,9003.6
XS Rating Curve= 0 ,0
Exp/Cntr=0.3,0.1

Type RM Length L Ch R = 1 ,63203   ,1922.6,1912.2,1901.8
XS GIS Cut Line= 5
     1566780.578       399683.43     1569786.265      405629.309
     1570641.751      413977.643     1571634.556      414229.153
     1573552.362      415132.357
#Sta/Elev= 30
       0  776.45   446.9  896.54  1066.4  808.41  2244.5 1118.73  2935.1  892.19
  3595.3  1049.2    4357  747.18  5210.1 1010.83  6185.1  746.75  6814.8  711.98
  7282.2  729.81  7820.6  935.93  8359.1  740.62  8704.5   911.9  9344.6  1053.2
  9923.7  932.12 10248.8  782.95 10787.3 1007.51 11203.9  900.82 11854.1 1052.56
 12433.2  794.82 12981.8  890.65   13185  869.39 13845.4  946.13 15054.5  730.55
 15186.3  663.82 15645.4   656.2 15693.3  660.62 16017.8  832.95 18198.5  792.51
#Mann= 3 , 0 , 0
       0      .1       0 15186.3    .045       0 15693.3      .1       0
Bank Sta=15186.3,15693.3
XS Rating Curve= 0 ,0
Exp/Cntr=0.3,0.1

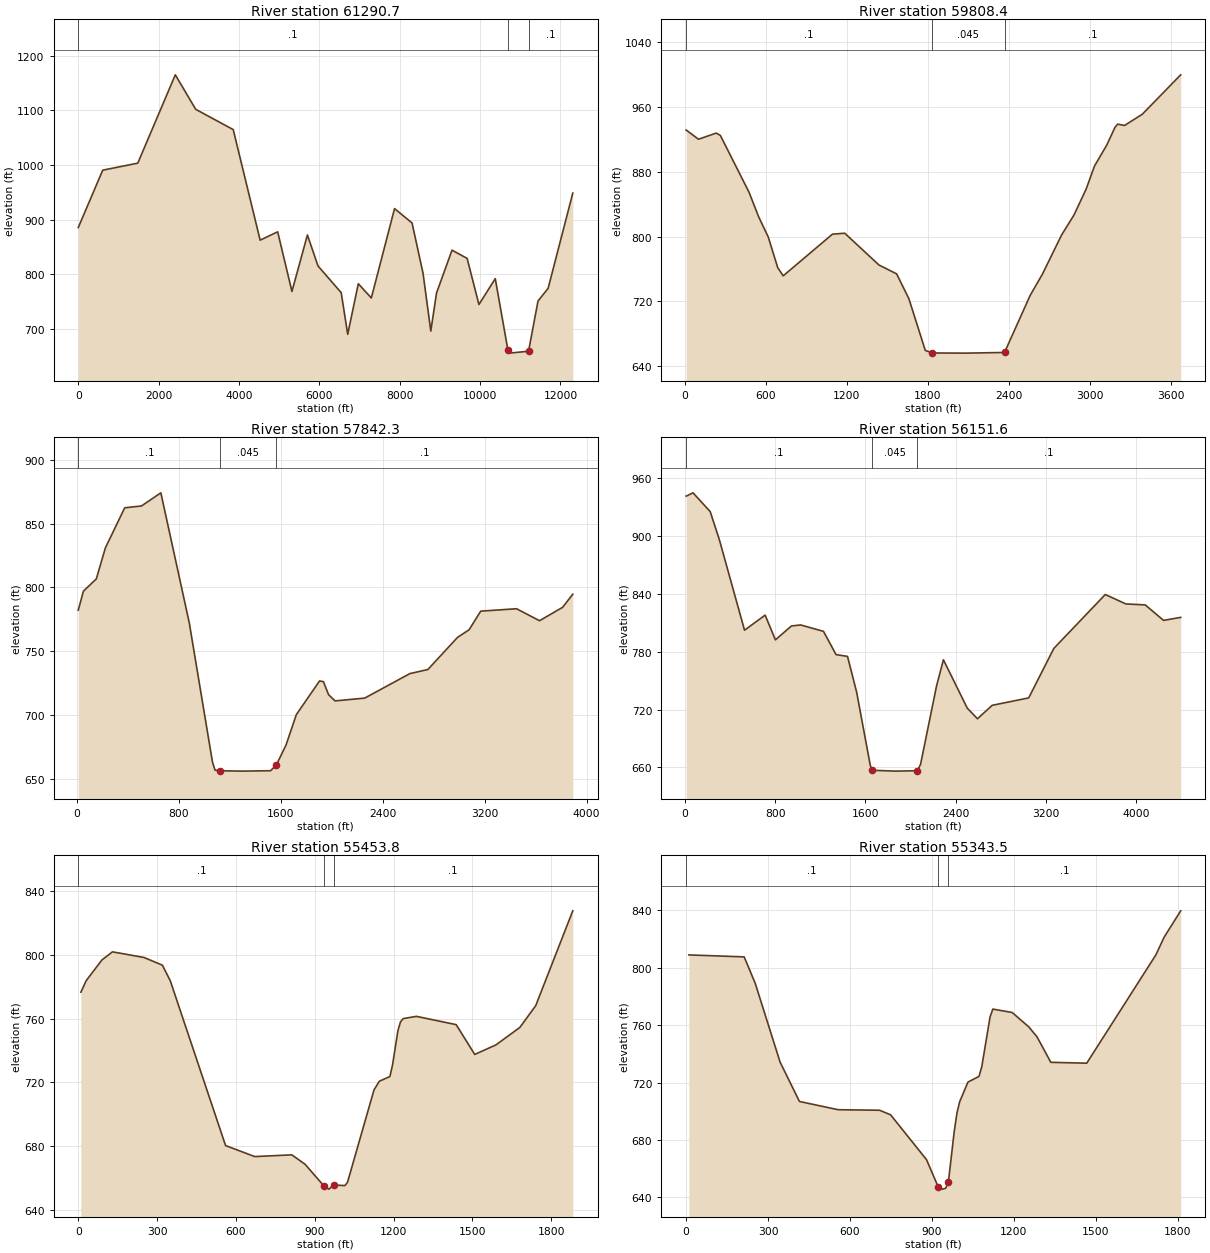
Type RM Length L Ch R = 1 ,61290.7 ,1471,1482.4,1493.8
XS GIS Cut Line= 6
     1561484.398      411593.888     1565971.446       414314.39
     1569186.686      414870.725     1570823.919        415929.9
     1571872.978      415834.531     1572667.719      415834.531
#Sta/Elev= 30
       0   885.7     609  990.63  1481.8 1003.49  2415.6 1164.94  2923.1 1101.88
  3856.9 1064.79  4526.7  862.66  4963.2  877.91  5318.3   768.9  5703.4  872.18
  5966.8  815.51  6544.5  766.68  6706.6  690.57  6970.1  783.04  7294.3  756.96
    7872  920.37  8307.7  894.12  8581.5  802.04  8774.4  696.46  8916.6   765.9
  9302.5  844.42  9678.3  829.34  9972.8  745.04 10379.1  792.34 10693.3  661.98
 10728.2  656.14 11207.1  659.57 11442.8  751.33 11694.8  774.63 12308.5  948.73
#Mann= 3 , 0 , 0
       0      .1       0 10693.3    .045       0 11207.1      .1       0
Bank Sta=10693.3,11207.1
XS Rating Curve= 0 ,0
Exp/Cntr=0.3,0.1

Type RM Length L Ch R = 1 ,59808.4 ,1958.9,1966,1973.2
XS GIS Cut Line= 4
     1568917.225       416206.65     1570124.547      417058.433
     1571300.764       417344.54      1572206.77      417726.016
#Sta/Elev= 30
    10.1  931.49   101.2  920.09   232.8  927.69   263.1  924.82   475.7  854.65
   546.5  824.44   617.3  799.68   688.2  761.54   728.7  751.51    1093  802.92
  1184.1  804.11  1437.1  764.92  1568.3  753.92  1659.1  723.22  1780.2  659.55
    1830   656.3  2082.8  656.12    2367 656.924  2556.9  727.38  2647.7  753.68
  2789.4  801.88  2880.6  826.38  2971.8   858.8  3032.6   886.9  3123.8  912.84
  3184.7   934.8  3204.9   938.7  3255.6  937.08  3387.3  950.99  3671.1  999.59
#Mann= 3 , 0 , 0
    10.1      .1       0    1830    .045       0    2367      .1       0
Bank Sta=1830,2367
XS Rating Curve= 0 ,0
Exp/Cntr=0.3,0.1

Type RM Length L Ch R = 1 ,57842.3 ,1731.6,1690.7,1649.7
XS GIS Cut Line= 4
     1568014.352      417213.075     1570156.337      418250.545
     1570935.183      418250.545      1571650.45      418091.597
#Sta/Elev= 30
    10.1   782.2    50.6  797.09   151.9  806.73   222.8  830.96   374.7  862.42
   506.4  863.85   658.3  874.15   881.1  772.45  1063.4  663.29  1083.7  656.85
    1126   656.4  1296.3   656.1  1519.2  656.41    1565 660.956  1640.7  676.52
  1721.7  700.37    1904  726.75  1934.4  726.18  1974.9  715.98  2025.5  711.12
  2258.5  713.31  2612.7   732.5  2754.3  735.72  2986.9  760.88  3077.9  766.87
  3168.9  781.44  3449.9  783.33  3630.6  773.95  3811.3  784.41  3891.6  794.72
#Mann= 3 , 0 , 0
    10.1      .1       0    1126    .045       0    1565      .1       0
Bank Sta=1126,1565
XS Rating Curve= 0 ,0
Exp/Cntr=0.3,0.1

Type RM Length L Ch R = 1 ,56151.6 ,702.8,697.9,692.9
XS GIS Cut Line= 6
     1568090.009      419712.869     1569504.649      419585.711
     1570172.231      418965.812     1570315.285      418504.862
     1570966.973      418409.493     1571888.873      418409.493
#Sta/Elev= 30
    10.1  941.57      71  945.04   223.2  925.56   304.4   896.4   527.6  802.41
   710.2  818.05   801.5  792.37   943.5   806.8  1024.7  807.85  1227.6  801.22
  1339.2  777.05  1440.6  775.22  1521.6  738.04    1643  661.81    1660 656.948
  1865.7  656.08    2060 656.473  2088.4  663.21  2230.1  744.58  2290.9  771.67
  2502.3  721.51  2592.8  710.45  2723.5  724.42    3047  732.11    3270   783.5
  3725.9  839.45  3908.2  829.68  4080.5  828.66  4242.6  812.59  4394.5  815.72
#Mann= 3 , 0 , 0
    10.1      .1       0    1660    .045       0    2060      .1       0
Bank Sta=1660,2060
XS Rating Curve= 0 ,0
Exp/Cntr=0.3,0.1

Type RM Length L Ch R = 1 ,55453.8 ,109.1,110.2,111.3
XS GIS Cut Line= 3
     1569886.562       420394.13     1570187.389      419945.087
     1571016.711      418890.356
#Sta/Elev= 30
      10  776.66      30  783.87    90.1  796.94   130.1  802.03   250.2  798.49
   320.3  793.64   350.3  783.81   560.7  680.22   671.6  673.31   812.9  674.39
   863.3  668.46   936.6  654.56   954.1  652.84   971.6  655.43  1014.6  655.08
  1024.7   657.1  1125.6  715.22  1145.8  720.68  1186.1  723.63  1196.2     731
  1216.4  752.29  1226.5  758.03  1236.6  760.05    1287  761.47  1438.3  756.26
    1509  737.52  1589.7  743.52  1680.5  754.48    1741  768.16  1882.2  827.82
#Mann= 3 , 0 , 0
       0      .1       0   936.6    .045       0   971.6      .1       0
Bank Sta=936.6,971.6
XS Rating Curve= 0 ,0
Exp/Cntr=0.3,0.1

Type RM Length L Ch R = 1 ,55343.5 ,106.4,107.4,108.4
XS GIS Cut Line= 2
     1569963.271      420355.919     1571122.495      418964.849
#Sta/Elev= 30
    10.1  809.01   212.4  807.64   252.9  789.22   343.9  734.34   414.8  706.88
   556.4  701.14   708.1  700.76   748.6  697.58   880.1  666.33   923.3  647.17
   940.8  645.79   950.9  646.51   958.3  650.58     961  652.07   981.3  685.49
   991.4  698.63  1001.5  706.68  1031.8  720.37  1072.3  724.35  1082.4  731.07
  1112.8  765.75  1122.9  771.26  1193.7   768.9  1254.4  758.89  1284.7  751.94
  1335.3  734.16  1466.8  733.56  1719.7  808.96  1750.1  821.33  1810.8  839.74
#Mann= 3 , 0 , 0
       0      .1       0   923.3    .045       0   958.3      .1       0
Bank Sta=923.3,958.3
XS Rating Curve= 0 ,0
Exp/Cntr=0.3,0.1

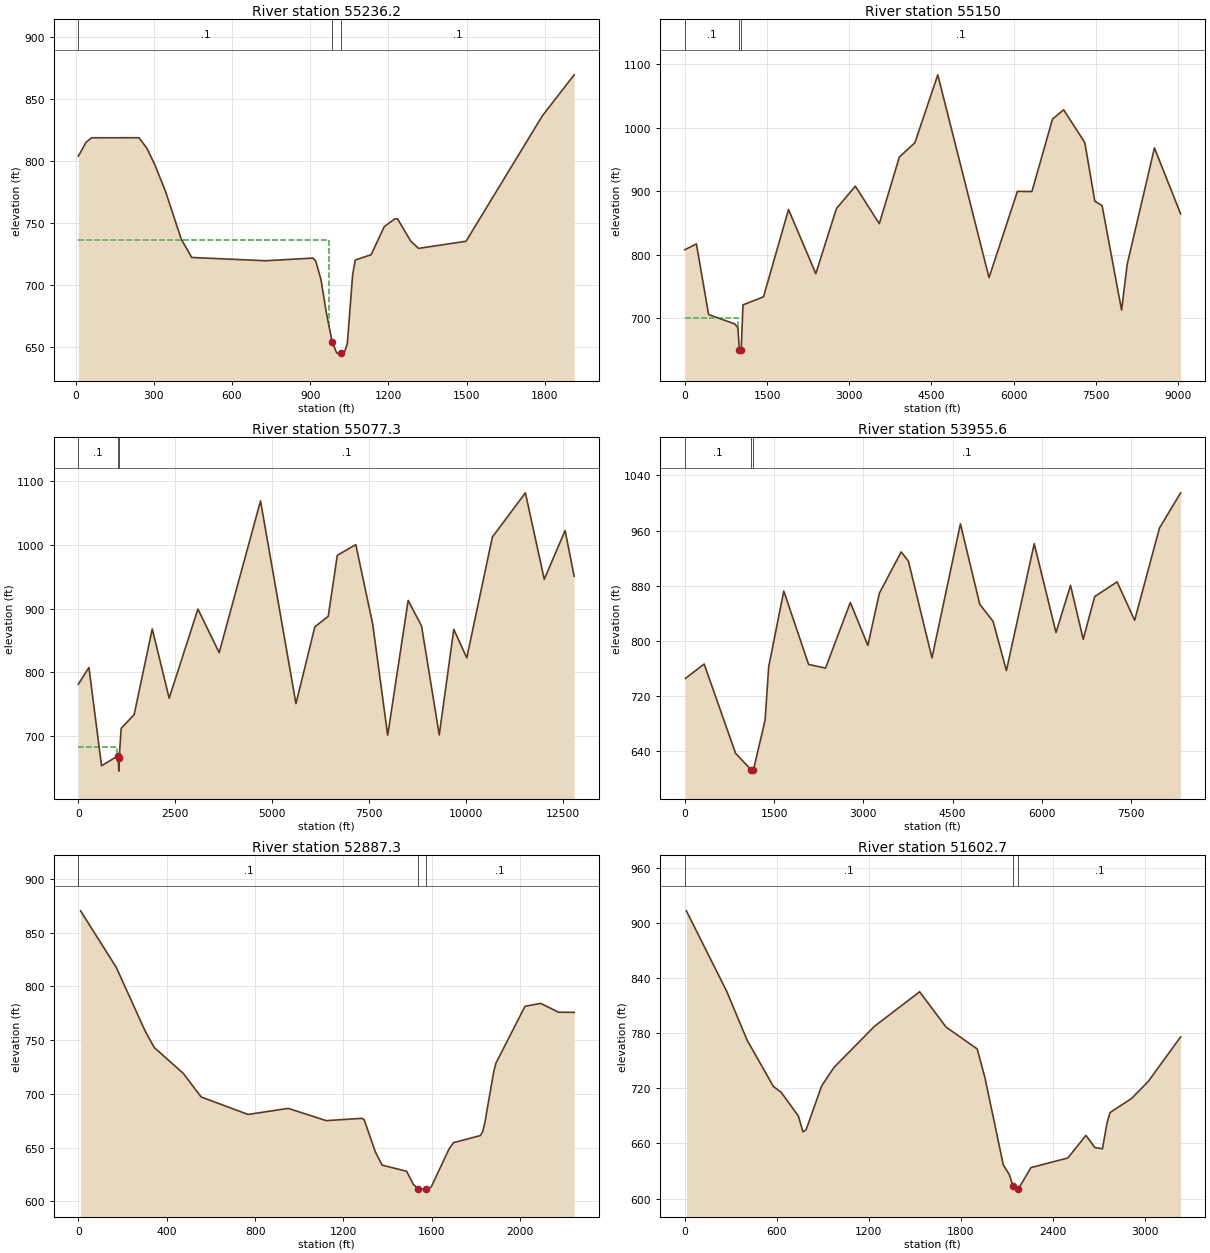
Type RM Length L Ch R = 1 ,55236.2 ,86.2,86.2,86.2
XS GIS Cut Line= 2
     1569969.689      420440.088      1571257.17      419025.448
#Sta/Elev= 30
    10.1  804.07    40.5   815.4    60.7  818.84   242.9   818.9   273.3  810.34
   303.6  797.18   344.1  775.97   404.8  737.28   445.3  722.36   728.7  719.72
   910.9  721.87     921  719.54   941.2  704.64   961.5  678.21   984.4  654.03
  1001.9  645.25  1019.4  645.47  1032.3  646.52  1042.4  653.07  1062.7  708.31
  1072.8  720.36  1133.5  724.54  1184.1  747.22  1224.6  753.51  1234.7  753.61
  1285.3  735.66  1315.7  729.69  1497.9  735.43  1791.4  836.75  1912.8   869.6
#Mann= 3 , 0 , 0
    10.1      .1       0   984.4    .045       0  1019.4      .1       0
#XS Ineff= 2 , 0
          973.15  736.16
Permanent Ineff=
       F       F
Bank Sta=984.4,1019.4
XS Rating Curve= 0 ,0
Exp/Cntr=0.3,0.1

Type RM Length L Ch R = 1 ,55150   ,73,72.6,72.3
XS GIS Cut Line= 3
     1570051.593      420471.841     1571089.183      419338.262
     1576892.068      414572.588
#Sta/Elev= 30
       0  808.03   212.3  817.17   434.7  705.98   909.9  691.29   970.6  685.03
   993.5  650.77    1011  645.24  1028.5  649.88  1061.6  721.23  1435.6  733.82
  1892.4  871.34  2390.3  770.38  2766.2  872.88  3111.7   908.1  3548.6  849.04
  3914.4  953.97  4198.9  976.69  4615.5 1083.42  5550.4  764.16  6068.6  899.94
  6332.8  899.64  6708.7 1013.79  6911.9 1028.37  7298.1  976.72    7481  884.47
    7613  877.52  7968.7  712.99  8070.3  784.81  8568.2  968.34  9045.8  864.49
#Mann= 3 , 0 , 0
       0      .1       0   993.5    .045       0  1028.5      .1       0
#XS Ineff= 2 , 0
          972.03  700.78
Permanent Ineff=
       F       F
Bank Sta=993.5,1028.5
XS Rating Curve= 0 ,0
Exp/Cntr=0.3,0.1

Type RM Length L Ch R = 1 ,55077.3 ,1069.8,1121.7,1173.6
XS GIS Cut Line= 4
     1570091.645      420552.111     1571261.758      419246.022
     1576630.785      414970.646     1580483.383      413379.356
#Sta/Elev= 30
       0  781.49   273.7  807.65     598   653.7  1026.5  669.24    1044  645.22
  1054.2   666.3  1104.9  712.32  1439.4  733.83  1905.9  868.15  2342.4  759.58
  3083.6   899.3  3631.9     831  4697.9 1068.93  5611.7  751.06    6099  871.49
  6444.2  887.95  6677.7  983.53  7154.9 1000.36  7591.5  875.38  7977.3  701.41
  8505.2  912.89  8850.2  872.76  9306.6  701.98  9681.8  867.53 10016.5   822.8
 10675.7 1012.12 11527.6 1081.55 12014.4     946 12551.9 1022.46 12785.2  950.84
#Mann= 3 , 0 , 0
       0      .1       0  1026.5    .045       0  1054.2      .1       0
#XS Ineff= 2 , 0
         1007.16  683.77
Permanent Ineff=
       F       F
Bank Sta=1026.5,1054.2
XS Rating Curve= 0 ,0
Exp/Cntr=0.3,0.1

Type RM Length L Ch R = 1 ,53955.6 ,1059,1068.3,1077.6
XS GIS Cut Line= 4
     1570292.097      420569.995      1571041.97      420435.097
     1571629.173      420946.916     1578410.182      421257.745
#Sta/Elev= 30
    10.2  745.83   325.1  766.65     853  637.35  1118.7  613.15  1136.2  611.54
  1153.7  613.53  1348.7  685.32  1409.4  762.66  1662.8  872.35  2079.4   766.1
    2364  760.76  2780.6  855.78  3075.3  793.65  3268.4  869.19  3634.2  928.93
  3756.1  915.78  4152.5  775.52  4630.1   969.6  4955.2  853.09  5178.8  828.41
  5402.4   757.2  5869.8  940.93  6235.6   812.2  6479.5  880.58  6692.9  802.54
    6886  864.36    7262  885.64  7556.7  830.02  7973.3  963.48    8329 1014.58
#Mann= 3 , 0 , 0
       0      .1       0  1118.7    .045       0  1153.7      .1       0
Bank Sta=1118.7,1153.7
XS Rating Curve= 0 ,0
Exp/Cntr=0.3,0.1

Type RM Length L Ch R = 1 ,52887.3 ,1358.1,1284.6,1211.1
XS GIS Cut Line= 3
     1569072.456       420203.51     1570201.572      420834.985
     1570712.656      421636.143
#Sta/Elev= 30
    10.1   870.2   171.8  817.56   303.2     758   343.6  743.03     475  718.99
   555.9  697.03   768.1  680.78   950.1  686.44  1121.9  675.01  1283.6  677.16
  1293.7   675.8  1344.2  646.07  1374.6  633.64  1485.8   627.9  1516.1  615.76
    1539  611.47  1556.5   611.3    1574  611.31    1597  613.28  1677.9  648.71
  1698.1  654.53  1819.4  661.13  1829.5  664.43  1839.6  672.84  1880.1  720.65
  1890.2  728.57  2021.6  781.38  2092.4  784.11  2173.2   775.9    2244  775.72
#Mann= 3 , 0 , 0
       0      .1       0    1539    .045       0    1574      .1       0
Bank Sta=1539,1574
XS Rating Curve= 0 ,0
Exp/Cntr=0.3,0.1

Type RM Length L Ch R = 1 ,51602.7 ,577.3,603.9,630.5
XS GIS Cut Line= 5
     1568036.642      422432.476      1569919.11      422121.674
     1570152.857       421534.59     1570294.191      421469.359
      1570767.12      421730.285
#Sta/Elev= 30
    10.1   913.1     274  825.32   405.9  772.63   578.5  721.94   629.2  715.59
   740.9  689.94   771.3  672.55   791.6  674.95   893.1  722.59   974.3   742.9
  1238.1   787.5  1532.5  825.02    1705  786.61    1908  762.86  1958.1     732
  2078.5  636.64  2118.6  625.87  2141.2  613.51  2158.7   610.3  2176.2  610.39
    2259   633.7  2499.7   644.2  2617.7  668.76  2676.1  655.58  2725.5  654.19
  2755.5  682.31  2775.5  693.66  2915.6  708.92  3025.6   727.7  3235.7  775.94
#Mann= 3 , 0 , 0
       0      .1       0  2141.2    .045       0  2176.2      .1       0
Bank Sta=2141.2,2176.2
XS Rating Curve= 0 ,0
Exp/Cntr=0.3,0.1

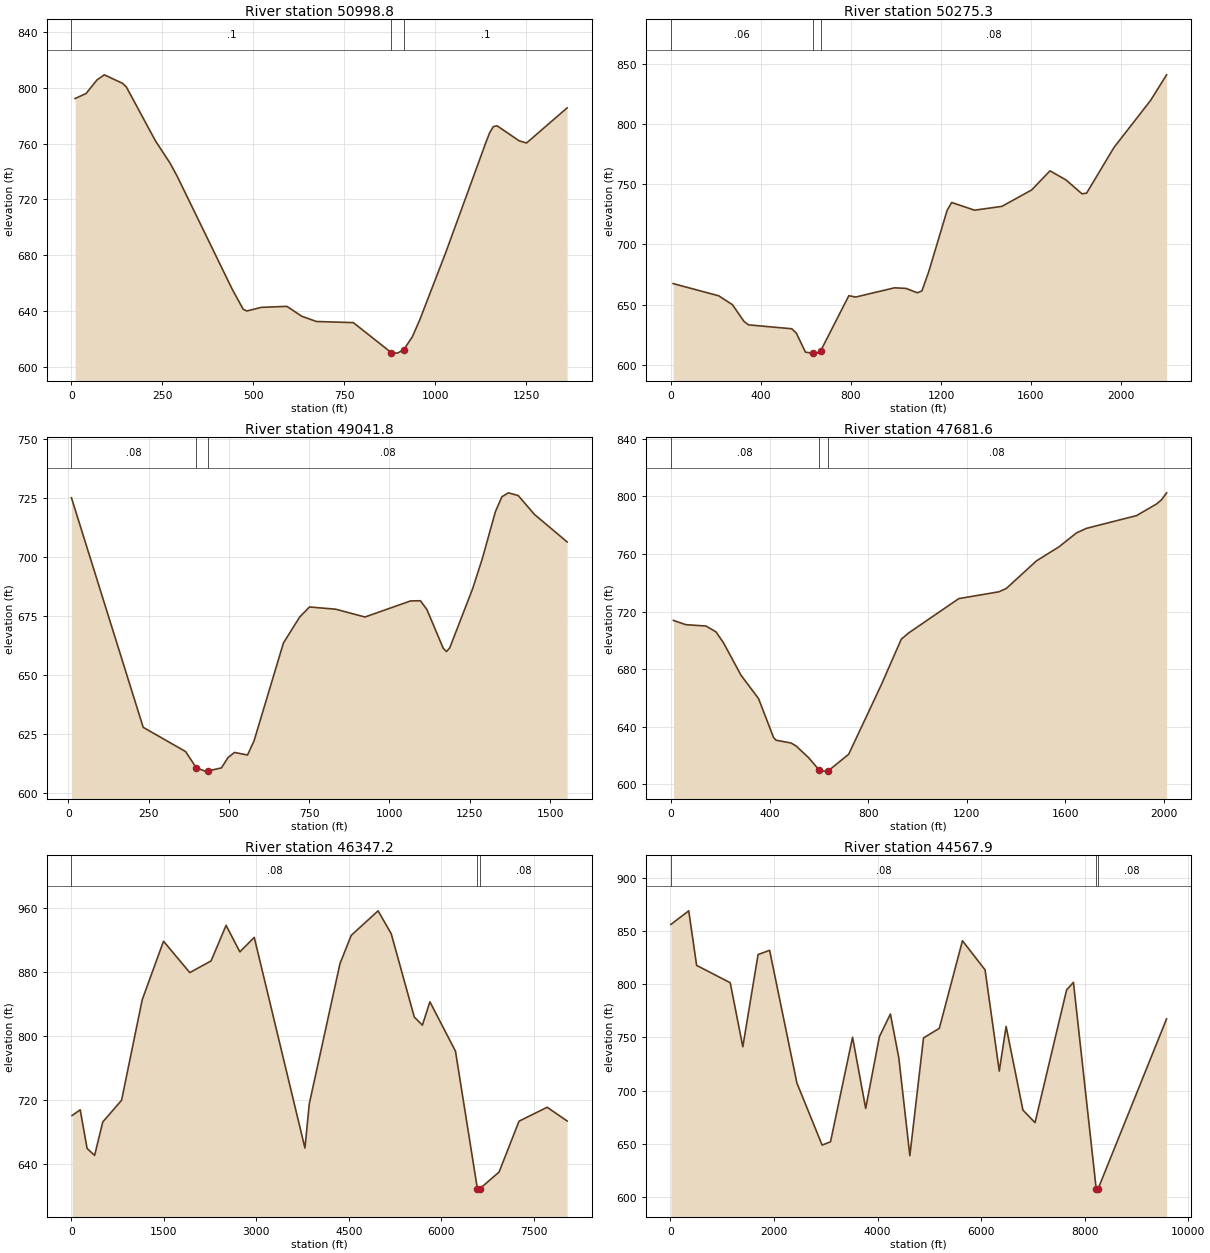
Type RM Length L Ch R = 1 ,50998.8 ,709.2,723.6,737.9
XS GIS Cut Line= 4
      1569806.65      422367.305     1570262.171      422111.686
      1570295.42      422161.508     1571014.657      421858.671
#Sta/Elev= 30
      10  792.33    40.2   795.9    70.3  805.69    90.4  809.32   140.6   803.2
   150.7  800.72     231  761.93   271.2  745.92   291.3  736.24     442  655.51
   472.1  641.19   482.2  639.95   522.3  642.54   592.4  643.25   632.9  636.19
   673.5   632.4   774.8  631.59   878.9  610.15   896.4  609.71   913.9  612.31
     937  621.36   957.2  633.41  1028.2  681.37  1139.7  761.12  1149.8   767.9
  1159.9  772.22  1170.1  772.76  1230.9  761.96  1251.1  760.44  1362.6  785.62
#Mann= 3 , 0 , 0
       0      .1       0   878.9    .045       0   913.9      .1       0
Bank Sta=878.9,913.9
XS Rating Curve= 0 ,0
Exp/Cntr=0.3,0.1

Type RM Length L Ch R = 1 ,50275.3 ,1234.9,1233.5,1232.1
XS GIS Cut Line= 3
     1569963.534       422742.04     1570783.772      422776.698
      1571908.67      421974.903
#Sta/Elev= 30
    10.1  667.42   212.8  657.25   273.7  649.84   324.3  636.08   344.6  633.12
   537.2  629.85   557.4  626.24     598  610.37   631.2   609.6   648.7  609.59
   666.2  611.74   790.6  657.36     821  656.23   993.6  663.91  1044.4  663.43
  1095.2  659.76  1115.5  661.37    1146  677.54  1227.3  728.32  1247.6  734.88
  1349.2  728.47    1471  731.66  1603.1  745.34  1684.3   761.2  1755.4  753.66
  1826.5   742.1  1846.9  742.62  1968.8  780.66  2131.3  819.76  2202.4  841.05
#Mann= 3 , 0 , 0
       0     .06       0   631.2    .045       0   666.2     .08       0
Bank Sta=631.2,666.2
XS Rating Curve= 0 ,0
Exp/Cntr=0.3,0.1

Type RM Length L Ch R = 1 ,49041.8 ,1343.3,1360.2,1377.1
XS GIS Cut Line= 2
     1570013.283      423972.683     1571566.205      423975.335
#Sta/Elev= 30
    10.1  725.13   233.4  627.93   365.4  617.66   398.6  610.79   426.3  609.38
   433.6   609.4     477  610.76   497.3  615.11   517.6  617.29   558.2   616.2
   578.5  622.24   669.9  663.64   720.6  674.65   751.1  678.89   832.3  677.95
   923.6  674.64  1065.7  681.45  1096.2  681.52  1116.5  677.79  1167.2  661.42
  1177.4  660.01  1187.5  661.57  1258.6  686.56    1289  699.39  1329.6  719.23
  1349.9  725.57  1370.2  727.22  1400.7  726.06  1451.4  718.04  1552.9  706.43
#Mann= 3 , 0 , 0
    10.1     .08       0   398.6    .045       0   433.6     .08       0
Bank Sta=398.6,433.6
XS Rating Curve= 0 ,0
Exp/Cntr=0.3,0.1

Type RM Length L Ch R = 1 ,47681.6 ,1329.4,1334.4,1339.4
XS GIS Cut Line= 3
     1569609.261      424975.551     1570426.064      425429.415
     1571419.426      425015.454
#Sta/Elev= 30
    10.2  713.85    60.9  710.87   142.2  709.94   182.8   705.9   213.3  698.33
   284.4  675.75   355.5  659.53   416.4  632.48   426.6  630.59   487.5  628.64
   507.8  626.59   558.6  618.45   602.1  609.75   619.6   609.1   637.1  609.14
   721.1  620.81   853.2     669   934.4  700.74   964.9  705.18  1167.9     729
  1330.4  733.72  1360.8  736.08  1482.7   755.2    1574  764.95  1645.1  774.63
  1685.7  777.82  1888.8  786.67    1970  794.76  1990.3  797.69  2010.6   802.5
#Mann= 3 , 0 , 0
       0     .08       0   602.1    .045       0   637.1     .08       0
Bank Sta=602.1,637.1
XS Rating Curve= 0 ,0
Exp/Cntr=0.3,0.1

Type RM Length L Ch R = 1 ,46347.2 ,1865.9,1779.2,1692.5
XS GIS Cut Line= 6
     1565144.125      420607.207     1566097.077      421783.571
     1567774.787      424564.706     1568789.382      425721.114
      1569377.49      426182.064      1570201.78      425627.866
#Sta/Elev= 30
    10.2  700.83   142.2  707.97     254  659.65   375.9  651.02     508  692.77
   812.8  719.86  1148.1  845.42  1493.6   918.5  1919.9  879.32    2265   893.9
  2508.6  938.32  2731.9  905.25  2965.4  923.31  3787.5  660.23  3858.6  715.66
  4355.9   890.5  4538.6  925.84  4974.4  956.47    5187  927.91  5561.5  823.81
    5693  813.64  5814.5  842.85  6229.5  781.21  6585.7     609  6593.1   608.9
  6620.7  609.21  6936.5  630.19  7260.4  693.74  7716.5  711.14  8040.8  694.01
#Mann= 3 , 0 , 0
       0     .08       0  6585.7    .045       0  6620.7     .08       0
Bank Sta=6585.7,6620.7
XS Rating Curve= 0 ,0
Exp/Cntr=0.3,0.1

Type RM Length L Ch R = 1 ,44567.9 ,1803.6,1843.2,1883
XS GIS Cut Line= 5
     1563694.278      423506.901     1566224.179      426519.595
     1570056.276      426883.216     1569723.416      426087.365
     1570527.938      425609.001
#Sta/Elev= 30
    10.1  856.05   354.9  868.81     507  817.62  1155.9   801.3  1399.2  741.23
  1693.3  827.76  1916.3  831.74  2443.6  707.21  2930.3  648.93  3092.5  652.03
  3518.3  750.13  3771.8  683.34  4035.6  750.56  4248.9  771.95  4411.4  730.84
  4624.7  639.05  4888.8  749.54  5193.5  758.49  5640.3  840.74  6077.1   813.4
  6351.3   718.4  6483.3  760.29  6808.3  681.77  7041.9  670.02  7651.3  794.55
  7783.4  801.69  8222.6  608.08  8229.9   607.6  8257.6  607.62    9582  767.39
#Mann= 3 , 0 , 0
    10.1     .08       0  8222.6    .045       0  8257.6     .08       0
Bank Sta=8222.6,8257.6
XS Rating Curve= 0 ,0
Exp/Cntr=0.3,0.1

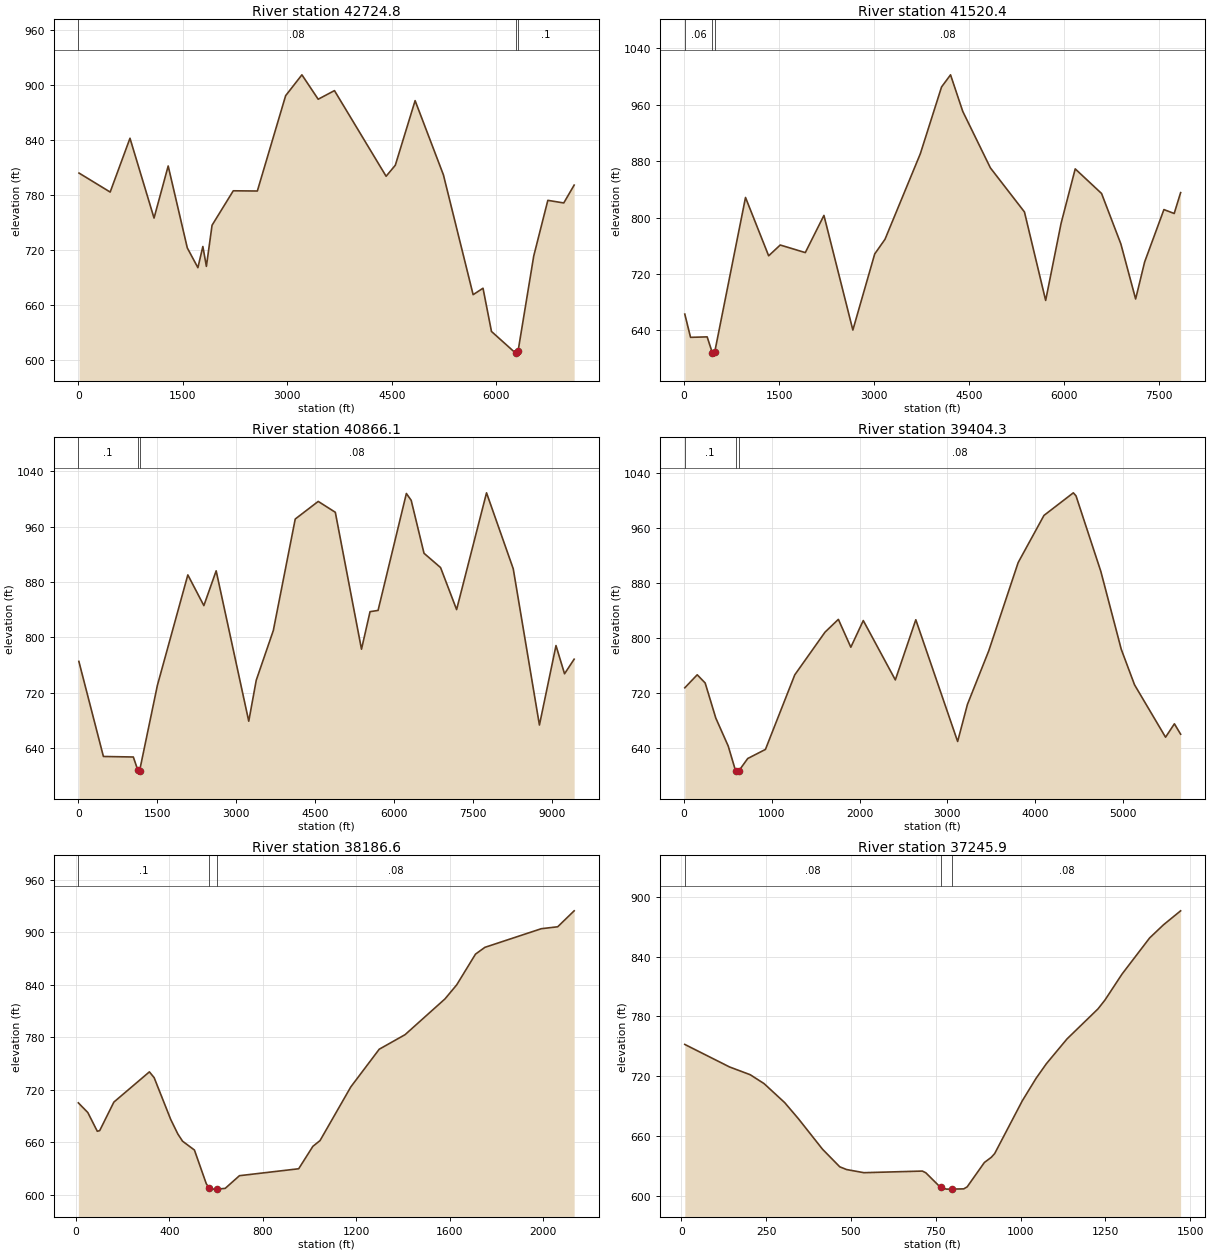
Type RM Length L Ch R = 1 ,42724.8 ,1197.1,1204.4,1211.4
XS GIS Cut Line= 4
     1565215.723      427677.448     1570903.974      427017.293
     1571642.697      426327.011     1571773.438      425972.598
#Sta/Elev= 30
    10.2  804.25   456.9  783.52   741.2  842.28  1086.4  755.12  1289.5  811.99
  1563.6  722.55  1715.9  700.91    1787  724.05  1837.7  702.36    1919  747.26
  2223.6   784.9  2568.8  784.65  2974.9  888.79  3208.4  911.57    3442  884.91
  3675.5  894.32  4416.7  800.78  4548.7  812.79  4832.9  883.38  5239.1  802.29
  5665.5  671.42  5807.3  678.48  5928.6  631.26  6275.1   607.6  6292.6  607.58
  6310.1  609.62  6535.3  713.72  6737.5  774.47  6966.1  771.62  7115.2  791.11
#Mann= 3 , 0 , 0
       0     .08       0  6275.1    .045       0  6310.1      .1       0
Bank Sta=6275.1,6310.1
XS Rating Curve= 0 ,0
Exp/Cntr=0.3,0.1

Type RM Length L Ch R = 1 ,41520.4 ,621.4,654.3,687.3
XS GIS Cut Line= 4
      1571714.03      427755.652     1572461.087      427294.702
     1573820.064      426230.685     1578102.386      423214.448
#Sta/Elev= 30
    10.1  662.96   100.9  629.96   363.2  630.63   446.6  607.63   474.2  607.56
   481.6  608.55   969.2   828.5  1334.7  745.69  1517.4  761.02  1913.4  750.25
  2207.8  803.02  2664.7  640.34  3009.8  748.33  3172.2  769.11  3730.5  890.63
  4065.5  985.35  4207.6 1002.59  4400.5   950.7    4837   870.5    5375  807.95
    5710  682.35  5953.6  791.78  6176.9  869.06  6593.1  834.15  6897.7  762.59
  7131.1   684.4  7273.3  736.94  7577.8  811.32  7740.2  805.77  7841.7  835.37
#Mann= 3 , 0 , 0
    10.1     .06       0   446.6    .045       0   481.6     .08       0
Bank Sta=446.6,481.6
XS Rating Curve= 0 ,0
Exp/Cntr=0.3,0.1

Type RM Length L Ch R = 1 ,40866.1 ,1428,1461.8,1495.6
XS GIS Cut Line= 5
     1571296.446       427585.49     1571507.089      427775.748
     1572791.334      428387.293     1573488.296      429098.676
     1580178.485      429792.552
#Sta/Elev= 30
    10.1  765.36   476.9  627.88  1045.9  627.14    1130  608.33  1147.5  606.71
    1165  607.24  1503.1  730.65  2082.3  890.39  2387.1  846.01  2620.9  896.28
  3240.7  678.89  3382.9  738.06    3708  810.07  4124.6  971.18  4561.5  996.63
  4886.6  980.93  5384.5  782.98    5547  837.24  5699.4  839.04  6237.9 1008.07
  6329.4  998.23  6573.2  921.65  6888.2  900.99    7193  840.25    7762 1009.05
    8270  899.24  8767.8  673.37  9082.8  788.22  9245.4  747.44  9428.2  768.54
#Mann= 3 , 0 , 0
       0      .1       0    1130    .045       0    1165     .08       0
Bank Sta=1130,1165
XS Rating Curve= 0 ,0
Exp/Cntr=0.3,0.1

Type RM Length L Ch R = 1 ,39404.3 ,1255.4,1217.7,1180
XS GIS Cut Line= 4
     1570888.749      427374.846     1571002.928      428448.529
     1573156.315      431138.617      1574023.59      431863.504
#Sta/Elev= 30
    10.1  727.51   151.4   746.4   242.2  734.49   363.3  683.48   504.5  642.91
     588  607.12   595.4  606.49     623   606.5   726.6   624.8   928.4  638.01
  1262.2  746.28  1606.7  808.32  1758.8   826.9  1900.7  786.44  2042.5  825.16
  2407.4  738.95  2640.5  826.32  3116.8  649.53  3228.3  703.35  3471.5  781.31
    3806  909.37  4099.9  977.84  4434.3 1010.66  4464.7 1006.29  4747.6  896.45
  4979.7   783.5  5131.1  731.85  5484.3  655.75  5585.2  675.21  5655.9  660.13
#Mann= 3 , 0 , 0
    10.1      .1       0     588    .045       0     623     .08       0
Bank Sta=588,623
XS Rating Curve= 0 ,0
Exp/Cntr=0.3,0.1

Type RM Length L Ch R = 1 ,38186.6 ,933.1,940.7,948.3
XS GIS Cut Line= 3
     1569468.606      428264.984     1570705.286      428659.091
     1570951.078      429456.399
#Sta/Elev= 30
    10.1   705.1    50.7  694.02    91.3  672.62   101.4   673.3   162.2  705.95
   314.3   740.5   334.6   733.9   405.6  686.07     436   669.5   456.3  661.24
     507  651.17   557.7  612.69   570.6   607.5   588.1  606.48   605.6   606.5
   638.8  607.35   699.7  621.83   953.2  629.76    1014  655.38  1044.5  661.92
  1176.3  723.29    1298  766.38  1408.5     783  1579.4  823.88  1629.7     840
  1710.1  875.08  1750.3  882.83  1991.6  904.11  2061.9  906.33  2132.3  924.56
#Mann= 3 , 0 , 0
    10.1      .1       0   570.6    .045       0   605.6     .08       0
Bank Sta=570.6,605.6
XS Rating Curve= 0 ,0
Exp/Cntr=0.3,0.1

Type RM Length L Ch R = 1 ,37245.9 ,1192.7,1195.4,1198.1
XS GIS Cut Line= 2
     1569339.502      428985.249     1570601.392      429742.506
#Sta/Elev= 30
    10.1  751.75   142.1  729.12     203  721.33   243.6  712.46   304.5  693.36
   345.1  677.12   416.1  646.53   466.9  628.88   487.2  626.11   537.9  622.97
   710.5   624.6   720.6  622.88     764  608.19   781.5  606.47     799   606.5
   832.3  606.73   842.4  608.72   893.2  633.21   913.4  638.36   923.6  642.19
  1004.8  695.04  1045.4  717.63  1075.8  732.31  1136.7  757.24  1228.1  787.43
  1248.4  796.18  1299.1  822.43  1380.3  858.64  1420.9  871.77  1471.7  885.89
#Mann= 3 , 0 , 0
    10.1     .08       0     764    .045       0     799     .08       0
Bank Sta=764,799
XS Rating Curve= 0 ,0
Exp/Cntr=0.3,0.1