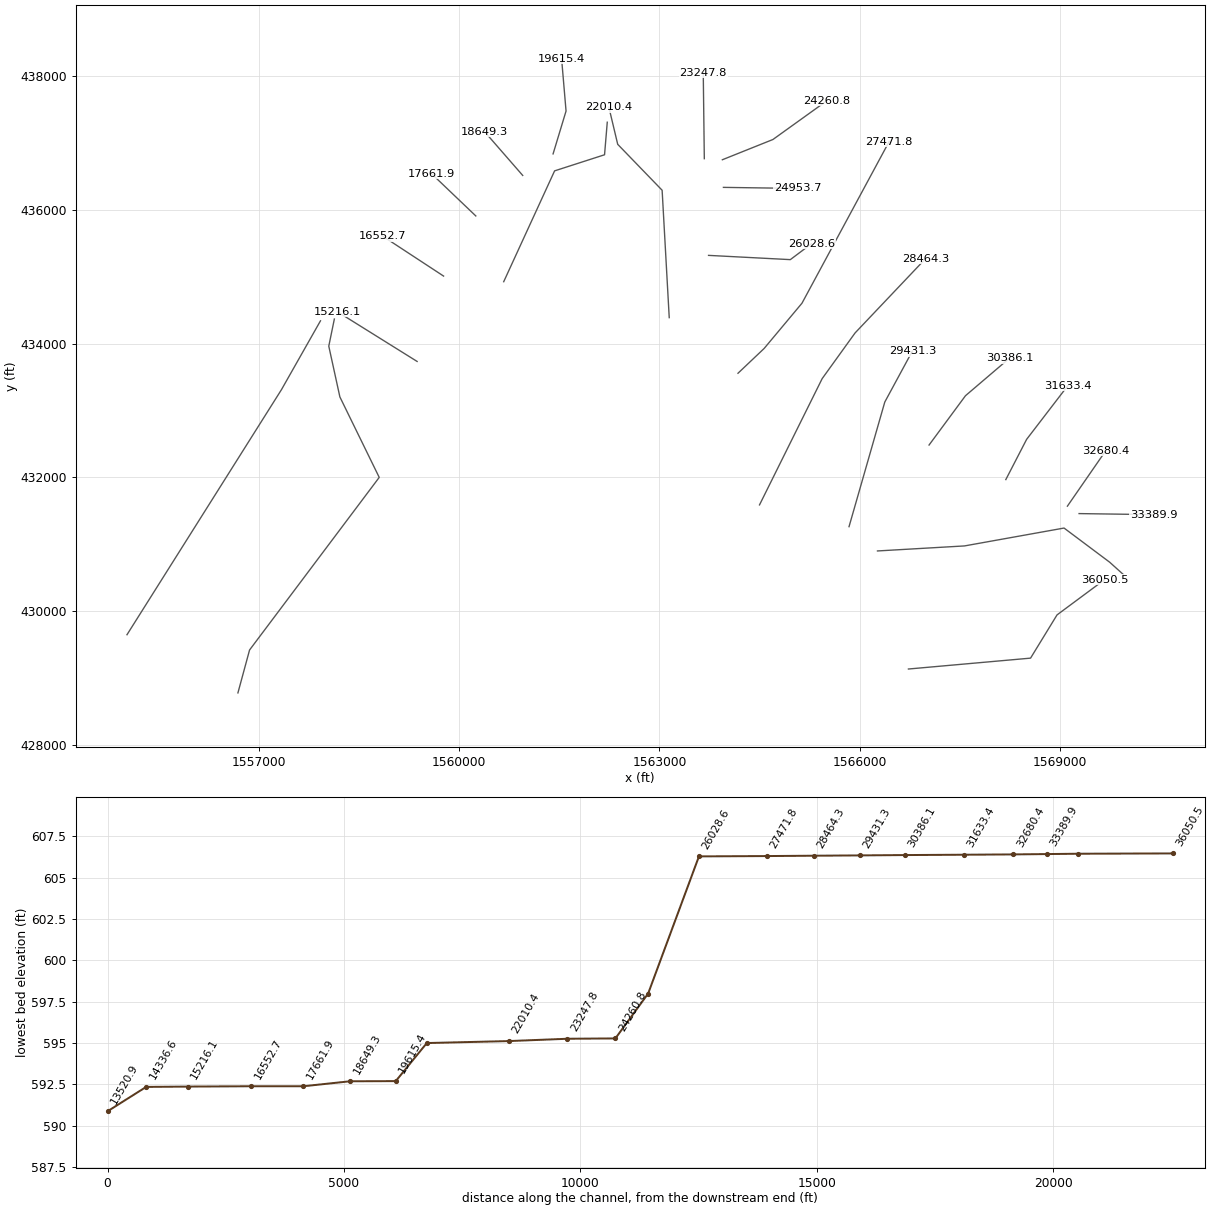
HEC-RAS study EFTWELVECR.prj: EFTWELVECR

--- EFTWELVECR.g01 (geometry) --- (continued)

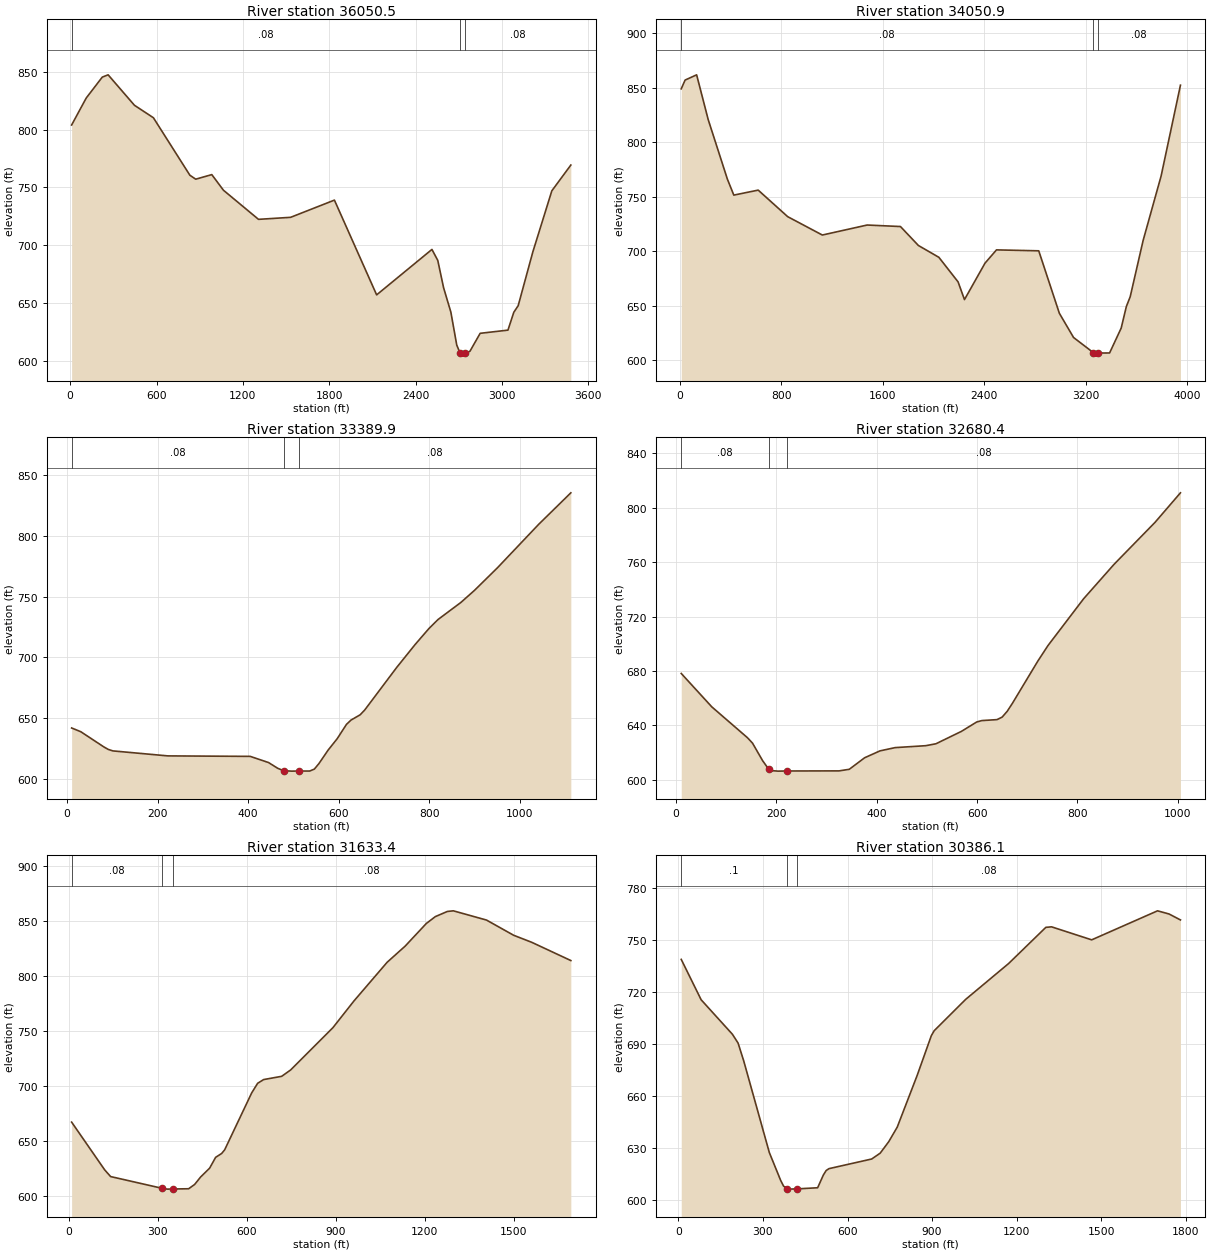
Type RM Length L Ch R = 1 ,36050.5 ,2036.4,1999.6,1962.9
XS GIS Cut Line= 4
     1566727.137      429134.148     1568555.816      429296.976
     1568951.984      429943.675     1569662.476      430469.865
#Sta/Elev= 30
    10.1  803.91   111.6  827.27   223.1  845.36   263.7  847.34   446.3  821.01
   578.2   810.2   831.7  760.42   872.3  757.01   983.9  760.97    1065  747.44
  1308.5  722.25  1531.6     724  1835.9   738.9  2129.2  656.88  2513.4  696.21
  2553.9  686.74  2594.3   663.1  2645.1  641.85  2685.8  613.43  2708.9  606.55
  2726.4  606.46  2743.9   606.5  2777.2  608.03  2848.4   623.6  3041.5  626.37
  3082.1  641.79  3112.6  647.51  3214.2  693.97  3346.3  746.92  3478.4  769.25
#Mann= 3 , 0 , 0
    10.1     .08       0  2708.9    .045       0  2743.9     .08       0
Bank Sta=2708.9,2743.9
XS Rating Curve= 0 ,0
Exp/Cntr=0.3,0.1

Type RM Length L Ch R = 1 ,34050.9 ,646.4,661.1,675.8
XS GIS Cut Line= 5
     1566263.705      430900.201     1567566.325      430975.352
     1569057.031      431242.782     1569740.403       430731.55
     1569944.252      430548.086
#Sta/Elev= 30
    10.1  848.84    40.5  856.87   131.5  861.68   222.5  820.71   374.2  765.95
   424.8  751.36     617  755.94   849.6  731.59  1122.7  714.75  1476.4  723.92
  1738.9  722.54  1880.3  705.16  2041.8  694.32  2193.3  671.78  2243.8  655.53
  2405.3  688.89  2496.2  701.13  2829.5  700.27    2992     643  3103.8  620.81
    3259  606.98  3286.6  606.44    3294   606.5  3388.2  606.59  3479.7  629.42
  3520.3  649.18  3550.8  658.17  3652.4  709.66  3794.6  768.94    3947  852.18
#Mann= 3 , 0 , 0
    10.1     .08       0    3259    .045       0    3294     .08       0
Bank Sta=3259,3294
XS Rating Curve= 0 ,0
Exp/Cntr=0.3,0.1

Type RM Length L Ch R = 1 ,33389.9 ,677.3,709.4,741.5
XS GIS Cut Line= 2
     1569282.121      431459.147     1570394.759      431443.252
#Sta/Elev= 30
    10.1   641.9    30.3  638.85    80.9  626.43      91  624.28   101.2  623.06
   222.6  618.95   404.6  618.55   445.1  613.47   465.3  608.75   478.2   606.8
   495.7  606.42   513.2   606.5   536.1   606.5   546.3  608.11   556.4  612.63
   576.6  623.69   596.8  633.13   617.1  644.82   627.2   648.4   647.4  652.74
   657.5  656.69   728.3  691.77   768.8  710.53   799.2  723.62   819.4   731.1
     870  745.18   900.3  755.21   950.9  773.74  1041.9  809.45  1112.8  835.32
#Mann= 3 , 0 , 0
    10.1     .08       0   478.2    .045       0   513.2     .08       0
Bank Sta=478.2,513.2
XS Rating Curve= 0 ,0
Exp/Cntr=0.3,0.1

Type RM Length L Ch R = 1 ,32680.4 ,1042.9,1047.1,1051.2
XS GIS Cut Line= 2
     1569107.278      431570.411     1569679.492      432396.942
#Sta/Elev= 30
    10.2  678.21    71.1  653.66   142.2  630.96   152.3  626.97   172.6  613.97
   182.8  608.72   185.6  608.16   192.9  606.68   203.1   606.4   220.6   606.5
   324.9  606.58   345.2  607.75   375.7  616.21   406.2  621.27   436.6  623.69
   497.6   625.1   517.9  626.51   568.6  635.61   599.1  642.51   609.3  643.55
   639.7  644.27   649.9  646.12     660  650.41   670.2  656.17     721   687.3
   741.3  698.75   812.3  733.14   873.3  758.58   954.5  789.25  1005.3  811.01
#Mann= 3 , 0 , 0
    10.2     .08       0   185.6    .045       0   220.6     .08       0
Bank Sta=185.6,220.6
XS Rating Curve= 0 ,0
Exp/Cntr=0.3,0.1

Type RM Length L Ch R = 1 ,31633.4 ,1252.5,1247.3,1242.1
XS GIS Cut Line= 3
     1568185.378      431967.782     1568496.664      432569.602
     1569115.268      433374.783
#Sta/Elev= 30
    10.1  667.32   121.4  623.95   141.6   617.8   316.2  607.06   333.7  606.38
   351.2   606.5   404.5  606.72   424.7  610.61     445  617.43   475.3  625.45
   495.5  635.28   515.8   638.8   525.9  642.08   616.9   693.8   637.1  702.63
   657.3  706.02   718.2  708.99   748.6  714.81   890.8  753.21   961.9  777.56
  1073.6   812.7  1134.5  827.42  1205.6  847.96    1236  854.22  1276.6  858.93
  1296.9  859.51  1408.6  851.11    1500   837.3  1560.9   830.9  1692.9  814.29
#Mann= 3 , 0 , 0
    10.1     .08       0   316.2    .045       0   351.2     .08       0
Bank Sta=316.2,351.2
XS Rating Curve= 0 ,0
Exp/Cntr=0.3,0.1

Type RM Length L Ch R = 1 ,30386.1 ,950.2,954.8,959.4
XS GIS Cut Line= 3
     1567036.015      432484.646     1567581.459      433222.403
      1568238.72       433782.48
#Sta/Elev= 30
    10.1  738.86    80.7  715.58   191.6  695.69   211.7  690.61   231.9  680.24
   322.6  627.46     363  611.32     373  608.14   385.8  606.59   393.2  606.36
   420.8   606.5     494  607.15   514.2  614.48   524.3  617.11   534.4  618.18
   685.6  623.73   715.8   627.1   746.1   633.7   776.3  642.11   846.9   671.9
   897.3  694.87   907.4  697.73  1019.1  715.81  1171.5  736.49  1303.5  757.35
  1323.9  757.64  1466.1  750.14  1699.7  766.88  1740.4  765.07    1781  761.63
#Mann= 3 , 0 , 0
    10.1      .1       0   385.8    .045       0   420.8     .08       0
Bank Sta=385.8,420.8
XS Rating Curve= 0 ,0
Exp/Cntr=0.3,0.1

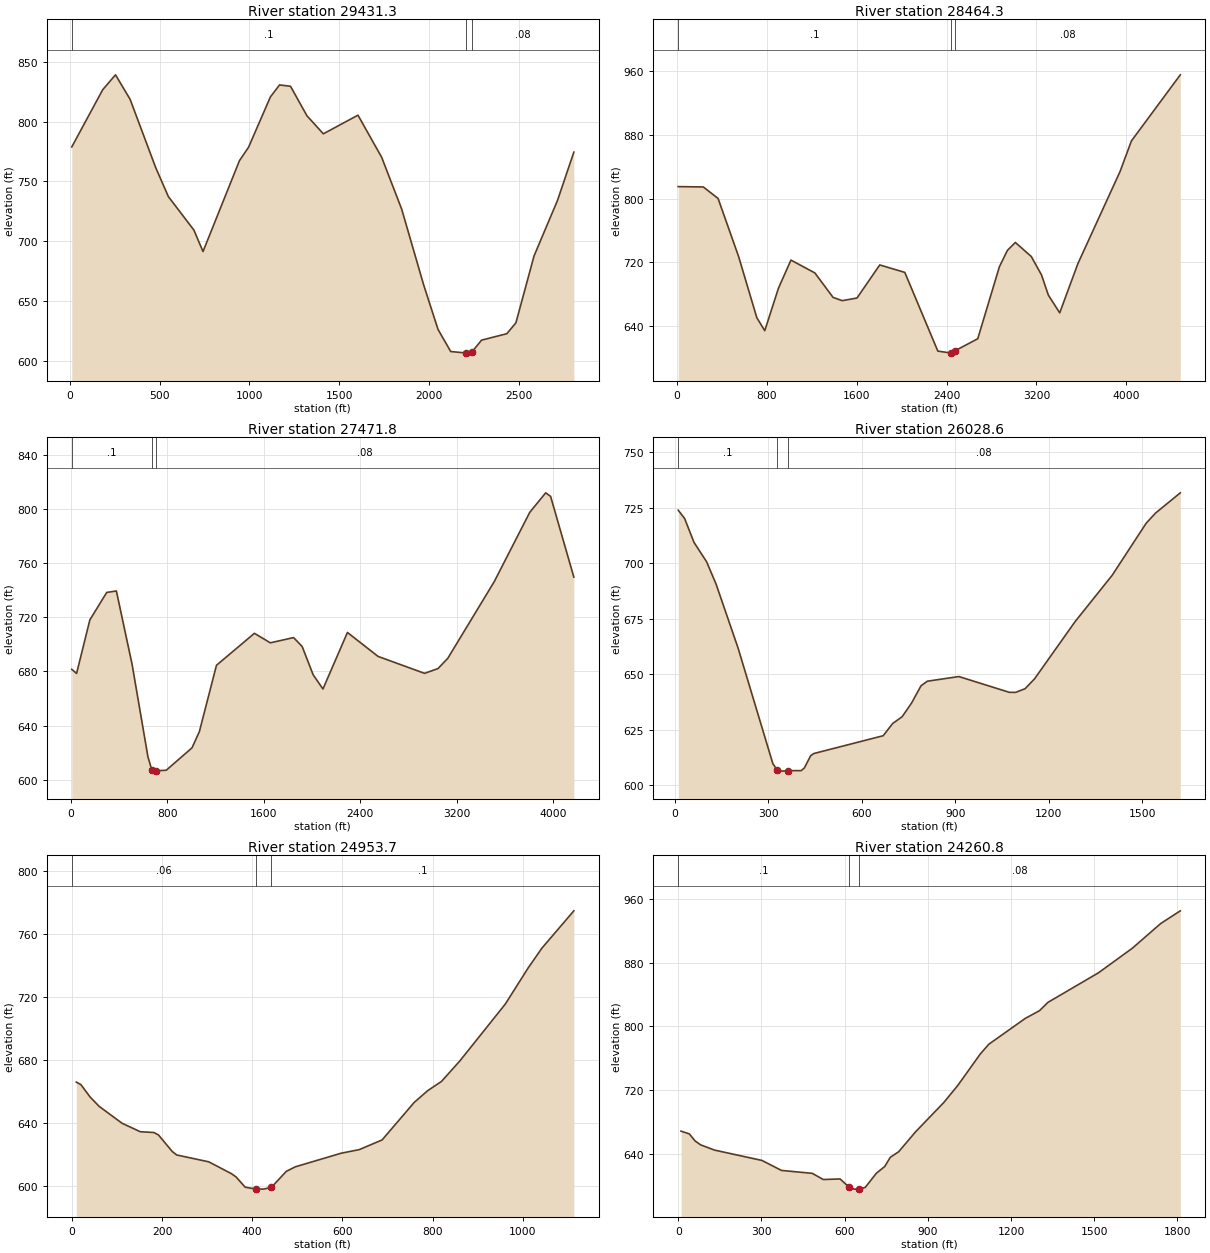
Type RM Length L Ch R = 1 ,29431.3 ,971.5,967,962.5
XS GIS Cut Line= 3
     1565837.848      431263.432     1566373.368      433128.104
     1566786.633      433891.056
#Sta/Elev= 30
    10.2  778.77   182.8  826.67   253.9  839.08   335.2  818.63   477.4  761.67
   548.5  737.25   690.7  709.25   741.5  691.29   944.6   767.3   995.4  778.57
  1117.3  820.71  1168.1  830.63    1229  829.52  1320.5  804.86  1411.9  789.74
  1604.9  805.34  1736.9  770.11  1848.6  726.67  1970.3   663.7    2051  626.15
  2121.7  607.67  2205.1   606.5  2212.5  606.34  2240.1  607.31  2293.2  617.18
  2434.4  622.59  2484.9  631.67  2585.8  687.55  2716.9  734.16  2807.7  774.42
#Mann= 3 , 0 , 0
    10.2      .1       0  2205.1    .045       0  2240.1     .08       0
Bank Sta=2205.1,2240.1
XS Rating Curve= 0 ,0
Exp/Cntr=0.3,0.1

Type RM Length L Ch R = 1 ,28464.3 ,994.6,992.6,990.5
XS GIS Cut Line= 4
     1564497.652      431589.087     1565435.573       433477.79
     1565928.312      434161.268     1566981.655      435270.573
#Sta/Elev= 30
    10.1  815.04   233.2  814.63     365   800.2   547.5  727.51   709.7  650.82
   780.6  634.44   902.3  687.59  1013.8  722.95  1226.7  706.87  1388.9  676.19
  1470.1  672.08  1601.9   675.4  1804.6  716.86  2027.7  707.53  2321.9  608.85
  2436.4  606.49  2453.9  606.32  2471.4  609.02  2677.3  624.34  2870.1  714.63
  2941.2  735.07  3012.1  745.04    3154  727.42  3245.1  704.35  3305.9  679.09
  3407.2  656.81  3569.3  718.58  3944.2  833.84  4045.5  872.27  4481.1  955.17
#Mann= 3 , 0 , 0
    10.1      .1       0  2436.4    .045       0  2471.4     .08       0
Bank Sta=2436.4,2471.4
XS Rating Curve= 0 ,0
Exp/Cntr=0.3,0.1

Type RM Length L Ch R = 1 ,27471.8 ,1473.4,1443.2,1413
XS GIS Cut Line= 4
     1564175.343      433558.247     1564567.119      433929.343
     1565133.571      434606.323     1566439.058      437025.022
#Sta/Elev= 30
      10   681.5      50  678.46   159.9  718.03   299.8  738.33   379.7  739.39
   509.7  685.29   641.1  616.97   674.3  606.78   691.8   606.3   709.3   606.5
   793.3  606.98  1006.3   623.5  1067.2  635.39  1209.3  684.51  1523.8  708.12
  1655.6  701.08  1848.3  704.96  1919.3   698.4  2010.6  677.47  2091.7     667
  2294.6  708.74  2548.1  691.07  2933.5  678.54  3045.1  682.07  3126.2  689.64
  3511.6  746.35  3805.7  797.52  3937.6  811.91  3978.2   809.3  4170.9  749.66
#Mann= 3 , 0 , 0
      10      .1       0   674.3    .045       0   709.3     .08       0
Bank Sta=674.3,709.3
XS Rating Curve= 0 ,0
Exp/Cntr=0.3,0.1

Type RM Length L Ch R = 1 ,26028.6 ,1073.4,1074.9,1076.4
XS GIS Cut Line= 3
     1563734.826       435321.59     1564958.728      435258.011
     1565276.624      435496.433
#Sta/Elev= 30
    10.1  723.83    30.4  720.15    60.8  709.32   101.3  700.59   131.7  690.53
   202.6  661.62     314  609.68   326.9  606.98   344.4  606.28   361.9   606.5
   405.1   606.5   415.3  607.73   435.5  613.23   445.7  614.21   668.5  622.23
   698.9  627.74   729.3  630.78   759.6  636.95     790  644.73   810.3  646.79
   911.6  648.89  1073.6  641.78  1093.9  641.76  1124.3  643.41  1154.7  647.86
  1285.2  673.69  1404.4  694.58  1513.6  718.04  1543.4  722.54  1622.9  731.66
#Mann= 3 , 0 , 0
    10.1      .1       0   326.9    .045       0   361.9     .08       0
Bank Sta=326.9,361.9
XS Rating Curve= 0 ,0
Exp/Cntr=0.3,0.1

Type RM Length L Ch R = 1 ,24953.7 ,679.8,692.9,705.9
XS GIS Cut Line= 2
     1563957.354      436338.859     1565069.992      436322.964
#Sta/Elev= 30
    10.1  666.01    20.2  664.43    40.5   656.6    60.7   650.6   111.3  639.89
   151.7  634.49   182.1  633.96   192.2  632.43   222.6  621.93   232.7  619.69
   303.5  615.36   354.1  607.77   364.2  605.72   384.4  599.21   407.4  598.08
   424.9  597.99   442.4  599.09   475.4  609.26   495.7  612.19   596.8  620.79
   637.3  623.11   687.9  629.27   758.7  653.02     789  660.61   819.4  666.43
   859.9  679.39     961  715.66  1011.6  738.59  1041.9  751.11  1112.8  774.88
#Mann= 3 , 0 , 0
       0     .06       0   407.4    .045       0   442.4      .1       0
Bank Sta=407.4,442.4
XS Rating Curve= 0 ,0
Exp/Cntr=0.3,0.1

Type RM Length L Ch R = 1 ,24260.8 ,972.9,1013,1053
XS GIS Cut Line= 3
     1563941.459      436752.125     1564698.307      437054.864
     1565507.152      437635.215
#Sta/Elev= 30
    10.1  668.26    40.3  664.72    60.4  656.05    80.5  651.03   130.8  644.42
   301.9  631.39   372.4  618.82   483.1  615.16   523.3  607.36   583.7   608.1
   616.5  597.65     634  595.28   651.5  595.29   674.3  597.39   714.5  615.24
   744.7  623.76   764.8  635.37     795  642.33   855.8  667.36   957.4  704.19
  1008.2  725.78  1089.4  765.41  1119.9  777.61    1252  810.28  1302.7  819.85
  1333.2  830.33  1516.1  867.69    1638  898.59  1739.6  929.49  1810.7  945.58
#Mann= 3 , 0 , 0
       0      .1       0   616.5    .045       0   651.5     .08       0
Bank Sta=616.5,651.5
XS Rating Curve= 0 ,0
Exp/Cntr=0.3,0.1

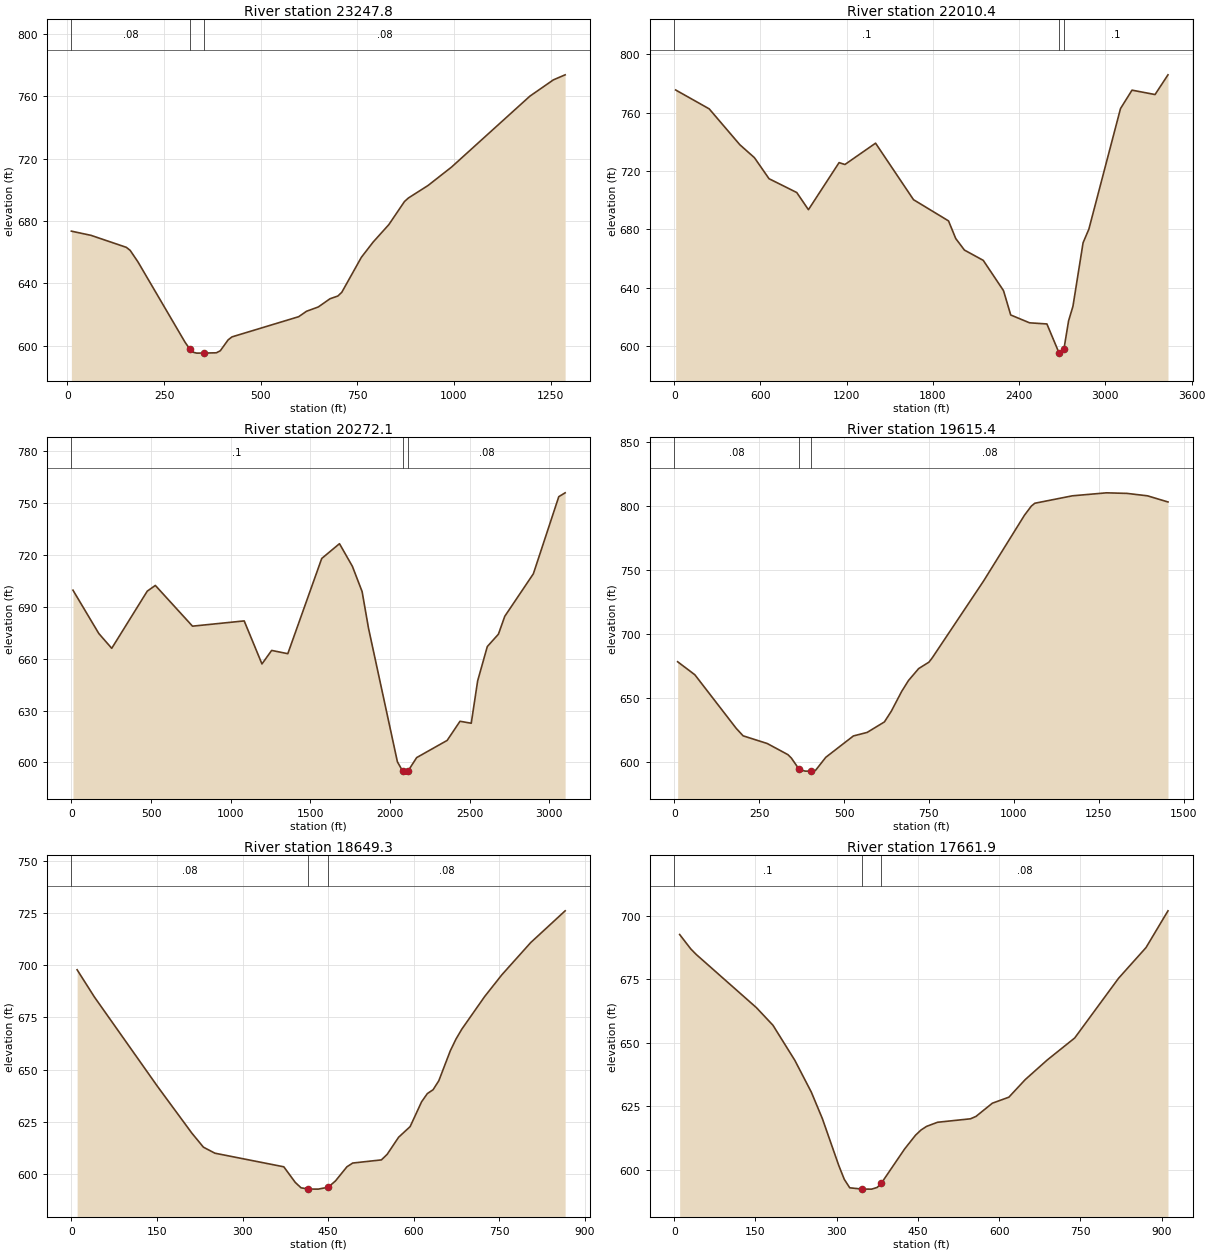
Type RM Length L Ch R = 1 ,23247.8 ,1212.8,1237.5,1262.1
XS GIS Cut Line= 2
     1563671.247       436768.02     1563655.352      438055.501
#Sta/Elev= 30
    10.1  673.51    60.8  670.83   152.1  663.15   162.2   661.2   182.5  653.75
   304.2  602.27   317.1  597.66   324.4  595.88   334.6  595.26   352.1   595.3
   385.3  595.47   395.4  596.76   415.7  603.76   425.8  605.69   598.2  618.63
   618.4   622.1   648.9  624.87   679.3  630.14   699.6   631.9   709.7  634.27
   760.4  656.73   790.8  666.49   831.4  677.68   871.9  692.51     882  694.77
   932.7  702.77   993.6   714.6  1196.3   760.1  1257.2  770.58  1287.6   773.8
#Mann= 3 , 0 , 0
    10.1     .08       0   317.1    .045       0   352.1     .08       0
Bank Sta=317.1,352.1
XS Rating Curve= 0 ,0
Exp/Cntr=0.3,0.1

Type RM Length L Ch R = 1 ,22010.4 ,1805,1738.3,1671.5
XS GIS Cut Line= 4
     1563146.029      434390.222     1563039.681      436295.734
     1562374.682        436982.9     1562242.366       437537.91
#Sta/Elev= 30
    10.2  775.48   243.6  762.54   456.8  737.95   558.3  729.07   659.8  714.67
   852.7  705.19   933.9  693.43  1147.1   725.7  1187.7  724.41  1400.9  739.02
  1664.8   700.3  1908.5  685.75  1958.8  673.64  2019.2  665.75  2150.1   658.7
    2291  637.96  2341.3  621.25  2472.2   615.9    2593  615.11  2676.1  595.55
  2693.6  595.12  2711.1  597.75  2743.9   617.3  2774.1  627.22  2844.6  670.78
  2884.8  680.08    3105  762.75    3185  775.37  3345.2  772.35  3435.3  785.87
#Mann= 3 , 0 , 0
       0      .1       0  2676.1    .045       0  2711.1      .1       0
Bank Sta=2676.1,2711.1
XS Rating Curve= 0 ,0
Exp/Cntr=0.3,0.1

Type RM Length L Ch R = 1 ,20272.1 ,625.3,656.7,688.2
XS GIS Cut Line= 4
     1560667.943      434927.797     1561429.836      436585.772
     1562177.629      436826.616      1562218.26      437313.548
#Sta/Elev= 30
    10.1  699.66   172.3  674.59   253.4  666.03   476.4   699.1   527.1   702.4
   760.3  678.84  1084.7  681.88  1196.2  656.99    1257  664.81  1358.4  662.92
  1571.2  717.98  1682.7  726.54  1763.8  713.43  1824.7  698.84  1864.9  677.64
  2046.2   600.4  2079.1  595.01  2086.5     595  2114.1  595.26  2167.1  602.83
  2358.5  612.77  2439.1  623.84  2509.6   622.7  2549.8   647.2  2610.3  667.03
  2680.1   674.2    2720  684.54  2899.5  709.15    3059  753.74  3098.9  755.96
#Mann= 3 , 0 , 0
       0      .1       0  2079.1    .045       0  2114.1     .08       0
Bank Sta=2079.1,2114.1
XS Rating Curve= 0 ,0
Exp/Cntr=0.3,0.1

Type RM Length L Ch R = 1 ,19615.4 ,932.9,966.1,999.4
XS GIS Cut Line= 3
     1561407.093      436839.736     1561601.213      437480.639
     1561534.618      438262.067
#Sta/Elev= 30
    10.1  678.32    60.9  668.11   182.6  626.18   202.9  620.33     274  614.31
   334.8  605.61     345  602.91   368.1  594.05   385.6   592.7   403.1  592.71
     416  593.25   446.4  603.53   527.6  620.23   568.2  623.01   618.9   631.2
   639.2  639.57   669.7  655.05   689.8   663.6   719.9  672.99   750.1  678.01
   760.1  681.49     911  741.55  1031.6  793.11  1051.7  800.19  1061.8  802.37
  1172.4  808.19  1272.9  810.53  1333.3  810.08  1393.6  808.18  1453.9  803.37
#Mann= 3 , 0 , 0
       0     .08       0   368.1    .045       0   403.1     .08       0
Bank Sta=368.1,403.1
XS Rating Curve= 0 ,0
Exp/Cntr=0.3,0.1

Type RM Length L Ch R = 1 ,18649.3 ,984.3,987.4,990.5
XS GIS Cut Line= 2
     1560952.233      436517.543     1560383.658      437169.509
#Sta/Elev= 30
    10.1  697.82    40.2  684.85   150.9  641.93   211.2   619.5   231.4  612.79
   251.5  609.91   372.2  603.39   392.3   595.9   402.4  593.33     415  592.73
   432.5  592.69     450  593.61   462.7  596.61   482.8   603.4   492.9  605.19
   543.2   606.7   553.2  609.34   573.4  617.58   593.5  622.65   613.6  634.55
   623.7  638.49   633.7  640.32   643.8  644.65   663.9  658.99   673.9  664.63
     684  669.33   724.2  685.03   754.4  695.47   804.7  710.83   865.1  726.07
#Mann= 3 , 0 , 0
       0     .08       0     415    .045       0     450     .08       0
Bank Sta=415,450
XS Rating Curve= 0 ,0
Exp/Cntr=0.3,0.1

Type RM Length L Ch R = 1 ,17661.9 ,1103.3,1109.2,1115.1
XS GIS Cut Line= 2
     1560250.247      435911.286       1559590.7      436540.509
#Sta/Elev= 30
    10.1  692.65    30.4  687.03    40.5  684.83   151.9  663.83   182.3  656.93
   222.8  643.08   253.2  630.56   273.5  620.18   303.8  601.71     314  596.25
   324.1  592.91   347.1   592.4   364.6  592.39   374.7  593.05   382.1  594.62
   425.4  608.21   445.6  613.64   455.8  615.69   465.9   617.1   486.2  618.72
   546.9  620.08   557.1  621.02   587.4  626.23   617.8  628.59   648.2  635.55
   688.7  643.25   739.4  651.91   820.4  675.44     871   687.5   911.6  701.98
#Mann= 3 , 0 , 0
       0      .1       0   347.1    .045       0   382.1     .08       0
Bank Sta=347.1,382.1
XS Rating Curve= 0 ,0
Exp/Cntr=0.3,0.1

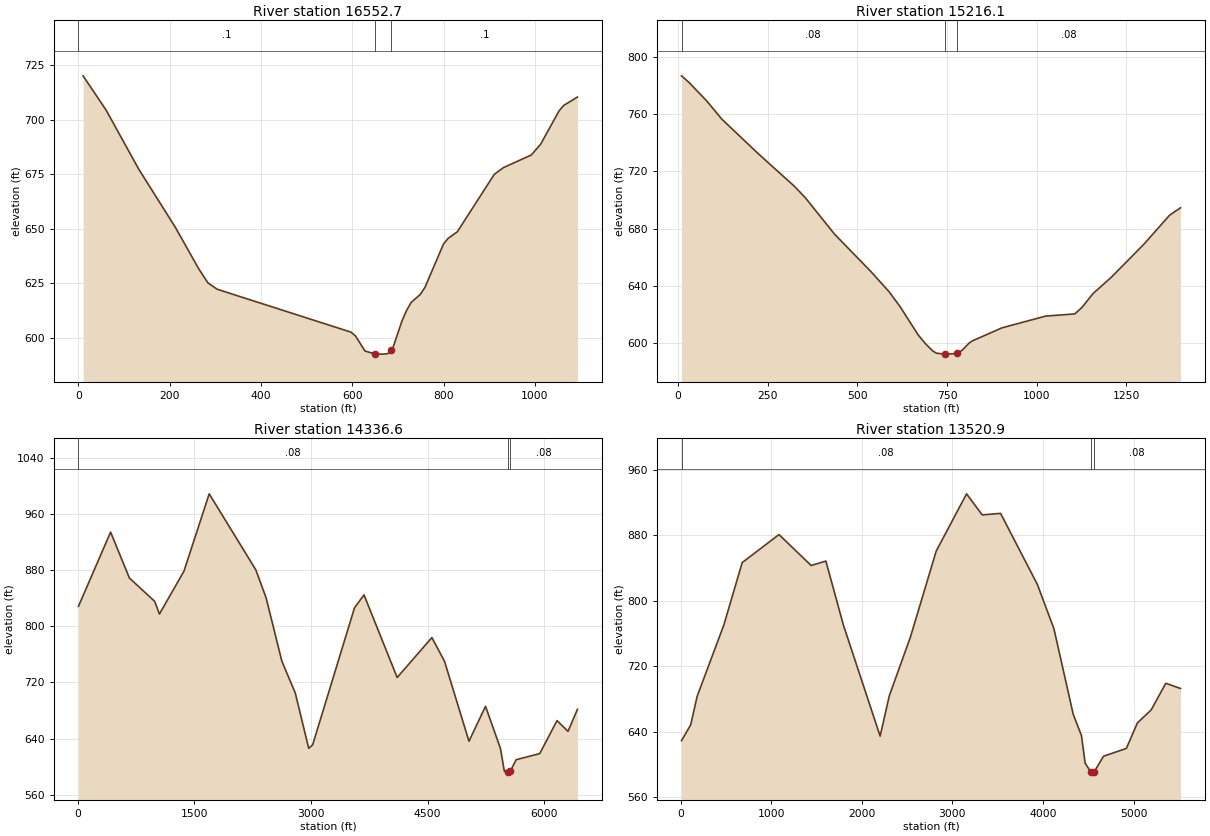
Type RM Length L Ch R = 1 ,16552.7 ,1335.9,1336.6,1337.4
XS GIS Cut Line= 2
      1559767.75      435011.932     1558852.965      435611.093
#Sta/Elev= 30
    10.1  720.13    60.8  704.31   131.6  677.45   212.6  650.48   263.3  631.64
   283.5  625.14   303.8  622.18   597.4  602.47   607.5  600.63   627.8  593.83
   650.8   592.4   668.3  592.39   678.4  592.65   685.8   594.3   688.5   594.9
   708.8  607.53   718.9  612.37     729  616.11   749.3  619.84   759.4  623.07
   799.9   642.9     810   645.5   830.3  648.56   911.3  674.92   931.5  678.02
   992.3  683.79  1012.5  688.63    1053  703.95  1063.2  706.51  1093.5  710.39
#Mann= 3 , 0 , 0
       0      .1       0   650.8    .045       0   685.8      .1       0
Bank Sta=650.8,685.8
XS Rating Curve= 0 ,0
Exp/Cntr=0.3,0.1

Type RM Length L Ch R = 1 ,15216.1 ,906,879.5,853
XS GIS Cut Line= 2
     1559371.316      433734.916     1558182.603      434475.804
#Sta/Elev= 30
    10.1  786.86    30.4  782.39    81.2  769.09   121.8  756.75   223.3   732.6
   324.8  709.66   355.2  701.65   436.4  676.27   537.9  650.08   588.7  635.95
   619.1  625.63   669.9  605.73   690.2  599.59   710.5  594.55   720.6  593.02
   743.7   592.4   751.1  592.37   778.7  592.88   791.7  594.97     812  600.17
   822.1  601.78   903.3  610.74  1025.1  618.96  1106.3  620.48  1126.6  625.12
  1157.1  634.72  1207.8  646.05  1299.2   669.3  1370.2  689.41  1400.7  694.63
#Mann= 3 , 0 , 0
    10.1     .08       0   743.7    .045       0   778.7     .08       0
Bank Sta=743.7,778.7
XS Rating Curve= 0 ,0
Exp/Cntr=0.3,0.1

Type RM Length L Ch R = 1 ,14336.6 ,838.7,815.7,792.7
XS GIS Cut Line= 6
     1556688.586      428776.759     1556862.884      429418.602
     1558804.175      432000.619     1558215.275      433203.658
     1558048.905      433963.686     1558132.296      434369.269
#Sta/Elev= 30
    10.1  828.56   423.2  934.18   665.1  868.78   990.2  835.55  1051.1  817.53
    1366  878.39  1691.1   988.7  2290.4  880.51  2422.5  840.77  2625.7  750.36
  2798.4     705  2971.1  626.26  3021.9  631.27  3560.2  826.42  3682.2  844.76
  4108.6   727.1  4555.1     784  4717.4  750.25    5032  636.35    5245  686.09
    5437  625.97  5487.5  593.38  5530.7  592.39  5548.2  592.35  5565.7  594.09
  5639.1  610.07  5942.2  618.71  6164.4  665.74  6305.8  650.42    6427  681.77
#Mann= 3 , 0 , 0
    10.1     .08       0  5530.7    .045       0  5565.7     .08       0
Bank Sta=5530.7,5565.7
XS Rating Curve= 0 ,0
Exp/Cntr=0.3,0.1

Type RM Length L Ch R = 1 ,13520.9 ,1565.4,1542.3,1519.3
XS GIS Cut Line= 3
     1555027.761      429647.161     1557340.585      433313.252
     1557924.758       434342.93
#Sta/Elev= 30
    10.2  629.32   111.7  648.64   182.7  683.42   477.1  770.35   680.1  846.71
  1086.2   880.9  1441.5  843.17  1603.9  848.56  1796.8   770.6  2202.9  634.85
  2304.4  684.13  2537.9     756  2822.1  860.74  3157.1  930.65  3329.7  904.93
  3532.7  906.78  3938.8  819.98  4121.5  765.98  4334.7  661.42  4425.7   635.5
  4466.2   601.8  4529.7  591.05  4547.2  590.88  4564.7   590.9  4668.6  610.27
  4921.5  619.85    5043  650.94  5194.7  666.78  5356.6  699.36  5518.5  693.02
#Mann= 3 , 0 , 0
    10.2     .08       0  4529.7    .045       0  4564.7     .08       0
Bank Sta=4529.7,4564.7
XS Rating Curve= 0 ,0
Exp/Cntr=0.3,0.1