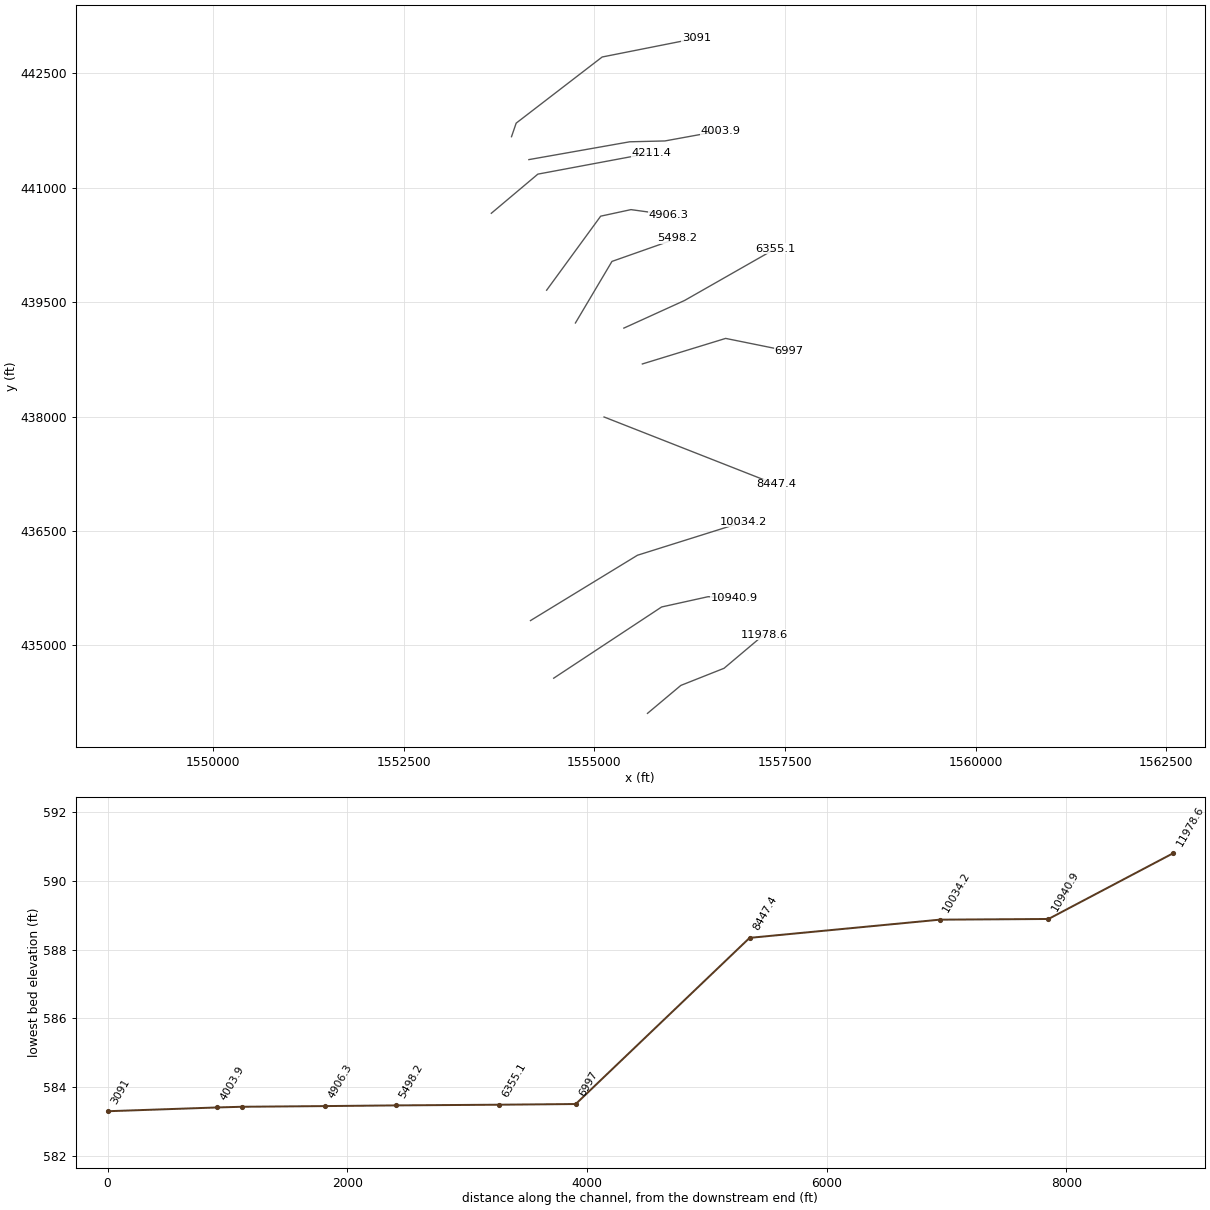
HEC-RAS study EFTWELVECR.prj: EFTWELVECR

--- EFTWELVECR.g01 (geometry) --- (continued)

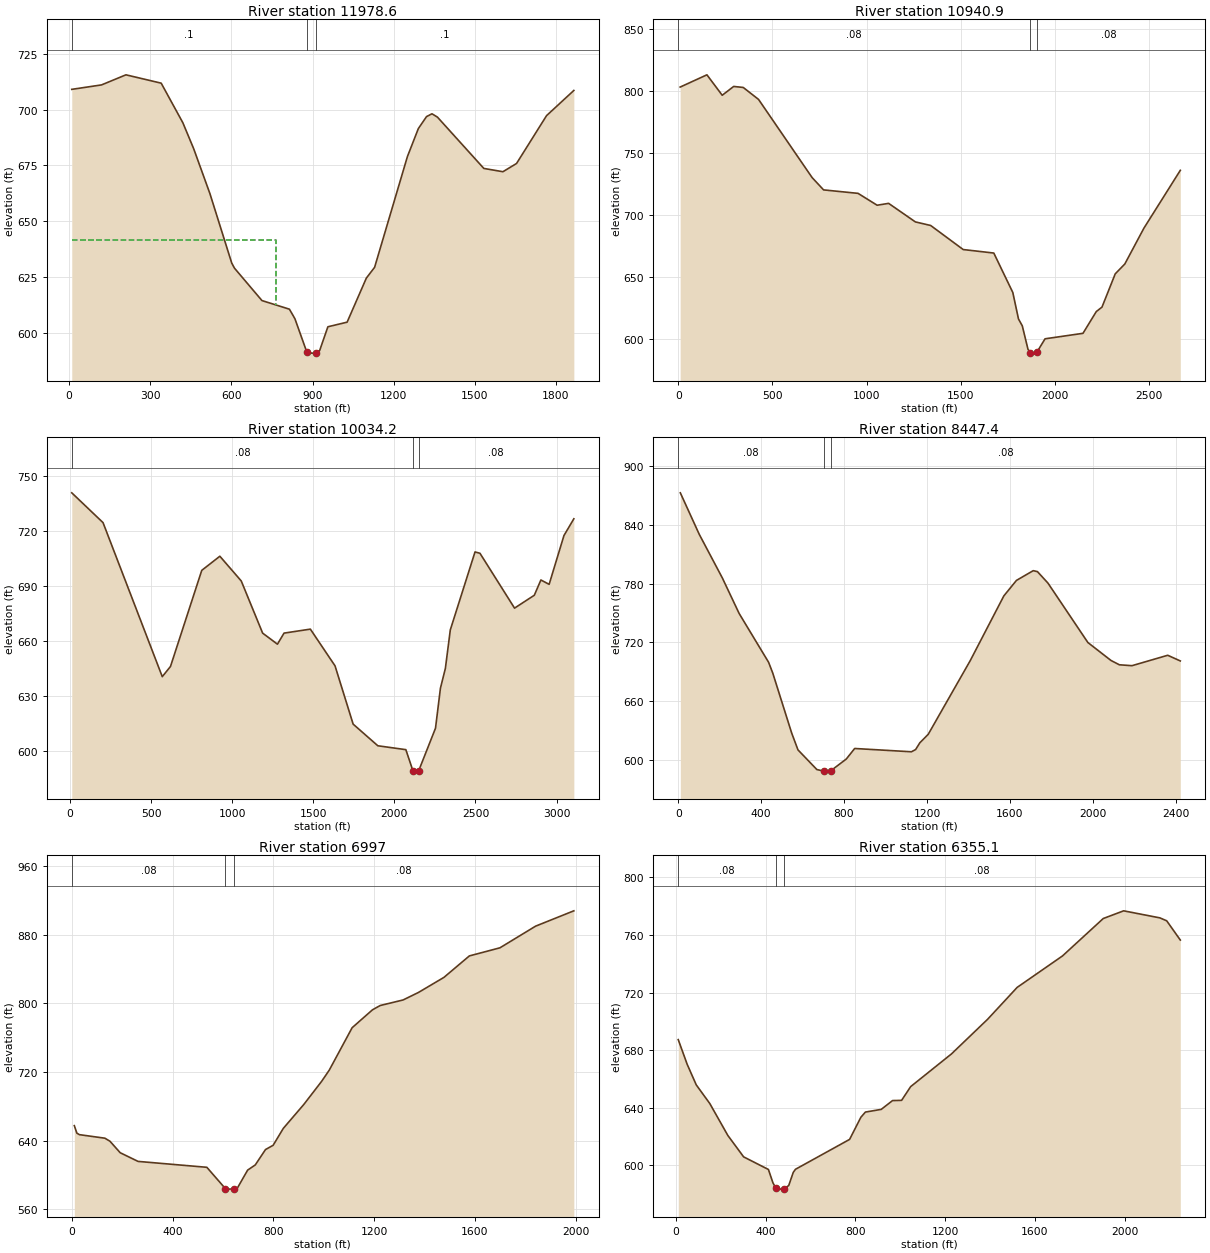
Type RM Length L Ch R = 1 ,11978.6 ,1042.9,1037.6,1032.4
XS GIS Cut Line= 4
      1555695.25      434108.638     1556132.963      434475.197
      1556699.57      434699.596     1557224.113      435141.469
#Sta/Elev= 30
      10  709.13   120.2  711.13   210.3  715.65   340.6  711.91   420.7  694.15
   460.7  682.51   520.8  662.35   601.4   631.2   611.6  628.91   713.1  614.38
   814.7  610.51     835  606.23   878.5  591.44     896   590.8   913.5  590.83
   926.4  591.95   956.9  602.62    1028  604.69  1099.1  624.46  1129.6  629.29
    1251  679.01  1291.3  691.53  1321.6  696.91  1341.7  698.17  1361.9  696.68
  1533.4  673.66    1604  672.18  1654.4  675.88  1765.3  697.34  1866.2  708.64
#Mann= 3 , 0 , 0
      10      .1       0   878.5    .045       0   913.5      .1       0
#XS Ineff= 2 , 0
           765.1  641.48
Permanent Ineff=
       F       F
Bank Sta=878.5,913.5
XS Rating Curve= 0 ,0
Exp/Cntr=0.3,0.1

Type RM Length L Ch R = 1 ,10940.9 ,903.2,906.7,910.2
XS GIS Cut Line= 4
     1554464.862      434569.851     1555880.911      435503.394
     1556490.815      435638.148     1556835.751      435619.195
#Sta/Elev= 30
    10.2  802.98   152.3  812.84   233.6   796.4   294.5  803.49   345.3  802.67
   426.6  793.03   710.9  730.16   771.9  720.24   954.7  717.46  1056.2  707.91
  1117.2  709.41  1259.4  694.48  1340.6   691.6  1513.3  672.24  1675.8  669.42
  1776.7  637.69  1806.9  616.36  1827.1  610.83  1857.3  591.98    1870  589.21
  1887.5  588.89    1905  589.73  1947.9  600.41  2149.4  604.83    2220  622.32
  2250.2   625.9  2320.7   652.7  2371.5  660.61  2473.1  689.49  2666.2  735.99
#Mann= 3 , 0 , 0
       0     .08       0    1870    .045       0    1905     .08       0
Bank Sta=1870,1905
XS Rating Curve= 0 ,0
Exp/Cntr=0.3,0.1

Type RM Length L Ch R = 1 ,10034.2 ,1608.7,1586.9,1565
XS GIS Cut Line= 3
     1554160.674      435325.077     1555563.902      436181.475
     1556959.363      436619.683
#Sta/Elev= 30
    10.1   740.9     203  724.61   568.3  640.47     619  646.06   811.8  698.54
   923.4  706.26  1055.4  692.75  1187.3  664.25  1278.6  658.22  1319.2  664.26
  1481.6  666.44  1633.8  646.38  1745.5  614.54  1897.8  602.72  2070.5   600.6
    2114   589.1  2131.5  588.87    2149  588.91  2253.4  612.31  2283.8  634.14
  2314.3     645  2344.8  666.05  2497.1   708.6  2527.6  707.88  2740.9  677.91
  2862.8  684.95  2903.4  693.29  2954.2  690.91  3045.6  717.56  3106.6  726.72
#Mann= 3 , 0 , 0
    10.1     .08       0    2114    .045       0    2149     .08       0
Bank Sta=2114,2149
XS Rating Curve= 0 ,0
Exp/Cntr=0.3,0.1

Type RM Length L Ch R = 1 ,8447.4  ,1429.3,1450.4,1471.5
XS GIS Cut Line= 2
     1555125.693      437993.872     1557380.553      437108.946
#Sta/Elev= 30
    10.1  872.71   101.4  830.31   212.8  785.74   293.9  749.41   435.8  699.63
   456.1  688.51   547.3  627.26   577.7  610.05   668.9  589.94   702.1  588.35
   709.5  588.34   737.1  588.89   810.8  600.71   851.3  611.47    1125  608.11
  1145.3  610.38  1165.5  617.26  1206.1  625.96  1408.8  701.24  1570.9  767.37
  1631.8  783.23  1712.8  793.17  1733.1  792.18  1783.8  780.46  1976.3  719.77
  2087.8  701.42  2128.4  696.99  2189.2  696.08  2361.5  706.72  2422.3  700.93
#Mann= 3 , 0 , 0
       0     .08       0   702.1    .045       0   737.1     .08       0
Bank Sta=702.1,737.1
XS Rating Curve= 0 ,0
Exp/Cntr=0.3,0.1

Type RM Length L Ch R = 1 ,6997    ,637.7,641.8,645.9
XS GIS Cut Line= 3
     1555628.058      438688.987     1556720.976      439023.883
     1557553.557      438855.397
#Sta/Elev= 30
    10.1  657.46    20.2  648.73    30.3  646.94   131.5  642.83   151.7  639.27
   192.2   625.9     263   615.8   536.1  608.92   609.7  584.07   617.1   583.5
   644.7  583.62   657.5  584.91     698  605.65   728.3   611.7   768.8  629.58
   799.1  634.56   839.6   654.3   920.5  681.99   991.3  708.94  1021.7  722.02
  1112.7  771.54  1193.6  792.43    1224  797.38    1315  803.87  1375.7  812.58
  1476.8  830.13  1577.9  855.16  1699.3  864.61  1840.8  889.84  1992.5  907.69
#Mann= 3 , 0 , 0
       0     .08       0   609.7    .045       0   644.7     .08       0
Bank Sta=609.7,644.7
XS Rating Curve= 0 ,0
Exp/Cntr=0.3,0.1

Type RM Length L Ch R = 1 ,6355.1  ,859,856.9,854.9
XS GIS Cut Line= 3
     1555385.471      439158.804     1556181.474      439520.815
     1557375.054      440200.471
#Sta/Elev= 30
    10.1  687.33    50.3  670.06    90.5  655.87   150.8  642.93   231.2  620.77
   301.5   605.9   412.1  597.12   432.2  587.88   444.9  584.19   462.4  583.48
   479.9   583.5   502.6  585.98   522.7  595.06   532.7  597.26   773.9  618.01
   824.2  633.38   844.3     637   914.9  638.87   965.4  644.99  1005.7  645.13
  1046.1  654.68  1227.9  677.38  1389.5  701.51  1520.8   723.6  1722.8  745.44
  1904.6  771.44  1995.5  776.78  2157.1  771.88  2187.4  769.84    2248  756.49
#Mann= 3 , 0 , 0
    10.1     .08       0   444.9    .045       0   479.9     .08       0
Bank Sta=444.9,479.9
XS Rating Curve= 0 ,0
Exp/Cntr=0.3,0.1

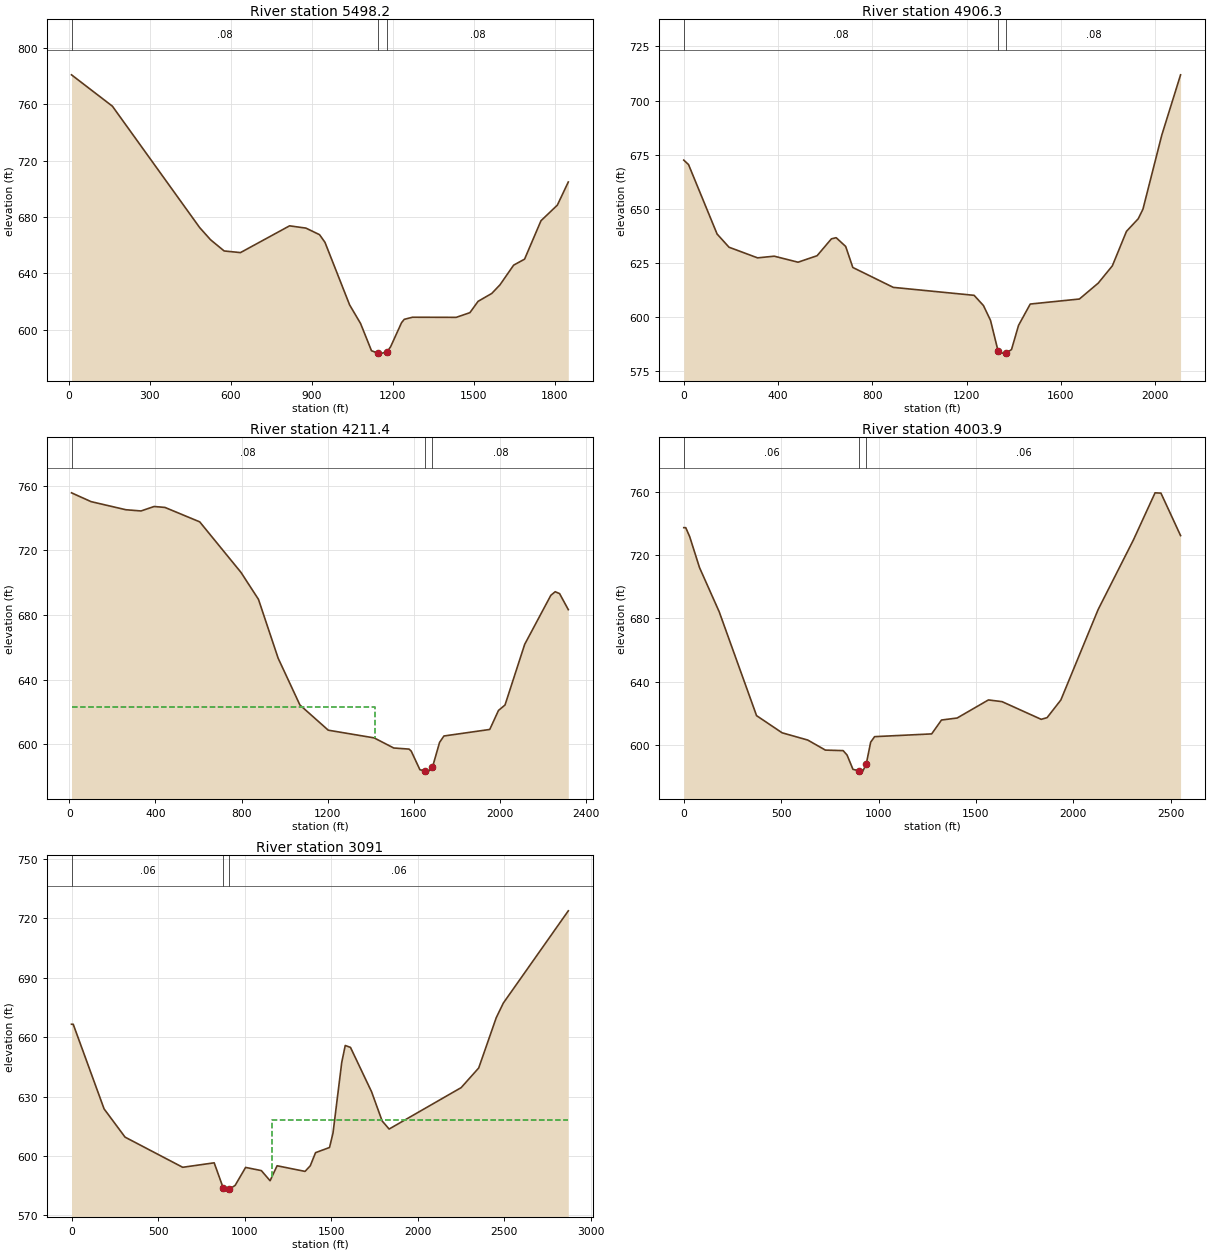
Type RM Length L Ch R = 1 ,5498.2  ,595.9,591.8,587.7
XS GIS Cut Line= 3
     1554750.166      439226.289     1555229.433      440033.148
     1556088.708      440335.664
#Sta/Elev= 30
    10.1  780.73   161.5   758.5   484.4   672.5   524.7  663.86   575.2  655.88
   635.7  654.72   817.4  673.69   877.9  672.08   928.4  667.42   948.6  661.96
  1039.7  617.67  1080.2   604.5  1120.7  585.16  1143.6   583.5  1161.1  583.46
  1178.6  584.46  1191.5  587.98    1232  605.03  1242.1  607.42  1272.5   608.9
  1434.4  608.82    1485  612.14  1515.4  620.18    1566  625.76  1596.4  631.87
    1647  645.82  1687.5  650.07  1748.2  677.29  1808.9  688.39  1849.4  704.78
#Mann= 3 , 0 , 0
    10.1     .08       0  1143.6    .045       0  1178.6     .08       0
Bank Sta=1143.6,1178.6
XS Rating Curve= 0 ,0
Exp/Cntr=0.3,0.1

Type RM Length L Ch R = 1 ,4906.3  ,695.9,694.9,694
XS GIS Cut Line= 4
     1554372.395      439655.854     1555081.328      440626.162
      1555478.76      440712.093     1555972.865      440644.064
#Sta/Elev= 30
       0  672.54    20.2  670.48   141.4  638.41   191.9  632.33     313  627.42
   383.7  628.19   484.7  625.41   565.5  628.41   626.1  636.19   646.3  636.73
   686.7  632.69     717  622.98   888.7  613.79  1231.5  610.12  1271.1  605.39
  1300.9   598.6    1333  584.47  1350.5  583.44    1368   583.5  1390.1   585.1
  1419.9  596.26  1469.5   606.1  1678.1  608.42  1757.9  615.76  1817.8  623.75
  1877.7  639.67  1927.5  645.47  1947.5  649.89  2027.3  684.04  2107.1  711.91
#Mann= 3 , 0 , 0
       0     .08       0    1333    .045       0    1368     .08       0
Bank Sta=1333,1368
XS Rating Curve= 0 ,0
Exp/Cntr=0.3,0.1

Type RM Length L Ch R = 1 ,4211.4  ,208,207.5,206.9
XS GIS Cut Line= 3
     1553646.701      440664.106      1554257.19      441177.265
     1555751.668      441456.564
#Sta/Elev= 30
    10.1  755.59     101  750.14   262.5  745.13   333.1  744.37   393.7  747.13
   444.2  746.56   605.7  737.63   797.5  706.35   878.6   689.7   969.8  653.35
  1071.2  624.32  1202.9  608.74  1415.8  603.99    1507  597.73    1578  597.05
  1588.1  595.83  1628.6  584.27  1651.7  583.59  1669.2  583.42  1686.7  585.76
  1719.9  601.21  1740.1  605.16    1953   609.2  1993.5  620.95  2023.9  624.33
  2115.2  661.84  2236.8   692.2  2257.1  694.41  2277.3  693.25  2317.9  683.33
#Mann= 3 , 0 , 0
    10.1     .08       0  1651.7    .045       0  1686.7     .08       0
#XS Ineff= 2 , 0
         1417.79  623.17
Permanent Ineff=
       F       F
Bank Sta=1651.7,1686.7
XS Rating Curve= 0 ,0
Exp/Cntr=0.3,0.1

Type RM Length L Ch R = 1 ,4003.9  ,893.4,913,932.5
XS GIS Cut Line= 4
     1554139.463      441367.687      1555462.31       441601.13
     1555923.638      441612.247     1556657.318      441745.643
#Sta/Elev= 30
       0  737.42    10.1  737.42    30.3  731.77    80.8  712.18   181.8  684.25
   373.7   618.5     505  607.64   636.3  603.07   727.2   596.7   818.1  596.37
   838.3  593.59   868.6  584.53   901.6  583.58   919.1   583.4   936.6  587.74
   959.5  601.72   979.7  605.21  1272.6  606.95  1323.1  615.73  1403.5     617
    1564  628.44  1634.2  627.35    1835  616.16  1865.2  617.24  1935.8  628.39
  2127.2   685.6  2308.6  729.71  2419.5  759.46  2449.7  759.28  2550.5  732.41
#Mann= 3 , 0 , 0
       0     .06       0   901.6    .045       0   936.6     .06       0
Bank Sta=901.6,936.6
XS Rating Curve= 0 ,0
Exp/Cntr=0.3,0.1

Type RM Length L Ch R = 1 ,3091    ,3062.9,3091,3119
XS GIS Cut Line= 4
     1553911.578      441667.828     1553972.718       441845.69
     1555101.028      442712.766     1556334.944      442957.326
#Sta/Elev= 30
       0  666.51     9.9  666.51   188.1   623.8   309.2  609.54   642.2  594.31
   823.9  596.57     877  583.67   894.5  583.29     912  583.31     945  585.18
  1005.5  594.25  1096.4  592.64  1146.8  587.52  1187.2  595.08  1348.7  592.24
  1378.9  595.08  1409.2  601.69    1490  604.31  1510.1  611.58  1560.6  647.25
  1580.8  655.79  1611.1  654.82  1732.8  632.45  1793.7  617.73  1834.2  613.62
  2250.2  634.52  2351.6  644.44  2453.1  669.88  2493.6  677.18    2869  723.76
#Mann= 3 , 0 , 0
       0     .06       0     877    .045       0     912     .06       0
#XS Ineff= 2 , 0
                         1157.72          618.38
Permanent Ineff=
       F       F
Bank Sta=877,912
XS Rating Curve= 0 ,0
Exp/Cntr=0.3,0.1

Chan Stop Cuts=-1
Use User Specified Reach Order=0